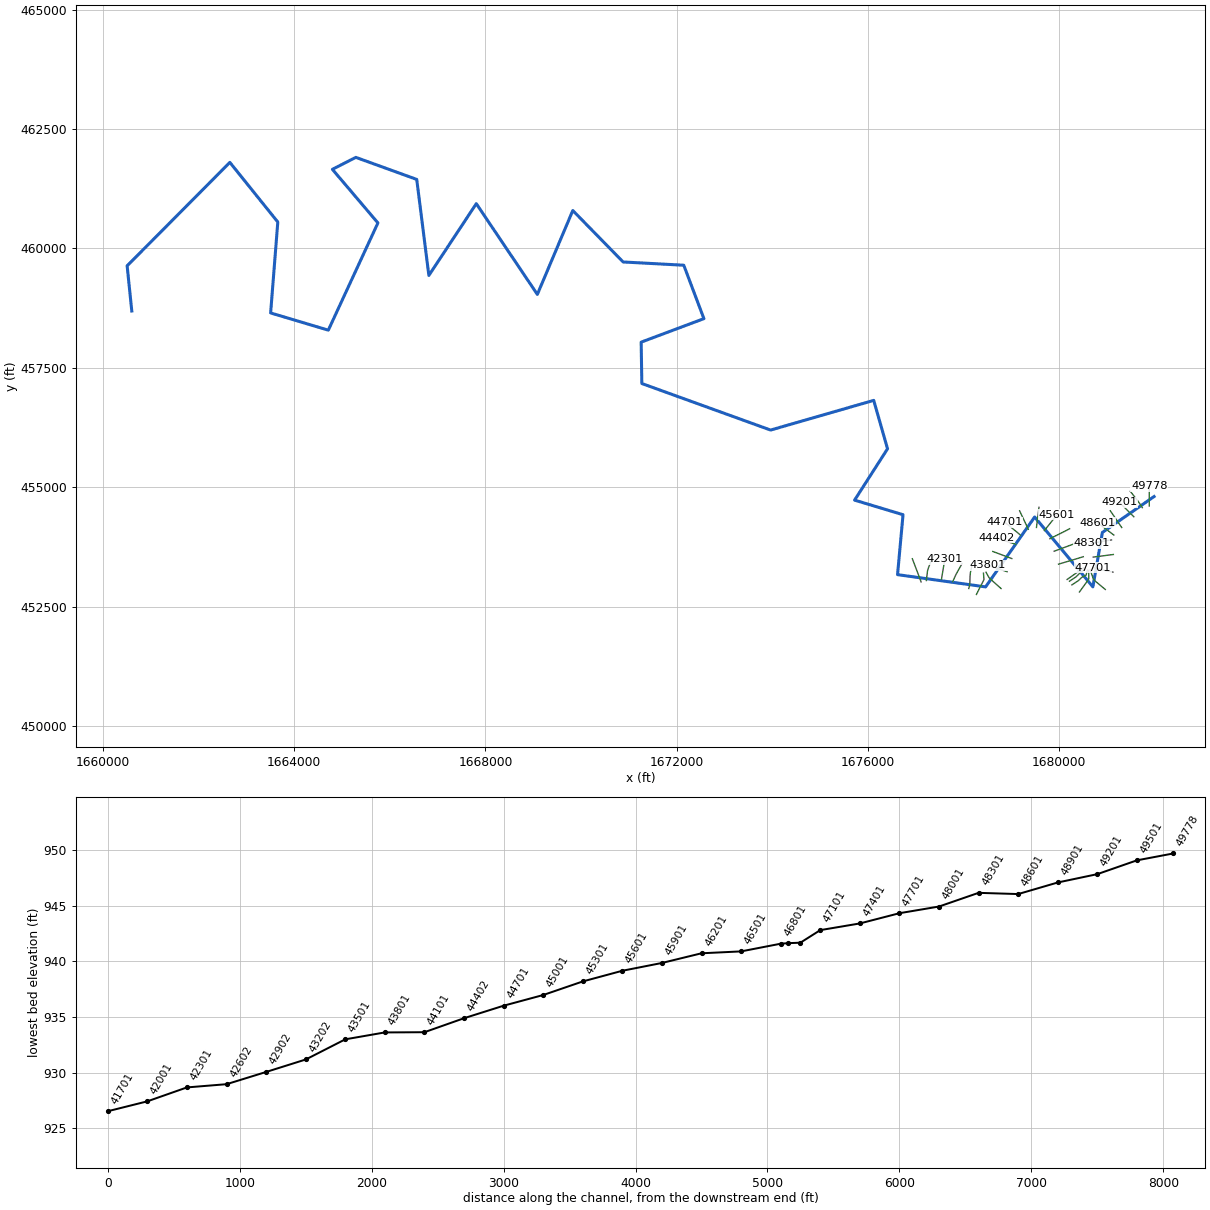
--- PenFrkFshCk.prj (project) ---

Proj Title=PenFrkFshCk
Current Plan=p01
Default Exp/Contr=0,0
English Units
Geom File=g01
Flow File=f01
Plan File=p01
BEGIN DESCRIPTION:
---------- MODELED AS PART OF WVEM CTP PROGRAM, 2025----------
Stream Name: Pennsylvania Fork Fish Creek
Flood Zone: AFH
Marshall County, WV
HEC-RAS Version: RAS 6.6
Vertical Datum: NAVD88
Projection: NAD 1983 StatePlane West Virginia N FIPS 4701 (US Feet)
Terrain: 1-meter West Virginia FEMA R3 South Central (collected 2018-2019)
Land Use: 2024 NLCD
Hydrologic Method:
Duda et al., "Estimation of magnitude and frequency of floods for rural, unregulated streams in and near Virginia and West Virginia." September 8, 2025.
Additional Model Notes:
None
END DESCRIPTION:
DSS Export Rating Curves= 0
DSS Export Rating Curve Sorted= 0
DSS Export Volume Flow Curves= 0
DXF OffsetX= 0
DXF OffsetY= 0
DXF ScaleX= 0
DXF ScaleY= 0

--- PenFrkFshCk.p01 (plan) ---

Plan Title=Floodplain
Program Version=6.60
Short Identifier=Floodplain
Geom File=g01
Flow File=f01
Subcritical Flow
K Sum by GR= 0
Std Step Tol= 0.01
Critical Tol= 0.01
Num of Std Step Trials= 20
Max Error Tol= 0.3
Flow Tol Ratio= 0.001
Split Flow NTrial= 30
Split Flow Tol= 0.02
Split Flow Ratio= 0.02
Log Output Level= 0
Friction Slope Method= 1
Unsteady Friction Slope Method= 2
Unsteady Bridges Friction Slope Method= 1
Parabolic Critical Depth
Global Vel Dist= 0 , 0 , 0
Global Log Level= 0
CheckData=False
Encroach Param=-1 ,0,0, 0
Flow Ratio Tolerance=0.1
Flow Ratio Min Ratio=0.5
Flow Ratio Max Ratio=4
Flow Ratio Max Iterations= 10
Mapping Interval=1HOUR
Computation Time Step Use Courant=        0
Computation Time Step Use Time Series=    0
Computation Time Step Count To Double=0
Computation Time Step Max Doubling=0
Computation Time Step Max Halving=0
Computation Time Step Residence Courant=0
Run HTab= 0
Run UNet= 0
Run Sediment= 0
Run PostProcess= 0
Run WQNet= 0
Run RASMapper=-1
UNET Theta= 0
UNET Theta Warmup= 0
UNET ZTol= 0
UNET ZSATol= 0
UNET MxIter= 0
UNET Max Iter WO Improvement= 0
UNET MaxInSteps= 0
UNET DtIC= 0
UNET DtMin= 0
UNET MaxCRTS= 0
UNET WFStab= 0
UNET SFStab= 0
UNET WFX= 1
UNET SFX= 1
UNET Gravity=32.17405
UNET 1D Methodology=Finite Difference
UNET DSS MLevel= 1
UNET Pardiso=0
UNET DZMax Abort= 0
UNET Use Existing IB Tables= 0
UNET Froude Reduction=False
UNET Froude Limit= 0
UNET Froude Power= 0
UNET D1 Cores= 0
UNET WindReference=Eulerian
UNET WindDragFormulation=Hsu (1988)
UNET D2 Coriolis=0
UNET D2 Cores= 0
UNET D2 Theta= 1
UNET D2 Theta Warmup= 1
UNET D2 Z Tol= 0.01
UNET D2 Volume Tol= 0.01
UNET D2 Max Iterations= 20
UNET D2 Advanced Convergence=0
UNET D2 WS Max Tol=0.15
UNET D2 WS RMS Tol=0.002
UNET D2 WS Stall Tol=1
UNET D2 Equation= 0
UNET D2 RampUpFraction=0.1
UNET D2 TimeSlices= 1
UNET D2 Turbulence Formulation=Non-Conservative (original)
UNET D2 Eddy Viscosity=0.3
UNET D2 Transverse Eddy Viscosity=0.1
UNET D2 Smagorinsky Mixing=0
UNET D2 BCVolumeCheck=0
UNET D2 Cores=0
UNET D2 SolverType=PARDISO (Direct)
UNET D2 Minimum Iterations= 3
UNET D2 Maximum Iterations= 30
UNET D2 Restart Number= 10
UNET D2 Relaxation Coeff=1.3
UNET D2 SOR Precondition Iterations= 10
UNET D2 ILUT Maximum Fill= 8
UNET D2 ILUT Tolerance=1E-08
UNET D2 Convergence Tolerance=0.00001
PS Theta= 1
PS WS Tol= 0.01
PS Volume Tol= 0.01
PS Max Iterations= 20
PS Equation= 0
PS Advance Time Step=-1
PS Target Courant=0.9
PS Time Slices= 1
PS Iterate With 2D=0
PS Project Initial WSE from DS=-1
PS Ramp Up Initial WSE from US=-1
PS Cores=0
UNET D1D2 MaxIter= 0
UNET D1D2 ZTol=0.01
UNET D1D2 QTol=0.1
UNET D1D2 MinQTol=1
Write IC File= 0
Write IC File at Fixed DateTime=0
Write IC File at Sim End=0
Echo Input=False
Echo Parameters=False
Echo Output=False
Write Detailed= 0
HDF Write Warmup=0
HDF Write Time Slices=0
HDF Flush=0
HDF Compression= 1
HDF Chunk Size= 1
HDF Spatial Parts= 1
HDF Use Max Rows=0
HDF Fixed Rows= 1
Calibration Method= 0
Calibration Iterations= 20
Calibration Max Change=0.05
Calibration Tolerance=0.2
Calibration Maximum=1.5
Calibration Minimum=0.5
Calibration Optimization Method= 1
WQ AD Non Conservative
WQ ULTIMATE=-1
WQ Max Comp Step=1HOUR
WQ Output Interval=15MIN
WQ Output Selected Increments= 0
WQ Create Restart=0
WQ Fixed Restart=0
WQ System Summary=0
WQ Write To DSS=0
Sorting and Armoring Iterations= 10
XS Update Threshold= 0.02
Bed Roughness Predictor= 0
Processes Affected by Predictor=Sediment Only
Hydraulics Update Threshold= 0.02
Energy Slope Method= 1
Volume Change Method= 1
Sediment Retention Method= 0
Sediment TS Multiplier= 1
Warm Up Method= 0
XS Weighting Method= 0
Number of US Weighted Cross Sections= 1
Number of DS Weighted Cross Sections= 1
Upstream XS Weight=0
Main XS Weight=1
Downstream XS Weight=0
Number of DS XS's Weighted with US Boundary= 1
Upstream Boundary Weight= 1
Weight of XSs Associated with US Boundary= 0
Number of US XS's Weighted with DS Boundary= 1
Downstream Boundary Weight= 0.5
Weight of XSs Associated with DS Boundary= 0.5
Percentile Method= 0
Sediment Output Level= 3
Mass or Volume Output= 0
Output Increment Type= 1
Profile and TS Output Increment= 1
Transport Output Increment 1
XS Output Flag= 0
XS Output Increment= 10
Read HDF5 Sediment Hotstart= 0
Sediment Hotstart Type= 0
Write Gradation File= 0
Read Gradation Hotstart= 0
Write HDF5 File= 1
Write Binary Output= 1
Write DSS Sediment File= 0
DSS Sediment Output Type= 1
SV Curve= 0
Specific Gage Flag= 0
Subcell Erosion Methods= 0
Subcell Deposition Methods= 0
Advection Scheme= 1
Matrix Solver= 0
Implicit Weighting Factor= 1
Maximum Outer Loop Convergence Iterations= 5
Convergence Maximum Absolute= 0.001
Convergence RMSE= 0.0001
Grain Fractions Max Abs Error= 0.001
Max Subgrid Regions= 1
Max Subgrid Length Scale= 3.402823E+38
Initial Layer Thickness= 3
Min Layer Thickness= 0.1
Max Layer Thickness= 6
Number of Layers= 5

--- PenFrkFshCk.f01 (steady flow) ---

Flow Title=Flow
Program Version=6.60
Number of Profiles= 1
Profile Names=P100yr
River Rch & RM=PenFrkFshCk,Main,49778
    5580
River Rch & RM=PenFrkFshCk,Main,27004
    7180
Boundary for River Rch & Prof#=PenFrkFshCk,Main            , 1
Up Type= 0
Dn Type= 3
Dn Slope=0.0071
DSS Import GetInterval= 0
DSS Import GetPeak= 0
DSS Import FillOption= 0

--- PenFrkFshCk.g01 (geometry) ---

Geom Title=Geometry
Program Version=6.60

River Reach=PenFrkFshCk     ,Main
Reach XY= 30
1681986.93663565454806.498243927     1680906.102       454055.35
      1680707.01       452915.69     1679489.318      454378.292
      1678463.41      452915.212     1676621.272      453171.764
      1676736.11      454426.262     1675722.917      454731.528
     1676412.027      455806.363     1676122.873      456819.355
     1673966.227      456198.224     1671272.756      457172.623
     1671258.583      458038.622     1672571.047      458530.442
     1672150.095      459648.729     1670881.568      459716.762
     1669828.479      460793.946     1669087.206      459037.852
     1667810.175      460937.098     1666818.032       459434.71
     1666564.267      461444.978     1665290.667      461906.489
        1664800.      461656.1781665752.21579884460534.146165583
     1664715.093      458289.493     1663508.333         458650.
     1663658.333      460552.778     1662655.555      461801.389
     1660506.945      459636.111     1660604.167      458690.972

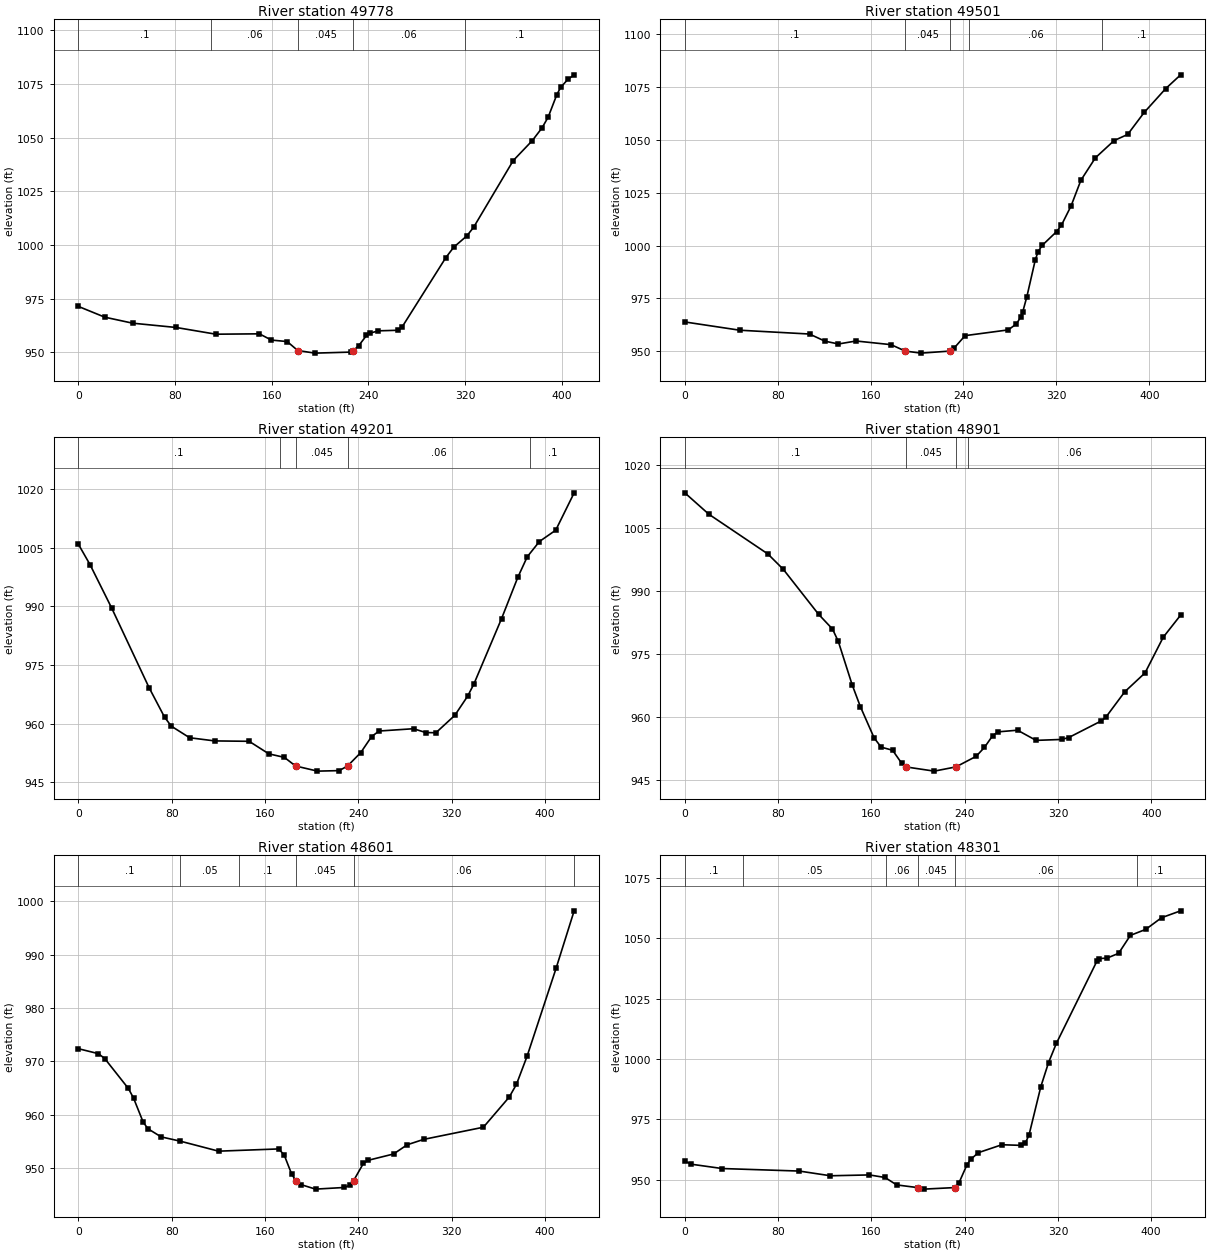
Type RM Length L Ch R = 1 ,49778   ,262.1,276.8,289.3
XS GIS Cut Line= 2
1681887.05663354454608.2561922511681885.94201157455018.437074905
#Sta/Elev= 30
       0  971.43    21.9  966.41    44.9  963.62    80.9  961.62   113.8  958.49
   149.8  958.66   159.7  955.76   172.8  955.06  181.55950.8856   195.8  949.68
   225.3  950.16  227.48 950.884   231.9  953.09   238.4   957.9   241.7  959.03
   248.3  960.06   264.7  960.32   267.9  961.89     304   994.1   310.6     999
   321.3 1004.18     327 1008.23   359.8  1039.3   375.5 1048.55   383.5 1054.42
   388.7 1059.51   395.9 1070.05   399.2 1073.51   405.1 1077.13   410.2 1079.21
#Mann= 5 ,-1,0
       0      .1       0     110     .06       0  181.55    .045       0
  227.48     .06       0     320      .1       0
Bank Sta=181.55,227.48
XS Rating Curve= 0 ,0
Exp/Cntr(USF)=0,0
Exp/Cntr=0.3,0.1

Type RM Length L Ch R = 1 ,49501   ,296.8,300,301.4
XS GIS Cut Line= 6
1681741.56715892 454573.94121559  1681693.083332454648.981091753
1681650.63262951 454711.000652761681588.94443268454789.706204012
  1681542.678121454848.7352854161681488.70086676454917.602929845
#Sta/Elev= 30
       0  963.82    47.4   959.9   107.4   958.1   120.7  954.72   132.3  953.39
   147.5   954.8   177.6  953.07   189.9950.0233   203.5  949.06  228.21950.0242
   231.8  951.37   241.4  957.34   278.6  960.06   285.6  962.91   289.3  966.13
     291  968.51   294.6  975.82   301.9  993.35   304.3  997.13   307.7 1000.02
   320.2 1006.59   324.4 1009.67   332.7  1018.8   341.1 1030.88   353.6 1041.52
   369.7 1049.67   381.4 1052.58   395.6 1062.98   414.1 1074.25     427  1080.8
#Mann= 5 ,-1,0
       0      .1       0   189.9    .045       0  228.21      .1       0
   244.5     .06       0   359.5      .1       0
Bank Sta=189.9,228.21
XS Rating Curve= 0 ,0
Exp/Cntr(USF)=0,0
Exp/Cntr=0.3,0.1

Type RM Length L Ch R = 1 ,49201   ,304.4,300,296.2
XS GIS Cut Line= 6
1681563.58818418454383.4753891681681501.71626067454445.347312674
1681448.68355834454498.3803430941681377.97274175454569.091159672
1681324.93971135454622.1238619981681263.06811592454683.995785505
#Sta/Elev= 30
       0 1005.89    10.1 1000.61    28.7  989.47    60.6   969.2    73.9  961.63
    79.7  959.32    95.4  956.36   116.9  955.55   146.4  955.45   163.3  952.24
   176.6  951.34  186.16949.1382     205  947.82   223.6  947.95  230.81949.1387
   242.1  952.57   251.4  956.67   257.8  958.08   287.3  958.67   297.8  957.69
   306.5  957.64   322.7  962.09   333.7     967     339  970.07   362.8  986.86
   376.7   997.4   384.8 1002.66   395.2 1006.56   409.2 1009.46     425 1019.02
#Mann= 5 ,-1,0
       0      .1       0   172.5     .06       0  186.16    .045       0
  230.81     .06       0   387.5      .1       0
Bank Sta=186.16,230.81
XS Rating Curve= 0 ,0
Exp/Cntr(USF)=0,0
Exp/Cntr=0.3,0.1

Type RM Length L Ch R = 1 ,48901   ,291.8,300,307
XS GIS Cut Line= 6
1681310.37018667454157.833123922 1681261.3207441454230.292952761
1681219.27817726454292.4010962551681163.22153084454375.211954251
 1681120.7285056454437.0153083351681070.64724092454508.776319668
#Sta/Elev= 30
       0 1013.31    20.6 1008.22    71.2  998.76    84.4  995.11   114.7  984.39
   126.6  980.89   131.6  977.93   143.4  967.66   150.5  962.41   162.3  954.97
   168.3  952.78   178.1  952.04   185.8  948.98  189.38948.0776   213.8  947.07
  232.45948.0775   249.7  950.59   256.8   952.7   263.9  955.51   268.6  956.42
   285.2  956.81   301.1  954.39   322.9  954.61     329  955.05     357  959.02
     361  959.94   377.1  965.95   394.5  970.45   410.1  978.94     425   984.2
#Mann= 4 ,-1,0
       0      .1       0  189.38    .045       0  232.45      .1       0
   242.5     .06       0
Bank Sta=189.38,232.45
XS Rating Curve= 0 ,0
Exp/Cntr(USF)=0,0
Exp/Cntr=0.3,0.1

Type RM Length L Ch R = 1 ,48601   ,284.3,300,316.1
XS GIS Cut Line= 6
1681145.55161868454000.8577160841681075.64559051454053.483267009
  1681015.726419454098.5907883351680935.83419034454158.733712673
1680875.91501884454203.8412339991680806.80557701454257.524853677
#Sta/Elev= 30
       0  972.37    17.2  971.44    22.6  970.53    42.9  964.91    47.3  963.12
    55.5  958.64    59.6  957.36      71  955.83    87.5  955.02   120.2  953.15
   171.8  953.57   176.5  952.41   182.8  948.88  186.49947.5963     191  946.87
   203.3  946.03     228  946.34   232.7  946.76  235.88947.5967   244.4  950.88
   248.5  951.44   270.2  952.62   281.9  954.35     296  955.36   347.2  957.64
   369.3  963.28   375.5  965.66   384.6  970.92   409.5  987.44     425  998.23
#Mann= 6 ,-1,0
       0      .1       0    87.5     .05       0   137.5      .1       0
  186.49    .045       0  235.88     .06       0  425.01      .1       0
Bank Sta=186.49,235.88
XS Rating Curve= 0 ,0
Exp/Cntr(USF)=0,0
Exp/Cntr=0.3,0.1

Type RM Length L Ch R = 1 ,48301   ,301.6,300,298.9
XS GIS Cut Line= 6
1681096.84371084453898.2388268411681009.87374042453887.208993256
1680936.19212925453873.2090212551680837.94987167453854.543048084
1680764.26793243453840.5430760831680678.30583401453824.210431591
#Sta/Elev= 30
       0  957.76     5.5  956.46      32  954.67    98.2  953.62   124.9  951.67
   158.3  952.02   171.7  950.96   181.7  947.88  199.59946.7852   205.1  946.14
  231.66946.7857   235.1  948.73   241.8  956.02   245.1  958.45   251.8  961.25
   271.9  964.52   288.6  964.26   291.9   965.1   295.2  968.57   305.3  988.55
   311.9   998.5   318.6 1006.45   353.4 1040.53   355.4 1041.62     362 1041.79
     372 1043.77   382.1 1051.21   395.3  1053.7   408.8 1058.52   425.2 1061.38
#Mann= 6 ,-1,0
       0      .1       0      50     .05       0  172.67     .06       0
  199.59    .045       0  231.66     .06       0  387.67      .1       0
Bank Sta=199.59,231.66
XS Rating Curve= 0 ,0
Exp/Cntr(USF)=0,0
Exp/Cntr=0.3,0.1

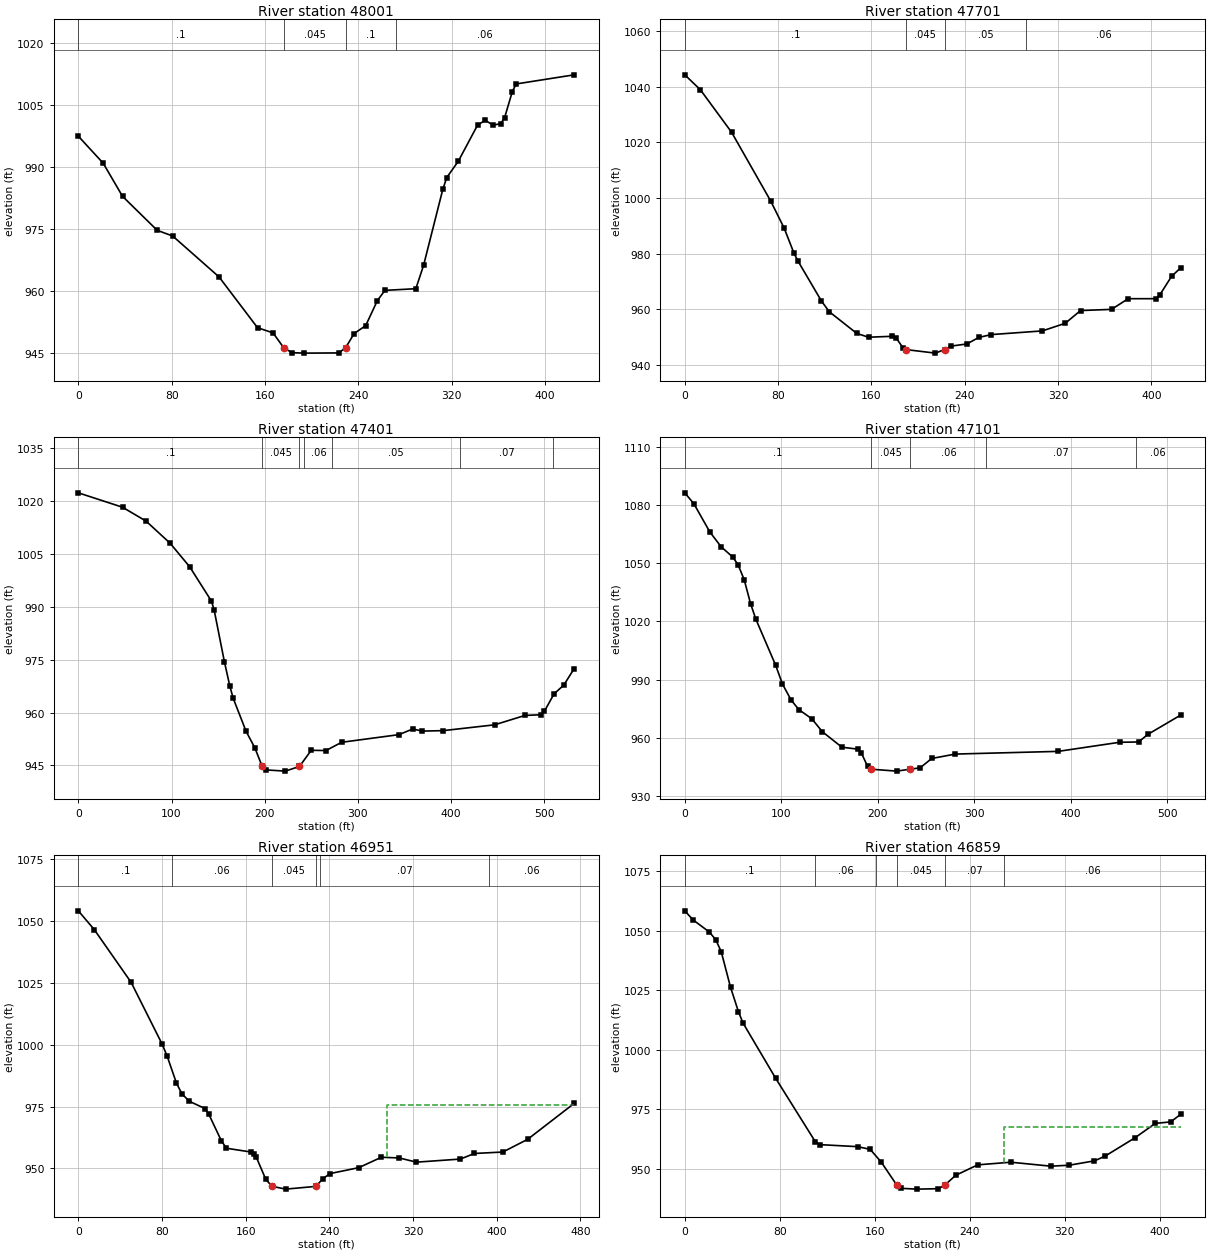
Type RM Length L Ch R = 1 ,48001   ,310.4,300,295.4
XS GIS Cut Line= 6
1681135.48142885453593.6869425031681048.70896459453582.426794425
1680974.33280101453572.7745827591680875.16436417453559.905842096
1680800.78787251453550.2539585081680714.01540826453538.993482336
#Sta/Elev= 30
       0  997.45    21.3  990.91    37.9  982.88    67.6  974.65    80.9  973.27
   120.6  963.37   153.6  951.07   166.9  949.81  176.15946.1752   183.1  945.03
   193.3  944.91   223.1  944.96  229.03946.1765   236.4  949.65   246.3  951.57
   256.3  957.62   262.8  960.11   289.3  960.51   295.9  966.14   312.4  984.57
   315.8  987.44   325.7  991.39   342.2 1000.13   348.8  1001.3   355.5 1000.12
   362.1 1000.49   365.4 1001.95     372 1008.26   375.3  1010.1     425 1012.31
#Mann= 4 ,-1,0
       0      .1       0  176.15    .045       0  229.03      .1       0
   272.5     .06       0
Bank Sta=176.15,229.03
XS Rating Curve= 0 ,0
Exp/Cntr(USF)=0,0
Exp/Cntr=0.3,0.1

Type RM Length L Ch R = 1 ,47701   ,308.3,300,291.4
XS GIS Cut Line= 6
1681127.44798034453224.0531673431681041.62269267 453241.37695159
1680968.33084451453257.3654366731680871.07972668453280.650823176
1680798.14122425453298.1146990061680713.04657817453318.489658251
#Sta/Elev= 30
       0 1044.21    13.4 1038.83    40.1  1023.6    73.6  998.95    85.2  989.17
    93.7  980.08    97.1  977.31   117.2  962.98   123.9  959.16   147.4   951.4
   157.5  950.02   177.7  950.35   181.1  949.83   186.9  946.31  189.43945.5982
   214.8  944.31  222.74945.5985   228.3  946.83   241.8   947.6     252  949.93
   262.6  950.96   306.6  952.29   326.2  955.03   339.3  959.59   365.9  960.02
   380.1  963.85   403.8  963.85   407.1  965.11   417.3  971.85   425.1  974.92
#Mann= 4 ,-1,0
       0      .1       0  189.43    .045       0  222.74     .05       0
  292.57     .06       0
Bank Sta=189.43,222.74
XS Rating Curve= 0 ,0
Exp/Cntr(USF)=0,0
Exp/Cntr=0.3,0.1

Type RM Length L Ch R = 1 ,47401   ,324,300,262.3
XS GIS Cut Line= 6
1680967.06280242452861.2090767621680899.84377676452917.225368917
1680842.22742218452965.2393805091680765.40572542453029.258281335
1680714.58036776453087.4973380861680652.08497025453269.270572492
#Sta/Elev= 30
       0 1022.25    47.4 1018.17    72.7 1014.23    98.5 1007.96   119.5 1001.28
   142.8  991.58   145.7  989.09   156.7  974.41   162.5  967.55   166.1  964.07
     180  954.66   189.4  949.98  197.31944.7056   201.2  943.74     222  943.39
  237.23944.7059   249.9  949.29   265.7  949.22   282.5  951.56     344  953.73
   358.8  955.33   369.1  954.73   391.8  954.87   446.6  956.51   479.3  959.18
   496.6  959.36   500.1  960.37   510.5  965.31   520.9  967.77     532  972.44
#Mann= 7 ,-1,0
       0      .1       0  197.31    .045       0  237.23      .1       0
   242.5     .06       0   272.5     .05       0   409.8     .07       0
   509.8     .06       0
Bank Sta=197.31,237.23
XS Rating Curve= 0 ,0
Exp/Cntr(USF)=0,0
Exp/Cntr=0.3,0.1

Type RM Length L Ch R = 1 ,47101   ,154.3,150.7,147.1
XS GIS Cut Line= 6
1680425.82930484452808.7305071651680477.16548826452879.588305086
1680521.16802493452940.3237479181680579.83785509453021.304229006
1680621.79643258453083.5203119221680618.90635725453259.731571078
#Sta/Elev= 30
       0 1086.37     9.5 1080.67    25.9 1066.22    37.7 1058.51    49.6 1053.28
    55.1 1049.36    61.5 1041.63    68.2 1029.11    73.6 1021.22    94.1  997.48
   101.1  987.84   110.1  979.51   118.2  974.53   131.6  969.81   142.5  963.14
   162.8  955.13     179  954.15     183  952.09   189.4  945.28   192.7   943.8
   219.5  942.79   233.7943.8006   243.8  944.48   255.9  949.32   280.3  951.59
   386.9  952.98   450.5  957.67   470.2  957.83     480   961.8   513.8  971.69
#Mann= 5 ,-1,0
       0      .1       0   192.7    .045       0   233.7     .06       0
   312.5     .07       0  467.54     .06       0
Bank Sta=192.7,233.7
XS Rating Curve= 0 ,0
Exp/Cntr(USF)=0,0
Exp/Cntr=0.3,0.1

Type RM Length L Ch R = 1 ,46951   ,91.7,91.2,91.4
XS GIS Cut Line= 5
1680268.35841332452957.1266354031680402.89915635453045.856670224
1680473.06090944453114.0420359081680565.06052344453160.645739059
1680592.64454774453269.042048614
#Sta/Elev= 30
       0 1054.04    15.2 1046.48    50.5 1025.14      80  1000.3    84.8  995.49
    93.8  984.47      99  980.15   106.1  977.13   121.3  974.16   124.8  971.83
   136.7  961.21   141.6  958.17   165.1  956.64   167.5  955.88   169.9   954.8
   179.1   945.7     185942.8111   198.3  941.66  227.14942.7703   233.7  945.85
   240.7  947.94   268.1  950.33   289.7  954.53   306.8  954.25   323.2  952.55
   365.2   953.8   378.7  956.06   405.8  956.64   429.5  961.76     474  976.27
#Mann= 6 ,-1,0
       0      .1       0      90     .06       0     185    .045       0
  227.14     .06       0  231.17     .07       0  392.13     .06       0
#XS Ineff= 2 , 0
                          295.13          975.74
Permanent Ineff=
       F       F
Bank Sta=185,227.14
XS Rating Curve= 0 ,0
Exp/Cntr(USF)=0,0
Exp/Cntr=0.3,0.1

Type RM Length L Ch R = 1 ,46859   ,61.2,58,55.6
XS GIS Cut Line= 4
1680217.03944021453034.1752446311680351.58018323453122.905279453
1680421.74193632453191.0906451361680543.38736149453293.033195799
#Sta/Elev= 30
       0 1058.26       7 1054.45    20.6  1049.4      26 1046.23    30.7 1041.12
    38.5 1026.28    45.2 1015.97    49.1 1011.19    76.6  988.03     110  961.46
   113.6  960.27   145.7  959.42   156.2  958.28   165.6  952.88  178.74943.1834
   181.9  941.96   195.4  941.62   213.7   941.8   218.9  943.23   228.2  947.41
   246.8   951.8   274.7   952.9   308.2  951.25   323.6  951.62   345.1  953.47
   353.9   955.4   379.3  963.15   396.4  969.19   409.3  969.78   417.7  972.95
#Mann= 6 ,-1,0
       0      .1       0     110     .06       0  161.17     .07       0
  178.74    .045       0   218.9     .07       0     269     .06       0
#XS Ineff= 2 , 0
                          268.55          967.45
Permanent Ineff=
       F       F
Bank Sta=178.74,218.9
XS Rating Curve= 0 ,0
Exp/Cntr(USF)=0,0
Exp/Cntr=0.3,0.1

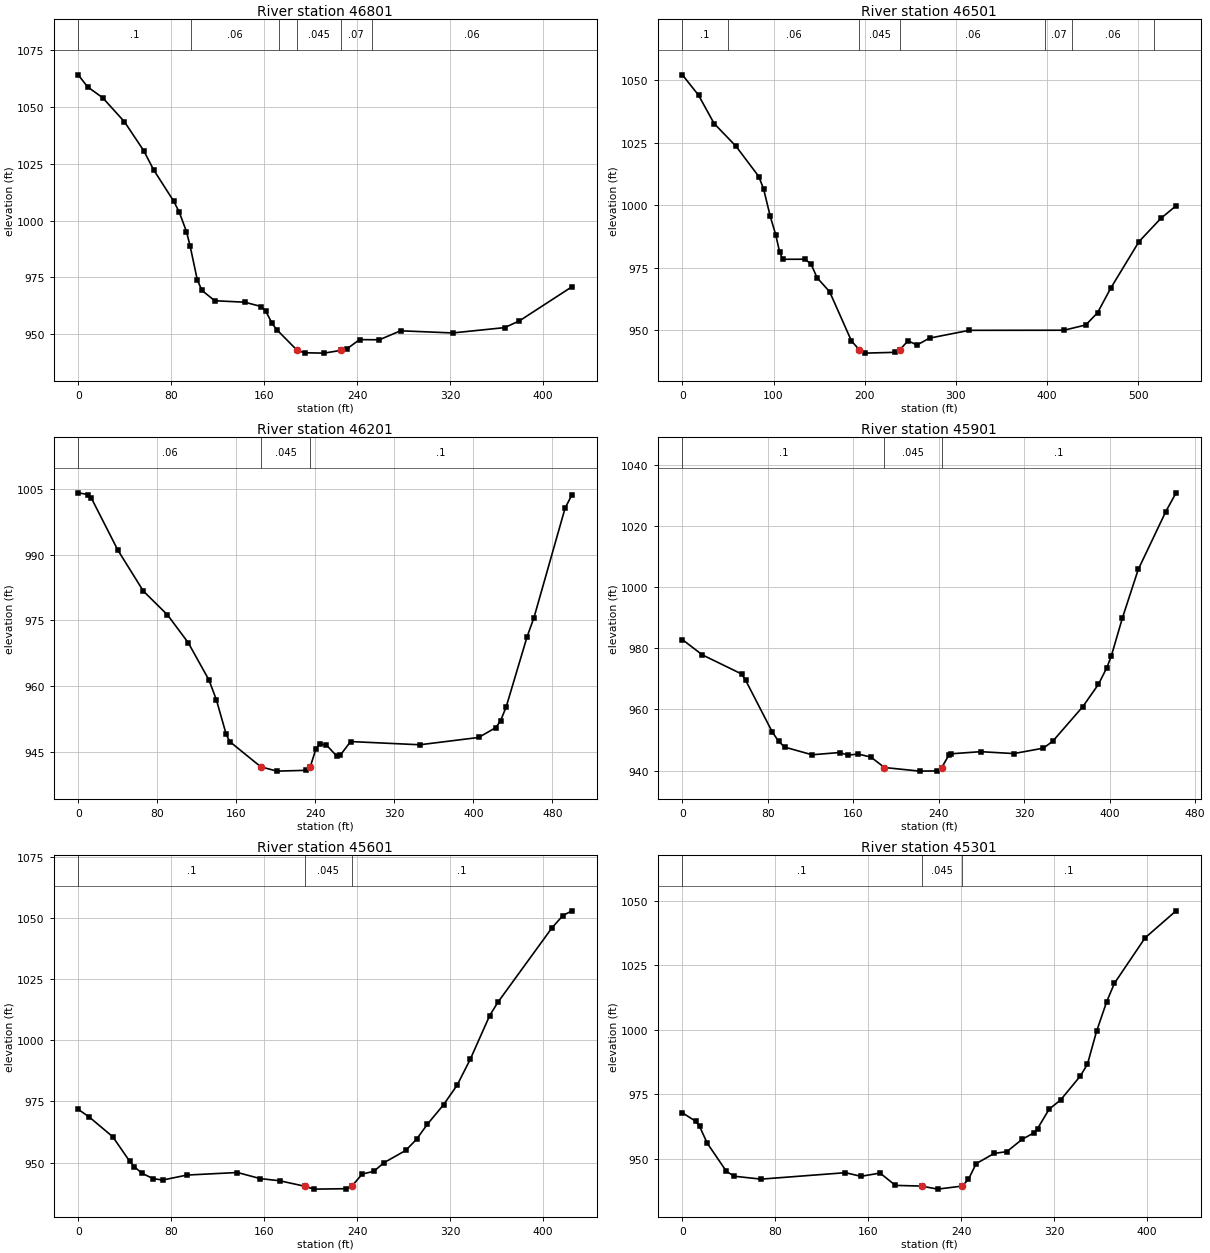
Type RM Length L Ch R = 1 ,46801   ,306.4,300,292.7
XS GIS Cut Line= 6
1680167.82522768453070.4192882631680239.26045226453120.949042842
1680300.49097285453164.260307923 1680382.1312295453222.008223921
  1680443.361422453265.319489002 1680514.7966466453315.849243596
#Sta/Elev= 30
       0 1064.21       8 1058.92      21 1054.14    39.8 1043.51    56.3 1030.85
    64.8 1022.45    82.2 1008.51    86.9 1003.78    93.2  995.11    96.3   988.8
   102.5  973.84   106.5   969.2   117.5  964.66   143.4  964.01   157.5   962.1
   161.4  960.09   166.9  954.64   170.8  951.96  188.54942.7599   194.9  941.73
   211.6  941.57  225.84 942.759   231.1  943.39   242.2  947.52   259.2  947.45
   277.5  951.42   322.3  950.46     367  952.81   379.8  955.79     425  970.81
#Mann= 6 ,-1,0
       0      .1       0    97.5     .06       0   172.5     .07       0
  188.54    .045       0  225.84     .07       0   252.5     .06       0
Bank Sta=188.54,225.84
XS Rating Curve= 0 ,0
Exp/Cntr(USF)=0,0
Exp/Cntr=0.3,0.1

Type RM Length L Ch R = 1 ,46501   ,298.7,300,301.6
XS GIS Cut Line= 6
1679988.46239743 453391.351389171680072.33460501453416.286050588
1680144.22488117453437.6587112551680240.07869209453466.156029582
1680311.96864018453487.5286902491680506.93889765453547.353276992
#Sta/Elev= 30
       0 1052.07    17.7 1043.95    34.8 1032.62    58.8 1023.54    83.8 1011.44
    89.1 1006.43    96.4  995.48   102.3  988.26   106.7  981.19   110.1  978.37
   134.1   978.4   140.9   976.6   147.8  970.97   161.5  965.39   185.4  945.75
  194.03942.2017   199.9  940.88   233.3   941.2  238.43942.1997   247.4   945.8
   257.3  944.13     271  946.87   314.6  949.99   418.5  950.03   442.4  952.14
   455.3  957.04   469.9  966.94   500.7  985.42   524.8  994.75   541.4  999.75
#Mann= 7 ,-1,0
       0      .1       0      50     .06       0  194.03    .045       0
  238.43     .06       0   397.5     .07       0   427.5     .06       0
   517.5     .05       0
Bank Sta=194.03,238.43
XS Rating Curve= 0 ,0
Exp/Cntr(USF)=0,0
Exp/Cntr=0.3,0.1

Type RM Length L Ch R = 1 ,46201   ,297.5,300,303.6
XS GIS Cut Line= 6
1679897.73390435453662.5883795021679979.80559058453692.926901504
1680050.15321893453718.9314426781680143.94994734453753.603945509
1680214.29724759453779.6084866671680366.21160708 453836.37371783
#Sta/Elev= 30
       0 1004.05     9.9 1003.66    13.4  1002.8    40.2  990.97    65.9  981.69
    90.3  976.28   111.3  969.95   132.3  961.46   139.8  956.96   149.8  949.06
   153.3  947.44  184.84941.6824   201.1  940.71   230.2  940.89  234.81941.6813
   240.7  945.83   244.2  946.88   251.2  946.67   261.7  944.11   265.2  944.33
   275.7  947.44   345.7  946.71   405.2  948.37   422.7  950.62   427.5   952.2
   433.1   955.3   454.3  971.29   461.3  975.67   492.8 1000.59   499.7  1003.6
#Mann= 3 ,-1,0
       0     .06       0  184.84    .045       0  234.81      .1       0
Bank Sta=184.84,234.81
XS Rating Curve= 0 ,0
Exp/Cntr(USF)=0,0
Exp/Cntr=0.3,0.1

Type RM Length L Ch R = 1 ,45901   ,291.3,300,310.7
XS GIS Cut Line= 6
1679808.22620934453923.8142350021679886.48852001453962.945390344
1679953.57073492453996.4863337581680043.01346943454041.208029091
1680110.09535626454074.7489725051680220.44724233454132.756676755
#Sta/Elev= 30
       0  982.85    18.7  977.85    55.4  971.62    59.1  969.63    84.1  952.69
    90.2  949.53    95.8  947.69   121.4  945.19   147.1  945.92     155  945.09
   164.8  945.41   176.5  944.43   189.2941.0167   222.2  939.84   238.2  939.91
  242.84941.0173   249.8  945.26   251.6  945.51   279.2   946.2   310.3  945.58
   337.9  947.35   346.6  949.56   374.9  960.93   389.5  968.23   397.2  973.54
   401.6  977.52     412  989.98   426.8  1005.8   452.6 1024.73   462.2 1030.84
#Mann= 3 ,-1,0
       0      .1       0   189.2    .045       0  242.84      .1       0
Bank Sta=189.2,242.84
XS Rating Curve= 0 ,0
Exp/Cntr(USF)=0,0
Exp/Cntr=0.3,0.1

Type RM Length L Ch R = 1 ,45601   ,293,300,313.5
XS GIS Cut Line= 6
1679692.27893467454094.3890250921679746.93958651454162.715003923
1679793.79152693454221.2801755071679856.26121825454299.367289677
1679903.11315867454357.9321331681679957.77413858454426.258111998
#Sta/Elev= 30
       0  971.79     9.7  968.56    29.8  960.53    44.4  950.45    48.4  948.24
    54.9  945.64    64.3  943.45    72.7  942.87    93.7   944.9   137.1  945.94
   156.7  943.44   173.5  942.56  194.92940.3228   202.9  939.14   230.5  939.31
  235.45940.3235   244.5   945.3   254.5  946.44   263.2  949.95   281.9  954.97
   291.2  959.52   300.5  965.66   314.5  973.67   326.2  981.71   337.5  992.29
   354.2 1010.15   361.2 1015.55   407.9  1046.1   417.2 1051.06     425    1053
#Mann= 3 ,-1,0
       0      .1       0  194.92    .045       0  235.45      .1       0
Bank Sta=194.92,235.45
XS Rating Curve= 0 ,0
Exp/Cntr(USF)=0,0
Exp/Cntr=0.3,0.1

Type RM Length L Ch R = 1 ,45301   ,292.7,300,313.5
XS GIS Cut Line= 6
1679526.95511834454159.4335144161679537.80844308454246.257815838
  1679547.111246454320.678598762 1679559.5147645454419.906418666
1679568.81756742454494.3275296691679579.67056409 454581.15183109
#Sta/Elev= 30
       0   967.8    11.5  964.51    14.8  962.54    21.4  956.01    37.9  945.09
    44.6  943.19    67.7  942.06   140.4  944.56   153.7  943.15   170.2  944.41
   183.4  939.63  205.86939.3583   219.8  938.18  240.77939.3584   246.2  941.93
   252.9  948.06   268.4  952.04   279.3  952.73   292.5  957.52   302.4  959.96
   305.8  961.71   315.7  969.18   325.6  972.79   342.5  982.03   348.7  986.66
   356.5  999.36   365.3 1010.98   371.9 1018.05   398.3 1035.69     425 1046.19
#Mann= 3 ,-1,0
       0      .1       0  205.86    .045       0  240.77      .1       0
Bank Sta=205.86,240.77
XS Rating Curve= 0 ,0
Exp/Cntr(USF)=0,0
Exp/Cntr=0.3,0.1

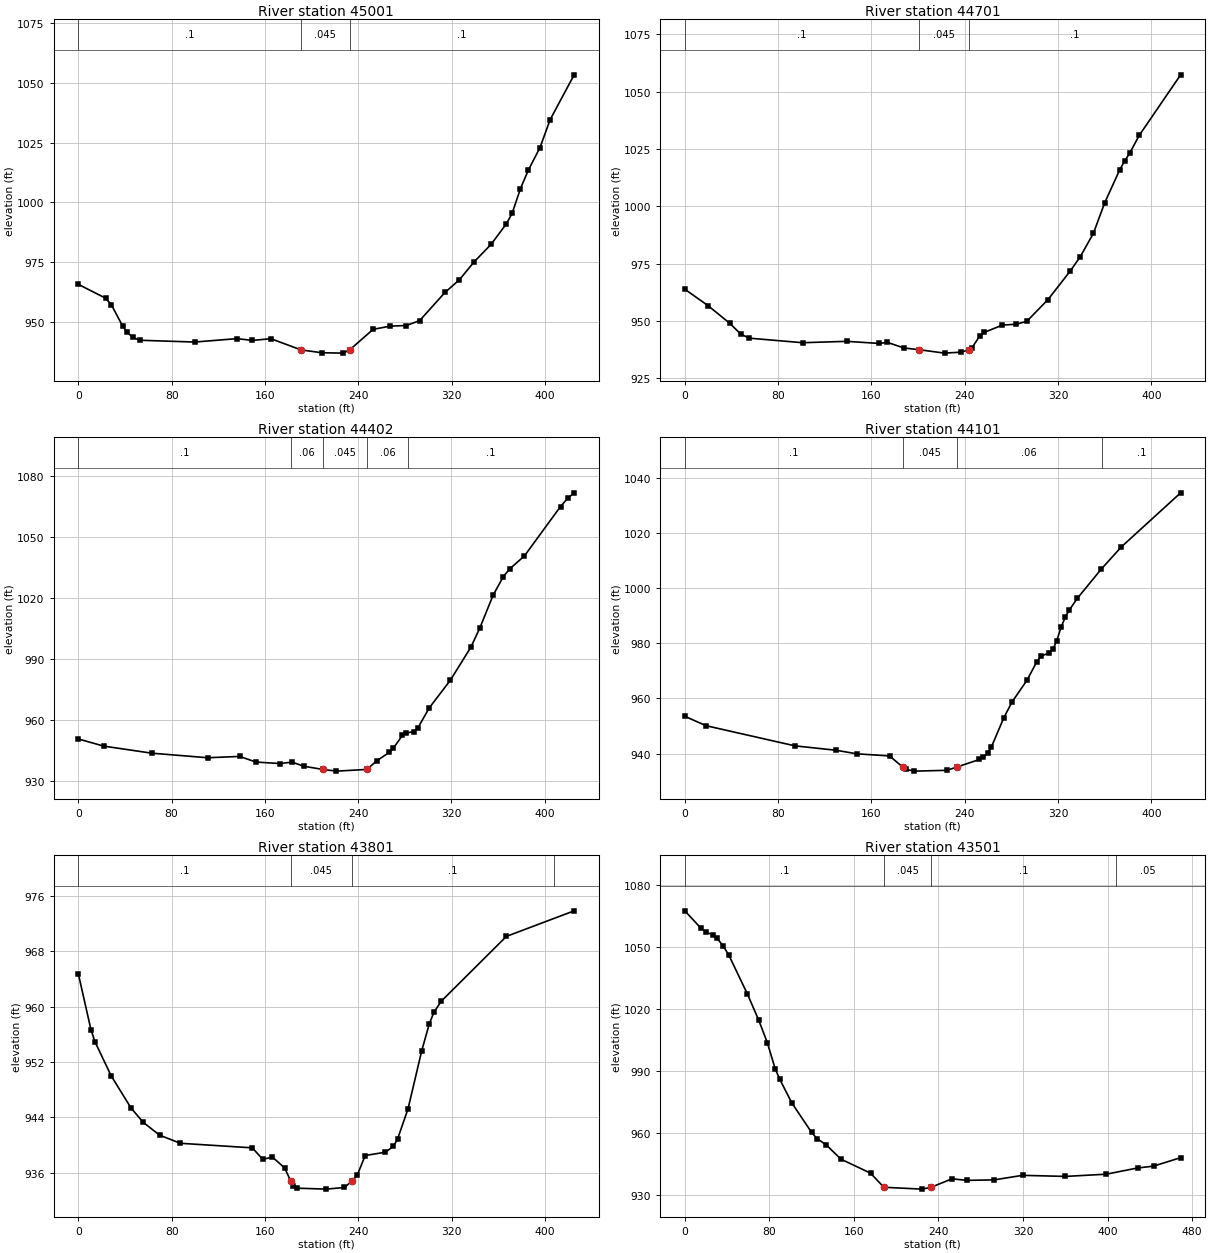
Type RM Length L Ch R = 1 ,45001   ,292.9,300,311.6
XS GIS Cut Line= 6
1679356.00172009454123.3181010931679318.67272651454202.455738083
1679286.67607135454270.2879514991679244.01408318454360.731012091
1679212.01775609454428.5635535871679174.68843442454507.701190591
#Sta/Elev= 30
       0  965.71    23.5   959.9    28.4  957.12      38  948.24    41.7  945.77
    46.5  943.57    52.5  942.35    99.7  941.59     136  943.02   149.2  942.27
     165     943  190.86938.3127   208.5  937.13   226.7  936.96  232.59938.3138
   252.7  946.91   267.5  948.26   281.1   948.5   292.6  950.57   314.3  962.35
   326.7  967.65   339.1  975.03   353.8  982.44   366.9  991.03   371.8  995.37
     379 1005.76   385.8 1013.56   395.7 1022.87   404.4 1034.56     425 1053.31
#Mann= 3 ,-1,0
       0      .1       0  190.86    .045       0  232.59      .1       0
Bank Sta=190.86,232.59
XS Rating Curve= 0 ,0
Exp/Cntr(USF)=0,0
Exp/Cntr=0.3,0.1

Type RM Length L Ch R = 1 ,44701   ,296.2,299.1,310.1
XS GIS Cut Line= 6
1679190.67265442454000.4882942591679124.15703942454057.375975758
1679066.01903234454104.7571145891678988.50147083454167.931857005
1678930.36346376454215.3126677571678862.53551543454270.590444341
#Sta/Elev= 30
       0  963.85      20  956.67    38.6  948.98    47.9  944.32    55.1  942.53
   100.9  940.54   138.7  941.14   166.7  940.22   173.7  940.68   187.7  938.26
  201.12937.4745   222.7     936   236.7  936.42  243.78937.4748     246   938.2
     253  943.63   256.7  945.05   272.3  948.23   283.8  948.59   293.1  949.83
   311.3  959.34   330.4  971.79   338.9  977.96   350.2  988.17     360 1001.61
   372.7  1015.8   376.9 1019.66   381.3 1023.11   389.6 1030.96     425 1057.29
#Mann= 3 ,-1,0
       0      .1       0  201.12    .045       0  243.78      .1       0
Bank Sta=201.12,243.78
XS Rating Curve= 0 ,0
Exp/Cntr(USF)=0,0
Exp/Cntr=0.3,0.1

Type RM Length L Ch R = 1 ,44402   ,304.1,300.9,301.8
XS GIS Cut Line= 6
1679094.58163926453808.9735854271679010.67301442453834.335739419
1678938.88149133453856.4265744981678844.41481675453889.283464178
1678774.05308084453915.2502757611678691.96499042453945.544834584
#Sta/Elev= 30
       0  950.71    21.8  947.19      63  943.71     111  941.47   138.5  942.12
   152.2  939.35   172.9  938.62   183.3  939.31   193.7  937.25  209.68 935.713
   221.4  934.88  247.43935.7125   256.3  940.09   266.7  944.09   270.2  946.14
   277.9  952.44   280.7  953.55   287.7  954.36   291.2  956.09   300.9  965.91
   319.2   979.7   336.7  995.89   344.4 1005.33   355.8 1021.51   364.6 1030.66
   369.9 1034.34   382.7 1040.84   413.6 1065.12   419.6  1069.1   425.3 1071.86
#Mann= 5 ,-1,0
       0      .1       0  182.77     .06       0  209.68    .045       0
  247.43     .06       0  282.79      .1       0
Bank Sta=209.68,247.43
XS Rating Curve= 0 ,0
Exp/Cntr(USF)=0,0
Exp/Cntr=0.3,0.1

Type RM Length L Ch R = 1 ,44101   ,299,300,300.8
XS GIS Cut Line= 6
1679011.65628017453508.2901316731678929.70171967453538.944269836
1678859.45481293453565.2191516761678765.79227059453600.252546176
1678695.54536384453626.5274280011678613.50911058453656.964375004
#Sta/Elev= 30
       0  953.54    18.2  950.12    94.4   942.8   129.9  941.19   147.4  939.91
   175.5  939.13  186.93935.0676   189.5  934.28   196.5  933.62   224.5  933.91
  232.95935.0685   252.5  937.85     256  938.69   259.5  940.13   262.7   942.3
   273.5  953.05   280.5  958.74   293.3  966.63   301.6  973.24   305.1  975.33
   312.1  976.52   315.6  977.86   318.8  981.01   322.6  985.94   326.1  989.55
   329.6  992.16   336.6  996.45     357 1007.01   374.3  1015.1     425  1034.7
#Mann= 4 ,-1,0
       0      .1       0  186.93    .045       0  232.95     .06       0
   357.5      .1       0
Bank Sta=186.93,232.95
XS Rating Curve= 0 ,0
Exp/Cntr(USF)=0,0
Exp/Cntr=0.3,0.1

Type RM Length L Ch R = 1 ,43801   ,307.6,299.9,290.4
XS GIS Cut Line= 6
1678913.30017768453233.1177817581678830.28295526453260.765692338
1678759.12528917453284.4638076721678664.24883851453316.061513498
1678593.09117243453339.7599569261678510.07427809453367.407867506
#Sta/Elev= 30
       0  964.73    10.8  956.68    14.2  954.93    28.1     950    45.3   945.3
    55.7  943.25    69.6  941.41    87.5  940.23   149.1  939.57   158.1  937.91
   166.4  938.23   176.8  936.67  182.13934.7463   183.7  934.06   187.1  933.74
   212.5   933.6   228.1  933.84   234.4 934.745     239  935.59   245.9  938.46
   263.2  938.94   270.1   939.8   273.6  940.83   282.6  945.21   294.3  953.59
   300.7  957.43   304.7  959.16   311.1  960.78   366.9  970.15     425  973.85
#Mann= 4 ,-1,0
       0      .1       0  182.13    .045       0   234.4      .1       0
   407.5     .05       0
Bank Sta=182.13,234.4
XS Rating Curve= 0 ,0
Exp/Cntr(USF)=0,0
Exp/Cntr=0.3,0.1

Type RM Length L Ch R = 1 ,43501   ,324.1,299.4,269.8
XS GIS Cut Line= 6
1678786.62260951452881.1440762581678721.13980085452939.181033671
1678665.01196034 452988.92699717  1678590.250955453055.340906337
1678536.03780884453107.2472985831678471.87848835453222.119444177
#Sta/Elev= 30
       0 1067.64    15.3 1059.22    19.7  1057.4      27 1055.92    30.2 1054.55
    36.3 1050.67    41.7 1046.18    59.2 1027.41    69.8 1014.93    78.1 1003.82
    85.5  991.21    89.9  986.05   101.3  974.66   119.9  960.45     125  957.47
   133.9  954.33   147.8  947.46   175.7  940.72  188.34933.8791   224.5  932.98
  233.03933.8788   252.7  937.95   267.3  937.22   292.7  937.46   319.5  939.65
     360  939.13   398.6   940.2   428.4  943.21   443.5  944.11   469.1   948.2
#Mann= 4 ,-1,0
       0      .1       0  188.34    .045       0  233.03      .1       0
  407.56     .05       0
Bank Sta=188.34,233.03
XS Rating Curve= 0 ,0
Exp/Cntr(USF)=0,0
Exp/Cntr=0.3,0.1

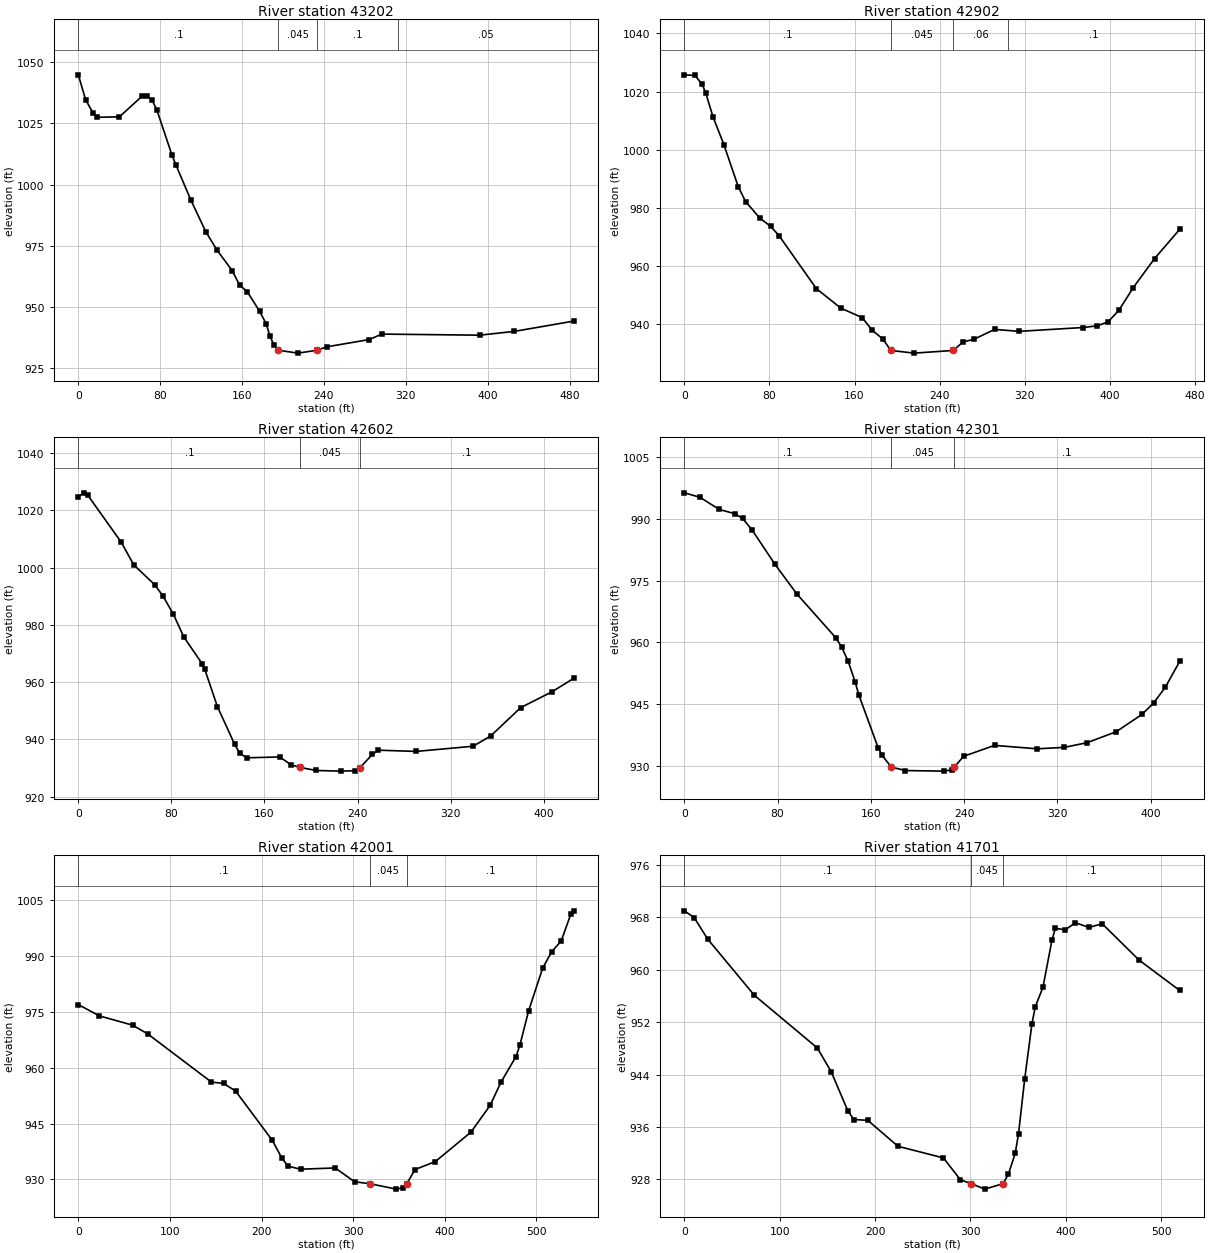
Type RM Length L Ch R = 1 ,43202   ,288.2,300.1,315.9
XS GIS Cut Line= 6
1678271.33492617452756.9855319261678310.61864026452835.171727255
1678344.28983276452902.1883255091678390.38258834452990.942413092
1678429.19222201453068.8316930091678418.45569493453202.911477342
#Sta/Elev= 30
       0 1044.85     7.1 1034.71    14.5 1029.18    18.3 1027.49    40.2  1027.7
    62.3 1036.12    67.2  1036.2    72.1 1034.51    76.9 1030.31    91.6 1011.96
    95.3 1008.11   109.9  993.75   124.6  980.72   135.7  973.15   150.3  964.91
   157.6  958.93     165  956.31   177.1   948.3   183.5   943.2   187.2   938.2
   190.9  934.62  195.31932.3603   214.6  931.17  233.42932.3611   242.8  933.75
   284.3  936.71   296.5  938.95     392   938.5   425.9  940.05     484  944.25
#Mann= 4 ,-1,0
       0      .1       0  195.31    .045       0  233.42      .1       0
  312.51     .05       0
Bank Sta=195.31,233.42
XS Rating Curve= 0 ,0
Exp/Cntr(USF)=0,0
Exp/Cntr=0.3,0.1

Type RM Length L Ch R = 1 ,42902   ,309.1,300.1,281.7
XS GIS Cut Line= 6
1678111.13347493 452881.549587251678133.33388984452967.718050092
1678134.87981851453042.7021520881678138.16983818453142.655692339
  1678145.712474453217.5161069181678173.51060375453340.637641746
#Sta/Elev= 30
       0 1025.76    10.1 1025.53    16.9 1022.45    20.3 1019.36      27 1011.29
    37.2 1001.78    50.7  987.29    57.6  982.18      71  976.48    81.2  973.63
      89  970.48   124.1  952.23   147.1  945.53   167.2  942.26   176.6  937.91
   186.5  934.94   194.1930.9681     216  930.05  252.83930.9684     262  933.93
   271.9  934.77   291.7  938.21   314.7  937.54   374.8  938.86   388.2  939.45
   398.3  940.83   408.4  944.78   421.9  952.58   441.9  962.57   465.5   972.6
#Mann= 4 ,-1,0
       0      .1       0   194.1    .045       0  252.83     .06       0
  303.99      .1       0
Bank Sta=194.1,252.83
XS Rating Curve= 0 ,0
Exp/Cntr(USF)=0,0
Exp/Cntr=0.3,0.1

Type RM Length L Ch R = 1 ,42602   ,292.2,300.5,309.5
XS GIS Cut Line= 6
1677776.24995834453024.7422142621677811.36078051453105.394283921
1677842.66911684453173.8406693341677890.92295735453261.433669999
1677927.74899918453326.769825429  1677970.712824453402.995722845
#Sta/Elev= 30
       0 1024.75     4.8 1026.11     8.3 1025.19      37  1008.8    47.7 1000.93
    65.6  994.05    72.8  990.06    81.8  983.65    90.7  975.77   106.6  966.34
   108.7  964.47   119.5  951.51   134.4  938.26   138.7  935.16   144.8   933.6
   173.1   933.9   182.8  931.15  190.79930.2175   204.5  929.17   225.9  928.95
   237.7  929.09  242.18 930.216   252.8  934.82   257.7  936.26   290.3  935.83
   339.3  937.64   354.3  941.21   380.2  951.13   407.1  956.66   425.7  961.33
#Mann= 3 ,-1,0
       0      .1       0  190.79    .045       0  242.18      .1       0
Bank Sta=190.79,242.18
XS Rating Curve= 0 ,0
Exp/Cntr(USF)=0,0
Exp/Cntr=0.3,0.1

Type RM Length L Ch R = 1 ,42301   ,305.9,300,295.1
XS GIS Cut Line= 6
1677540.49222776453078.2611360851677554.96726443453164.555254832
1677567.37439184  453238.52229851677583.91700967453337.144148499
1677596.32446517453411.1108640881677610.79950184453497.405310929
#Sta/Elev= 30
       0  996.37    13.4  995.29      30  992.32    43.7  991.27      50  990.13
      58  987.41    77.9  978.94    96.5  971.79   129.8  961.17   134.9  958.91
   140.6   955.4   146.7  950.26   149.8  947.16   166.4  934.29   169.7   932.5
  177.63929.6426   189.7   928.8     223  928.66   229.6  929.01  231.71 929.643
   239.6  932.26   266.2  934.92   302.8  934.09   326.1  934.44   345.7  935.59
   370.5  938.24   392.6  942.44   402.7  945.24   412.6  949.03     425  955.34
#Mann= 3 ,-1,0
       0      .1       0  177.63    .045       0  231.71      .1       0
Bank Sta=177.63,231.71
XS Rating Curve= 0 ,0
Exp/Cntr(USF)=0,0
Exp/Cntr=0.3,0.1

Type RM Length L Ch R = 1 ,42001   ,292.6,300,320.8
XS GIS Cut Line= 6
 1677223.9504116453048.9545892771677248.29136859453250.418600172
1677270.45864709453322.2819735111677306.89886293453415.406131089
1677334.22886075453485.249167249 1677366.1139676453566.732928172
#Sta/Elev= 30
       0  976.99      23  973.95    59.3  971.45    75.9  969.08   145.2  956.17
   158.5  955.81   171.7  953.74   211.7  940.51     222   935.8   228.8  933.58
   242.6  932.76   280.4   933.1   301.5  929.38  318.16928.8656   347.2  927.41
   354.8  927.79  358.51 928.865   367.4  932.67   389.6  934.81   428.4   942.7
   449.5  949.93   461.1  956.08   477.7  963.03   481.9  966.12   491.5  975.37
   506.7  986.74   516.4  991.11     527  994.08   537.6 1001.38   540.6 1002.17
#Mann= 3 ,-1,0
       0      .1       0  318.16    .045       0  358.51      .1       0
Bank Sta=318.16,358.51
XS Rating Curve= 0 ,0
Exp/Cntr(USF)=0,0
Exp/Cntr=0.3,0.1

Type RM Length L Ch R = 1 ,41701   ,288.3,286.3,285.9
XS GIS Cut Line= 6
1677113.84157892453019.370594437 1677050.6106616453189.859994262
1677023.91812967453259.9490929251676988.32830584453353.401661918
1676961.63577393453423.490760595  1676930.494432453505.261922508
#Sta/Elev= 30
       0  968.99    10.4  967.96    24.4   964.7    73.4  956.11   139.4  948.07
   153.9  944.47   171.4  938.49   177.7  937.14   192.4  937.02     224  933.06
   271.7  931.28   289.5  927.94  300.99927.3486     315  926.52  334.24927.3492
   339.8  928.82   346.9  931.97   350.4  934.99   356.8  943.26   364.4  951.69
   367.9  954.34     376  957.33   385.5  964.56     389  966.31   399.5  966.11
     410  967.17   424.3  966.46   438.1  967.02   476.7  961.48   519.3  956.84
#Mann= 3 ,-1,0
       0      .1       0  300.99    .045       0  334.24      .1       0
Bank Sta=300.99,334.24
XS Rating Curve= 0 ,0
Exp/Cntr(USF)=0,0
Exp/Cntr=0.3,0.1