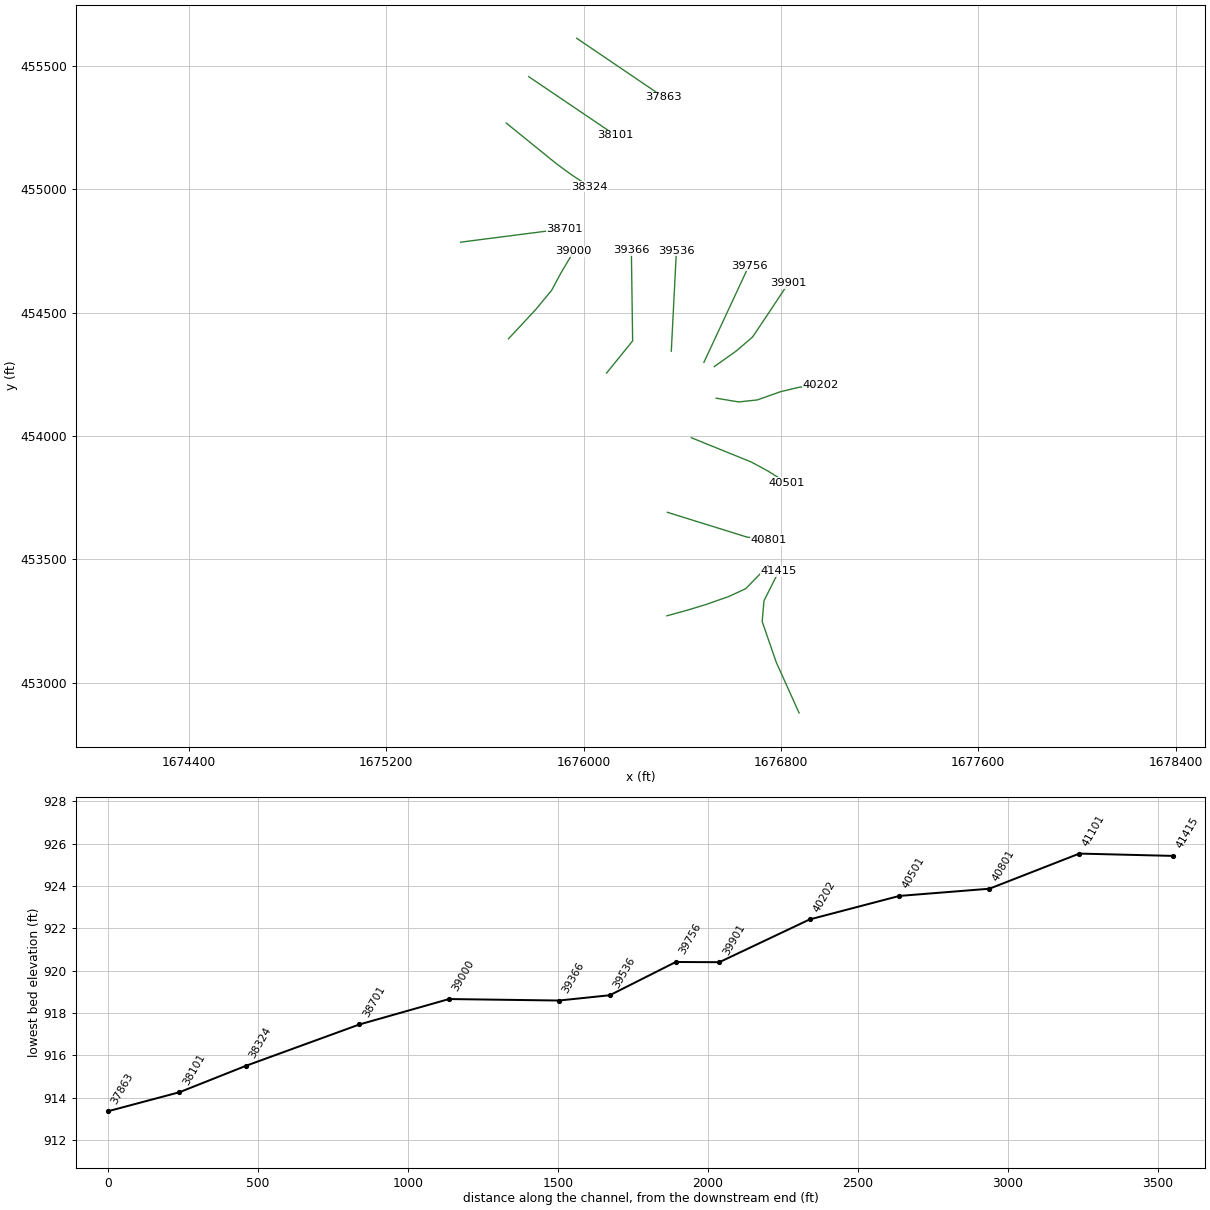
HEC-RAS study PenFrkFshCk.prj: PenFrkFshCk

--- PenFrkFshCk.g01 (geometry) --- (continued)

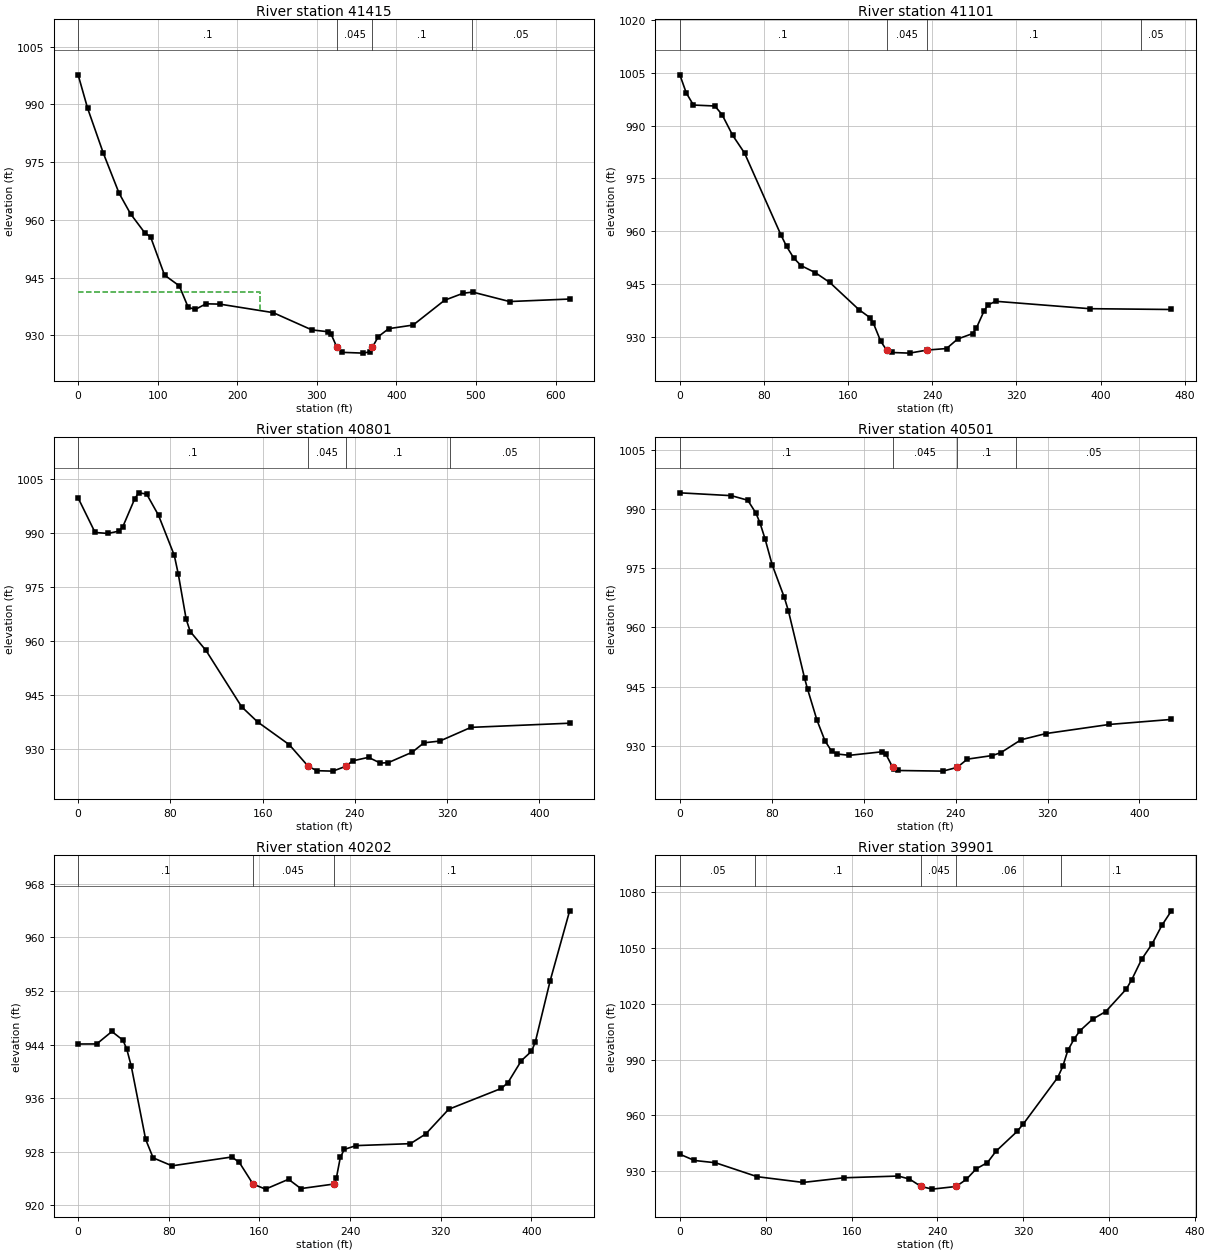
Type RM Length L Ch R = 1 ,41415   ,345.3,313.7,279
XS GIS Cut Line= 6
1676873.90492191452877.2147967871676781.20154992453082.630539168
1676756.75212375453153.5332845051676724.15310759453248.070497011
1676731.54515316453332.1490690011676791.30061109453450.927046676
#Sta/Elev= 30
       0  997.66    11.9     989    31.7  977.31    51.5  966.92    65.9  961.57
    83.8  956.64    91.1  955.58   108.6  945.67   127.1  942.89   138.4  937.27
   147.5  936.79   160.7  938.22   178.1  938.14   245.1  935.93   293.7  931.45
   314.5  930.96   318.1  930.26  325.23926.9316   331.9  925.62   358.6  925.42
   366.6  925.78  369.68926.9325   377.4  929.73   390.3  931.77     421  932.71
   460.5  939.14   483.8  940.96   495.8  941.27   542.2  938.81   617.7  939.46
#Mann= 4 ,-1,0
       0      .1       0  325.23    .045       0  369.68      .1       0
  494.77     .05       0
#XS Ineff= 2 , 0
          228.95  941.23
Permanent Ineff=
       F       F
Bank Sta=325.23,369.68
XS Rating Curve= 0 ,0
Exp/Cntr(USF)=0,0
Exp/Cntr=0.3,0.1

Type RM Length L Ch R = 1 ,41101   ,309.1,300,285.9
XS GIS Cut Line= 6
  1676338.200341453270.9868005071676422.72707485453294.350270838
1676494.54090759453316.1989804211676588.92917025453349.227129593
1676657.32667126453380.8399272561676747.58469284453473.384689674
#Sta/Elev= 30
       0 1004.36     6.1  999.23    12.9   995.8    33.3  995.53    40.1   993.1
    50.3  987.19    61.5  982.21      96  959.09   101.5  955.75   108.3  952.46
   115.2  950.33   128.9  948.31   142.6  945.54   170.2  937.87   180.6  935.62
   184.1  933.96     191  928.89  196.61926.3973   201.5  925.71   218.4  925.53
  235.12926.3984   253.6  926.83   264.1  929.52   278.5  931.08     282  932.65
   289.4  937.56     293  939.15   300.2  940.22   389.6  938.12   467.4  937.89
#Mann= 4 ,-1,0
       0      .1       0  196.61    .045       0  235.12      .1       0
  438.11     .05       0
Bank Sta=196.61,235.12
XS Rating Curve= 0 ,0
Exp/Cntr(USF)=0,0
Exp/Cntr=0.3,0.1

Type RM Length L Ch R = 1 ,40801   ,302.6,300,297.7
XS GIS Cut Line= 6
1676339.84994401453690.4311715961676423.40227035 453664.44565925
1676495.01859692453642.172081754  1676590.506923453612.474306509
1676662.12357767453590.2010570911676749.98331009453578.065582678
#Sta/Elev= 30
       0  999.85    14.7  990.25    25.8  989.97    35.3  990.61    38.8  991.87
    49.1  999.62    52.5 1001.27    59.4 1000.94    69.7  995.03    83.4  983.87
    86.9   978.6    93.7  966.11    97.2   962.7   110.9  957.42   141.8  941.76
   155.6  937.56   183.1  931.22  199.53 925.201   207.1  923.99   220.9  923.87
  232.06   925.2     238  926.72   251.8   927.7   262.1   926.1     269  926.24
   289.6  929.12   299.9  931.75   313.6  932.23   340.6  936.04   426.2   937.2
#Mann= 4 ,-1,0
       0      .1       0  199.53    .045       0  232.06      .1       0
   322.5     .05       0
Bank Sta=199.53,232.06
XS Rating Curve= 0 ,0
Exp/Cntr(USF)=0,0
Exp/Cntr=0.3,0.1

Type RM Length L Ch R = 1 ,40501   ,248.9,299.1,300.6
XS GIS Cut Line= 6
1676436.94784692453992.7612755891676518.03757976453959.886997506
1676587.54301818453931.7092323451676680.21704543453894.138441339
1676746.60470793453858.2707309281676822.90704876453810.756390259
#Sta/Elev= 30
       0  994.16    44.9  993.44    59.1  992.28    66.2  989.02    69.7  986.55
    74.1  982.53    80.3  975.94    90.9  967.62    94.5  964.18   108.6  947.07
   111.1   944.4   119.3   936.5   126.3  931.22     132  928.62     137  927.87
   147.6  927.54   175.9  928.44   179.4  927.79  185.25924.4913   186.5  923.96
     190  923.69     229  923.53  241.45924.4925   250.2  926.57     272  927.49
   279.4  928.22   296.9  931.48   318.7  933.07   373.9  935.38   427.8  936.65
#Mann= 4 ,-1,0
       0      .1       0  185.25    .045       0  241.45      .1       0
   292.5     .05       0
Bank Sta=185.25,241.45
XS Rating Curve= 0 ,0
Exp/Cntr(USF)=0,0
Exp/Cntr=0.3,0.1

Type RM Length L Ch R = 1 ,40202   ,295.4,301.2,309.3
XS GIS Cut Line= 6
1676537.87448233454152.7845775931676629.23256734454137.739332095
1676704.96929251454145.948961332 1676799.2171355454179.421991512
1676872.77505925454196.8671665941676961.56818876454207.811698511
#Sta/Elev= 30
       0  944.09    16.4   944.1    29.8  945.96    39.6  944.66      43  943.29
    46.9  940.79    59.6  929.85    66.2  927.09    82.9   925.9   135.7  927.22
   142.3   926.4   154.4923.1733   165.4  922.42   185.7  923.89   196.6   922.5
  225.55 923.175   227.9  924.06   231.4  927.15   234.9  928.35   245.3  928.92
   293.3  929.21   306.8  930.66     327  934.34   373.5  937.46   379.4  938.34
   391.2  941.61   400.1     943   403.4  944.33   416.6  953.53   433.8  963.98
#Mann= 3 ,-1,0
       0      .1       0   154.4    .045       0  225.55      .1       0
Bank Sta=154.4,225.55
XS Rating Curve= 0 ,0
Exp/Cntr(USF)=0,0
Exp/Cntr=0.3,0.1

Type RM Length L Ch R = 1 ,39901   ,141.3,145.1,145.5
XS GIS Cut Line= 6
1676530.24949759 454281.056630761676618.48160459454343.665429428
 1676684.7646085 454400.314266251676740.59651785454483.279651508
1676782.04197301454545.7877285931676830.39522275454618.713763833
#Sta/Elev= 30
       0  939.17    13.6   935.8    33.2  934.58    72.1  927.08   114.9     924
   152.9   926.5   203.5  927.43   213.9  925.82  224.73921.8204   235.1   920.4
  257.39921.8215   266.8  925.62   276.2  931.36   286.5  934.64   294.5  940.77
   314.1  951.38   319.9  955.39     352   980.4   356.7  986.33   361.4  994.93
   367.4 1001.24   372.8 1005.57   384.5 1011.76   396.8 1015.88   415.9 1027.96
   420.9  1032.9   430.1 1043.86   440.1 1052.37     449 1062.14   457.9 1070.01
#Mann= 5 ,-1,0
       0     .05       0      70      .1       0  224.73    .045       0
  257.39     .06       0  355.38      .1       0
Bank Sta=224.73,257.39
XS Rating Curve= 0 ,0
Exp/Cntr(USF)=0,0
Exp/Cntr=0.3,0.1

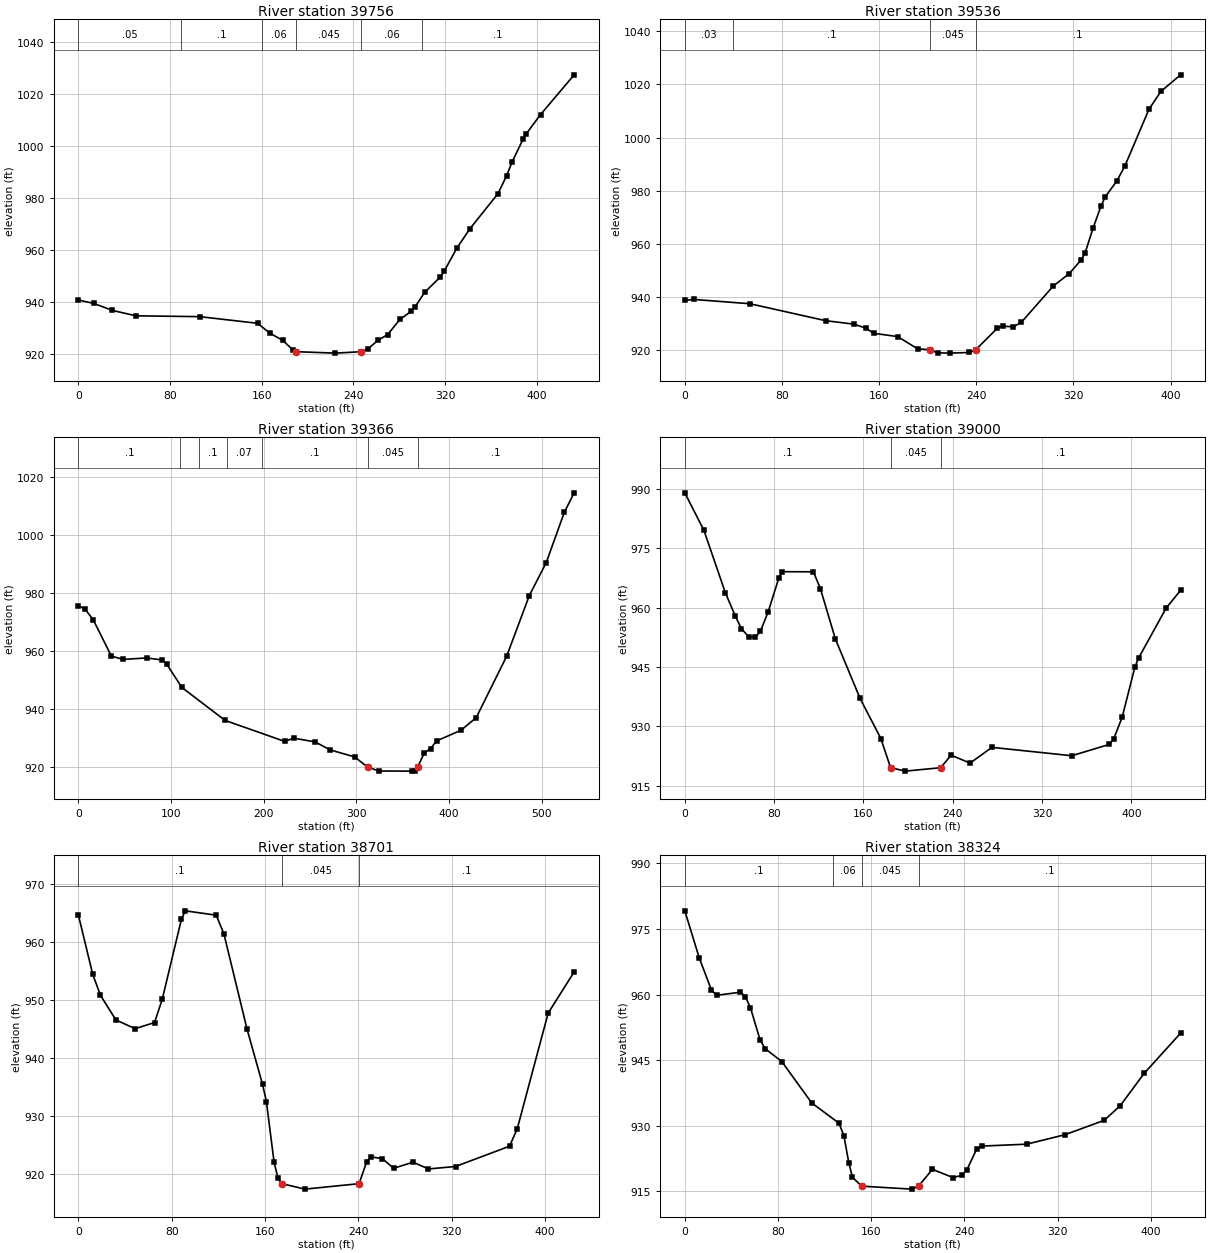
Type RM Length L Ch R = 1 ,39756   ,216.5,220,233.1
XS GIS Cut Line= 2
1676488.01794957454297.9761544281676670.69128597454690.194742515
#Sta/Elev= 30
       0  940.82    13.3  939.55    29.8  936.83    50.3  934.76   105.8  934.44
   156.4  931.89   167.4     928   178.2  925.39   187.4   921.6  189.95920.9656
   224.4  920.41  246.96920.9662   252.8  922.08   261.5  925.34     270  927.57
   280.7  933.41   290.4  936.45     294  938.28   302.1  943.73   315.8  949.65
   319.4  952.01   330.2  960.71   341.7  968.23   366.2  981.74   373.7  988.59
   378.7   994.1   388.1 1002.69     391 1004.83   403.4 1012.19   432.7 1027.45
#Mann= 6 ,-1,0
       0     .05       0      90      .1       0     160     .06       0
  189.95    .045       0  246.96     .06       0     300      .1       0
Bank Sta=189.95,246.96
XS Rating Curve= 0 ,0
Exp/Cntr(USF)=0,0
Exp/Cntr=0.3,0.1

Type RM Length L Ch R = 1 ,39536   ,169.8,169.6,171.7
XS GIS Cut Line= 2
1676355.83349809454343.572389193  1676376.597341454751.298759101
#Sta/Elev= 30
       0  938.72     7.7  939.04    53.7  937.43   116.1  931.04   139.1  929.77
     149  928.26   155.5  926.31   175.3  925.07   191.7  920.46  201.52920.1252
   208.1  918.95     218  918.84   234.4  919.08  239.61920.1241   257.4  928.24
   261.8  928.97   270.5  928.76   277.1  930.42   303.4  944.08   316.5  948.75
   326.4  953.94   329.6  956.53   336.2  965.92   342.8  974.25   346.1  977.59
   355.9  983.75   362.5   989.4   382.2 1010.62   392.1 1017.39   408.3 1023.61
#Mann= 4 ,-1,0
       0     .03       0      40      .1       0  201.52    .045       0
  239.61      .1       0
Bank Sta=201.52,239.61
XS Rating Curve= 0 ,0
Exp/Cntr(USF)=0,0
Exp/Cntr=0.3,0.1

Type RM Length L Ch R = 1 ,39366   ,384.9,366.3,353.8
XS GIS Cut Line= 3
1676093.47103711454254.6169595211676199.16086521454385.100075017
1676193.94986324 454752.22909692
#Sta/Elev= 30
       0  975.58     7.2  974.37      16  970.76    35.7  958.17    48.6  957.06
    73.7  957.56    90.6  956.87    95.3  955.48   111.7  947.41   158.4  936.05
   222.7  928.82   232.5  929.94   255.5  928.65   271.9  925.89   298.1  923.49
  312.27919.9775   324.4  918.64   360.5  918.59   363.8  918.78  366.15919.9764
   373.4  924.84   380.2  926.37   386.7  929.01     413  932.66   429.4  937.01
   462.2  958.11   486.7  979.04   504.9  990.34   524.5 1007.72   535.1 1014.42
#Mann= 7 ,-1,0
       0      .1       0     110     .07       0     130      .1       0
     160     .07       0  197.92      .1       0  312.27    .045       0
  366.15      .1       0
Bank Sta=312.27,366.15
XS Rating Curve= 0 ,0
Exp/Cntr(USF)=0,0
Exp/Cntr=0.3,0.1

Type RM Length L Ch R = 1 ,39000   ,322.4,298.7,282.4
XS GIS Cut Line= 6
1675695.87747867  454393.68140551675755.67329083454457.524781749
1675806.55606309 454512.61292617 1675870.7111185454589.853585333
1675908.26550534 454659.788812921675960.17944351454747.354582667
#Sta/Elev= 30
       0  989.03    17.1  979.57    36.3  963.79    45.3  957.82    50.7  954.69
    57.2  952.63    63.3  952.51    67.8  954.06    74.7  958.95    84.3  967.58
    87.4  969.09   115.2  969.06   121.5  964.77   134.9  952.05     157  937.04
   175.6  926.91  184.31919.5329   197.6  918.66  229.26919.5325   238.5  922.69
   255.5  920.69   275.1  924.67   346.6  922.55   380.3  925.42   384.1  926.79
   391.7  932.25   403.1  944.94   406.4  947.23   431.2  959.92   444.1  964.39
#Mann= 3 ,-1,0
       0      .1       0  184.31    .045       0  229.26      .1       0
Bank Sta=184.31,229.26
XS Rating Curve= 0 ,0
Exp/Cntr(USF)=0,0
Exp/Cntr=0.3,0.1

Type RM Length L Ch R = 1 ,38701   ,401.9,377.8,354.4
XS GIS Cut Line= 6
1675501.78042592454785.099913999 1675588.5660135454796.258028179
1675662.95366001454805.8219854241675762.13718867454818.573928416
1675836.52483517454828.1378856751675923.31042276454839.295671761
#Sta/Elev= 30
       0  964.76    12.3  954.51      19  950.86    32.2  946.63    48.7  945.12
    65.3  946.18    71.9  950.16    88.4  964.02    91.7  965.44   118.2  964.69
   124.8  961.45   144.6  945.05   157.9  935.52   161.2  932.56   167.8  922.08
   171.1  919.37  174.44918.4031   194.3  917.46  240.64 918.401   247.2  922.19
   250.5  923.03   260.4  922.74   270.3  921.05   286.9  922.11   300.1  920.94
   323.3  921.36   369.6  924.86   376.2  927.85   402.7   947.8     425  954.91
#Mann= 3 ,-1,0
       0      .1       0  174.44    .045       0  240.64      .1       0
Bank Sta=174.44,240.64
XS Rating Curve= 0 ,0
Exp/Cntr(USF)=0,0
Exp/Cntr=0.3,0.1

Type RM Length L Ch R = 1 ,38324   ,220.1,222.2,225
XS GIS Cut Line= 6
1675686.84347832455267.8906769941675754.80954973455212.783175666
1675813.06632298455165.5480339121675890.74202065455102.567844916
1675951.35869732455058.2434584981676024.88512507455009.993226919
#Sta/Elev= 30
       0  979.15    12.4  968.39    22.9  961.01    27.3  959.84    47.8  960.54
      52  959.52    56.3  957.02    64.6  949.64    68.9  947.64    83.3  944.67
   108.9  935.23   132.3  930.59   136.5  927.76   140.7  921.59   143.9  918.21
  151.72 916.188   194.8  915.51  200.59 916.187   212.5  920.04   230.2  918.15
   237.9  918.69   242.1  919.93   250.6  924.75   254.8  925.35   293.4  925.79
   326.3  927.96   359.9  931.24   373.6  934.56   394.3  942.01   425.5  951.18
#Mann= 4 ,-1,0
       0      .1       0   127.5     .06       0  151.72    .045       0
  200.59      .1       0
Bank Sta=151.72,200.59
XS Rating Curve= 0 ,0
Exp/Cntr(USF)=0,0
Exp/Cntr=0.3,0.1

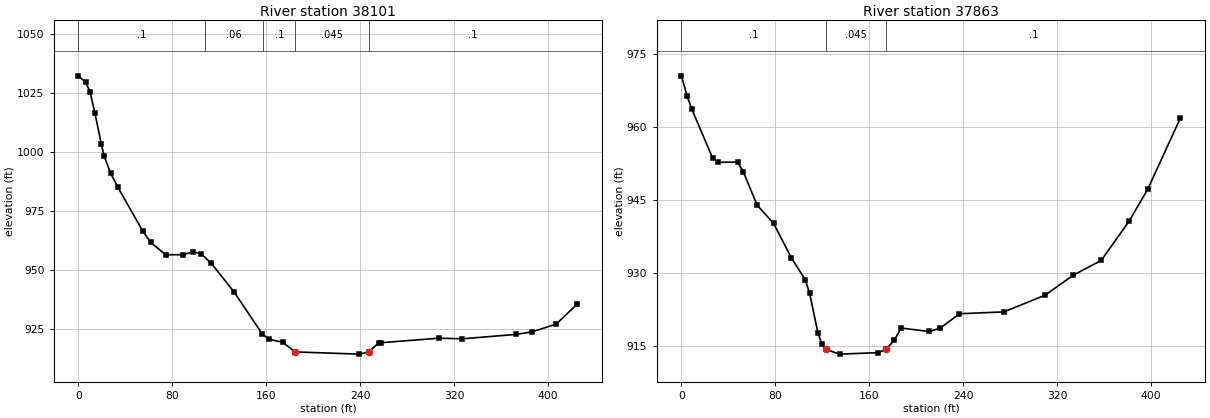
Type RM Length L Ch R = 1 ,38101   ,238.5,238.7,238.1
XS GIS Cut Line= 6
1675777.99411234455455.8147799221675850.48281251455406.808316261
1675912.61589034455364.8028228431675995.46021284455308.795060843
1676057.59329067455266.7895674261676130.08199084455217.783103749
#Sta/Elev= 30
       0  1032.3     6.1 1029.48     9.8 1025.63      14  1016.5    19.4 1003.39
    21.9  998.17    27.3  991.08    33.6  984.95    54.8  966.39    61.5  961.65
    74.2  956.41    89.3  956.41    97.6  957.69   104.5  956.77     113  952.85
   132.8  940.43   156.4  922.88   162.1   920.6   173.8   919.3  184.63915.1923
   239.1  914.26  247.05 915.191   255.6  918.96     258  919.12   307.1  921.02
   326.9  920.76   372.9  922.64   386.3  923.71   406.9  926.99     425  935.61
#Mann= 5 ,-1,0
       0      .1       0   107.5     .06       0   157.5      .1       0
  184.63    .045       0  247.05      .1       0
Bank Sta=184.63,247.05
XS Rating Curve= 0 ,0
Exp/Cntr(USF)=0,0
Exp/Cntr=0.3,0.1

Type RM Length L Ch R = 1 ,37863   ,368.8,361.3,352.9
XS GIS Cut Line= 6
1675972.68264558455611.2192439481676045.10704143455562.117964198
1676107.18532934455520.0311061041676189.95583309455463.915076603
  1676252.034121455421.8278904451676324.45851684455372.726610695
#Sta/Elev= 30
       0  970.49     4.7  966.41     8.7  963.72    26.5  953.62    31.3  952.74
    47.8  952.78    52.8  950.72    64.5  943.92    78.5  940.19    93.7  933.08
   105.4  928.66   109.2  925.81   116.3  917.63   119.7  915.41  122.96914.3318
   134.7  913.36   167.3  913.66  174.35914.3316   181.4   916.3   187.2  918.71
   210.9  918.01   220.2  918.66   236.8  921.65   274.6  922.03   309.7  925.46
   333.7  929.56   357.5  932.59   381.3  940.67   397.2  947.25     425  961.86
#Mann= 3 ,-1,0
       0      .1       0  122.96    .045       0  174.35      .1       0
Bank Sta=122.96,174.35
XS Rating Curve= 0 ,0
Exp/Cntr(USF)=0,0
Exp/Cntr=0.3,0.1