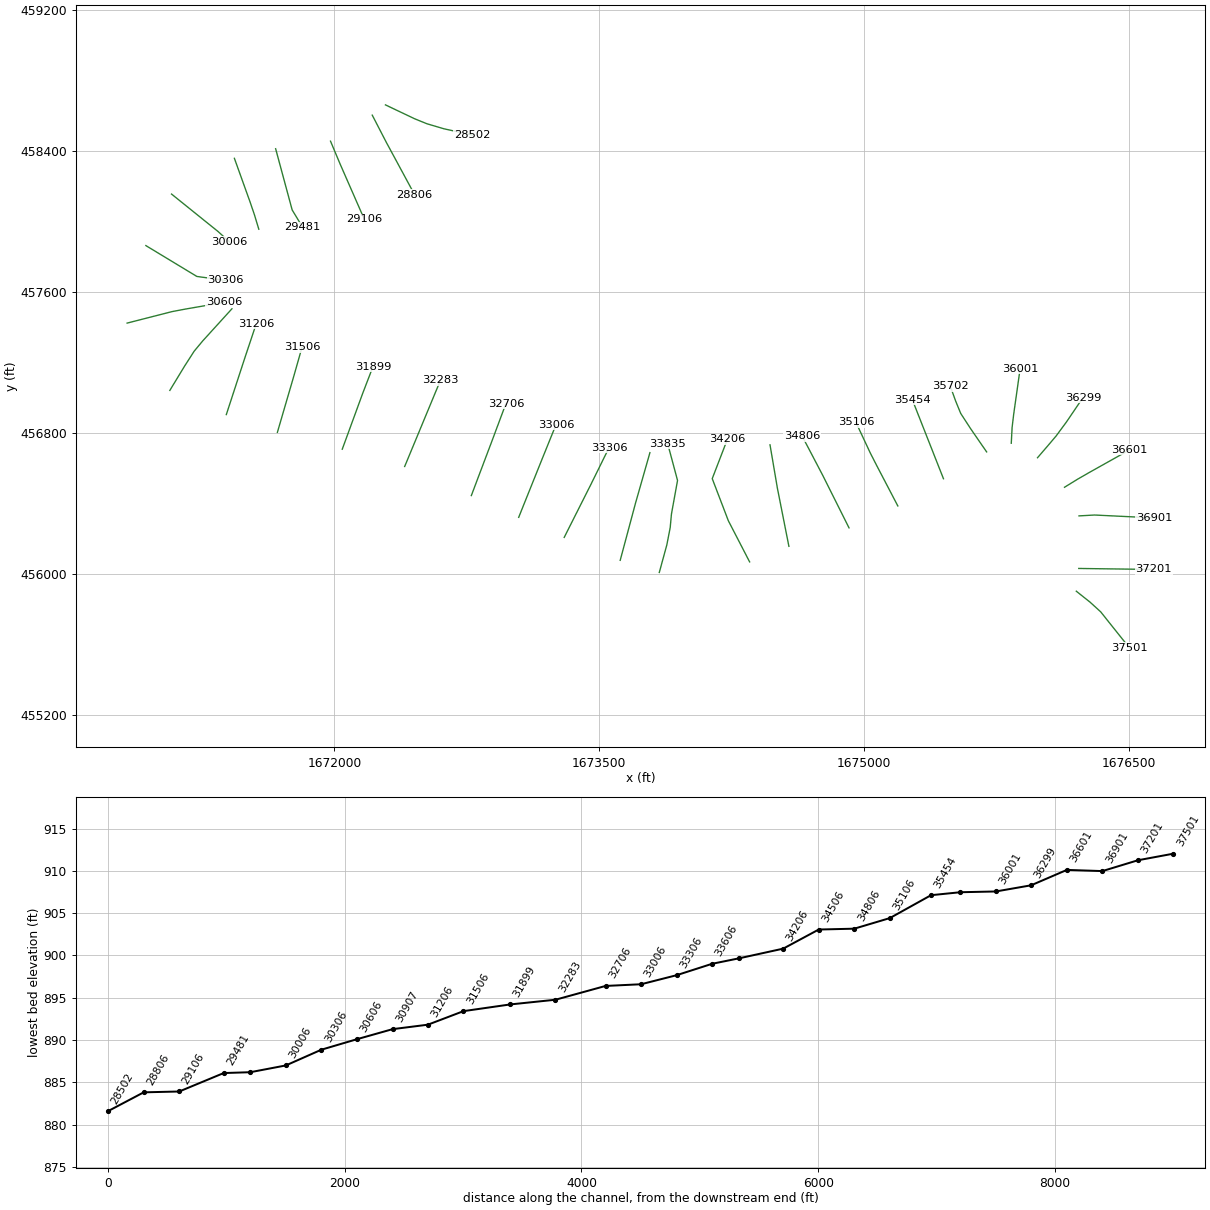
HEC-RAS study PenFrkFshCk.prj: PenFrkFshCk

--- PenFrkFshCk.g01 (geometry) --- (continued)

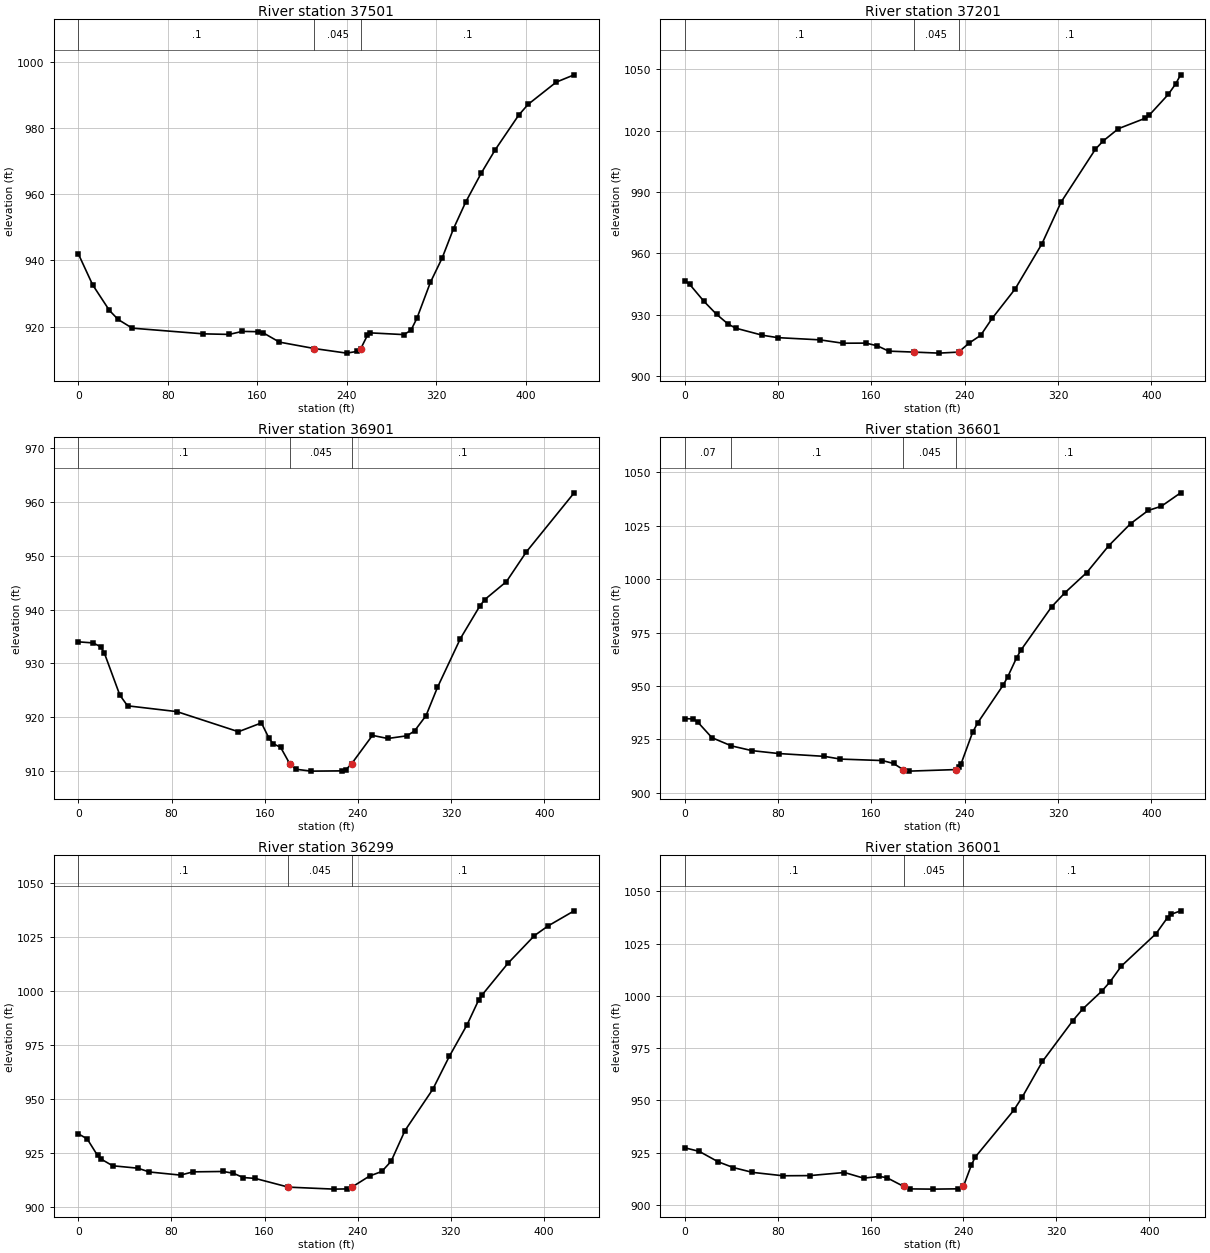
Type RM Length L Ch R = 1 ,37501   ,281.2,300,317.2
XS GIS Cut Line= 6
1676201.39155951455901.2492565071676280.08201893455838.440983176
1676339.34043059 455784.297390671676401.63361309 455706.06920068
1676448.35267976455647.3980581761676502.85847625455578.948391929
#Sta/Elev= 30
       0     942    12.8  932.65    27.8  924.92    35.6  922.19    48.2  919.57
   111.8  917.85     135  917.68   146.6  918.59   160.6   918.5   165.2  918.19
   179.9  915.35  211.22 913.409   239.9  912.03   249.2  912.54  252.66913.4062
   258.5  917.36   260.9  918.15   291.2  917.62   297.5  918.92   302.9  922.59
   314.9  933.39   325.5   940.8   335.6  949.62   346.5  957.64   360.4  966.38
   372.9  973.43   393.9  983.88   402.3  987.13   427.5  993.85   443.5  996.05
#Mann= 3 ,-1,0
       0      .1       0  211.22    .045       0  252.66      .1       0
Bank Sta=211.22,252.66
XS Rating Curve= 0 ,0
Exp/Cntr(USF)=0,0
Exp/Cntr=0.3,0.1

Type RM Length L Ch R = 1 ,37201   ,301.7,300,299.2
XS GIS Cut Line= 6
  1676215.169091456030.318224087  1676302.661042456029.135483667
1676377.65433034456028.1220342521676477.64527209456026.770987093
1676552.63856043456025.7572095841676640.13051142456024.575125337
#Sta/Elev= 30
       0  946.73     4.2  944.84    16.4  936.57    27.2  930.23      37  925.52
    43.6  923.46    66.6  919.98    79.7  918.82   115.8  917.74   135.5  916.09
   155.2  916.15     165  914.83   174.8  912.22  196.26911.7598   217.9  911.25
  234.71911.7609   243.7  916.16   253.6  919.94   263.4   928.2   283.1  942.57
   306.1  964.64   322.5  985.03     352 1010.94   358.6 1014.93   371.7 1020.95
   394.7 1026.05     398 1027.49   414.4 1037.68   420.8 1042.88     425 1047.26
#Mann= 3 ,-1,0
       0      .1       0  196.26    .045       0  234.71      .1       0
Bank Sta=196.26,234.71
XS Rating Curve= 0 ,0
Exp/Cntr(USF)=0,0
Exp/Cntr=0.3,0.1

Type RM Length L Ch R = 1 ,36901   ,281.7,300,311.3
XS GIS Cut Line= 6
1676216.66121401456328.4629690051676304.50322993456333.385531336
1676379.41515359456329.7490556691676479.29749976456324.900312096
1676554.20909534456321.2638364291676641.60623026 456317.02139084
#Sta/Elev= 30
       0  934.02    12.6  933.82    19.2   933.1    22.4  931.89    35.6  924.12
    42.2  922.12    84.6  921.04   137.4   917.3   157.1  918.94   163.7  916.06
     167   915.1   173.6  914.39  181.37911.3676   186.7  910.32   199.8  909.97
   226.1  910.02   229.4  910.18  234.61911.3668   252.4  916.62   265.5  916.04
     282  916.54   288.5  917.44   298.4   920.3   308.2  925.55   327.9  934.64
   344.4  940.63   348.6  941.85   367.4  945.23   384.5  950.76   425.5  961.74
#Mann= 3 ,-1,0
       0      .1       0  181.37    .045       0  234.61      .1       0
Bank Sta=181.37,234.61
XS Rating Curve= 0 ,0
Exp/Cntr(USF)=0,0
Exp/Cntr=0.3,0.1

Type RM Length L Ch R = 1 ,36601   ,289.3,301.9,310.4
XS GIS Cut Line= 6
1676134.38447568456490.7677625121676208.93353917456536.717145666
1676273.92520709456574.1573595111676361.11728993456623.121828511
1676426.51151609456659.8455083371676502.80467059 456702.68958275
#Sta/Elev= 30
       0  934.71     7.4  934.54    11.2  933.01    23.3  925.75      40  921.93
    57.5  919.71    80.6  918.34   119.6  917.03   133.4  915.75   169.4  915.06
     179  913.69  187.09910.8426   192.4  910.11  232.78910.8422   235.5  912.07
   236.9  913.59   246.8  928.35   251.3  932.86     273  950.41   276.9  954.32
   284.4  963.11   288.2  966.79   314.5  987.05     326  993.69   344.6 1003.08
   363.4 1015.62   382.2 1025.99   397.3 1032.16   408.6 1034.14   425.1 1040.42
#Mann= 4 ,-1,0
       0     .07       0      40      .1       0  187.09    .045       0
  232.78      .1       0
Bank Sta=187.09,232.78
XS Rating Curve= 0 ,0
Exp/Cntr(USF)=0,0
Exp/Cntr=0.3,0.1

Type RM Length L Ch R = 1 ,36299   ,283.7,298.1,309.7
XS GIS Cut Line= 6
1675981.69252384456658.3045009231676039.15271075456725.074708596
1676087.85996242 456782.674330921676147.07605134456863.348054096
1676189.09926125456925.4693209231676238.12606609456997.944241583
#Sta/Elev= 30
       0  933.92     7.6  931.56    16.5   923.9    19.2  922.32    29.5  919.11
    51.1  917.99    61.1  916.23    87.8  914.79    98.6  916.29   124.4  916.47
   133.2  915.65   141.6  913.66   151.9  913.26  180.52909.2122   219.8  908.29
   230.6  908.39  235.05909.2106   250.3  914.36   260.8  916.47   268.8  921.19
   280.7  935.41   304.6  954.53   318.8  969.77   334.1  984.46     344  995.86
   347.1  998.32   369.2  1012.9     392 1025.75   403.8 1030.25   426.1 1037.21
#Mann= 3 ,-1,0
       0      .1       0  180.52    .045       0  235.05      .1       0
Bank Sta=180.52,235.05
XS Rating Curve= 0 ,0
Exp/Cntr(USF)=0,0
Exp/Cntr=0.3,0.1

Type RM Length L Ch R = 1 ,36001   ,278.8,299.3,321.1
XS GIS Cut Line= 6
1675833.03829359456740.4883916681675837.78959642 456829.82876417
1675846.67540543456904.3177884221675860.63896017457003.337931588
1675871.11203635457077.6032029991675883.33051585457164.246074334
#Sta/Elev= 30
       0  927.32    12.4  925.62    28.8  920.61    41.9  917.85    58.3  915.57
    84.6  913.95   107.7  914.03   137.5  915.51     154  912.81   167.2  913.61
   173.8  913.09  188.42 908.872   193.7  907.67   213.6  907.56   235.4   907.7
  239.93908.8699   246.7  918.91     250   922.8   283.2   945.2   290.6  951.56
     308  968.62   334.1  988.08   342.8  993.76   359.4  1002.4   366.1 1006.62
   375.9 1014.18   405.8  1029.7   415.7  1037.4     419 1039.01     427 1040.64
#Mann= 3 ,-1,0
       0      .1       0  188.42    .045       0  239.93      .1       0
Bank Sta=188.42,239.93
XS Rating Curve= 0 ,0
Exp/Cntr(USF)=0,0
Exp/Cntr=0.3,0.1

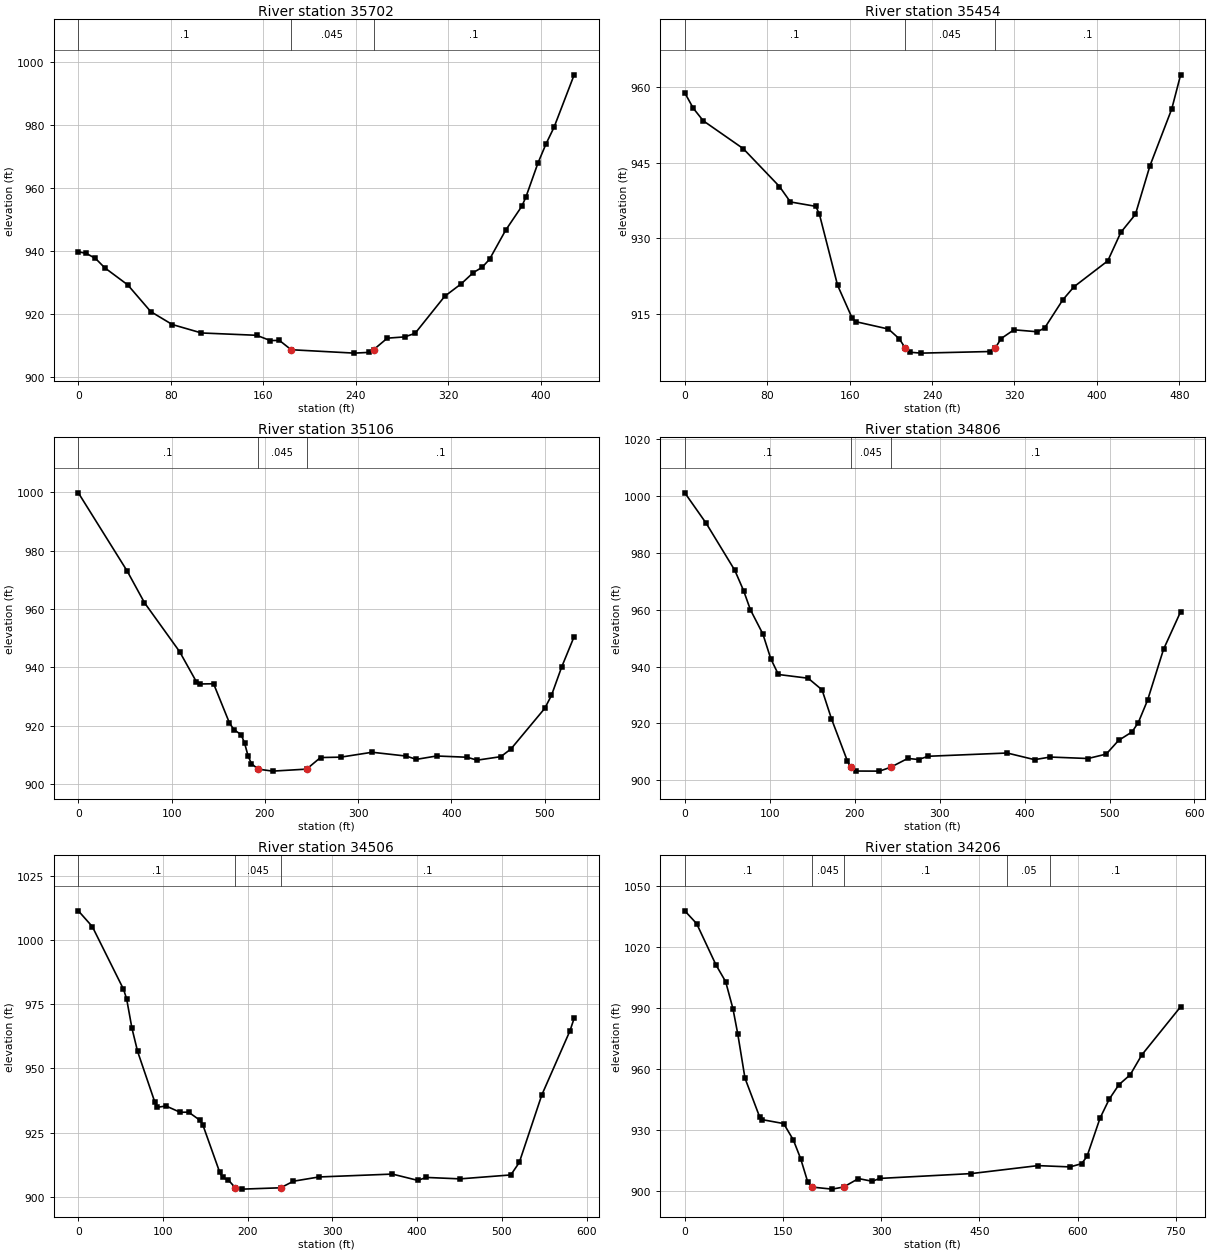
Type RM Length L Ch R = 1 ,35702   ,252.8,247.7,233.1
XS GIS Cut Line= 6
1675693.54546234456691.4199202511675643.82508934456763.463739425
1675601.41933426456825.3527232561675546.98899692456909.241663083
1675518.07862167 456979.890471921675487.61345951 457064.43295376
#Sta/Elev= 30
       0  939.69     6.8  939.19    14.8  937.59    22.8  934.62    42.7  929.18
    62.6  920.68    81.2  916.57   106.5  913.88   154.2  913.14     166  911.47
   173.9  911.51  184.06908.5495   238.7  907.47   251.6  907.71  255.31908.5506
   267.2  912.23   282.2  912.63   291.2  913.75   316.9  925.56   331.1   929.5
   341.6  933.08   349.2  934.75   355.6   937.3   369.5  946.52   383.5  954.15
     387  957.02   397.4  967.82   404.4  973.95   411.4  979.28   428.8  995.96
#Mann= 3 ,-1,0
       0      .1       0  184.06    .045       0  255.31      .1       0
Bank Sta=184.06,255.31
XS Rating Curve= 0 ,0
Exp/Cntr(USF)=0,0
Exp/Cntr=0.3,0.1

Type RM Length L Ch R = 1 ,35454   ,340.9,348.4,356.7
XS GIS Cut Line= 2
  1675449.123617456539.3432250471675272.88021946456987.245742219
#Sta/Elev= 30
       0  958.89     8.3  955.82    17.9  953.35    56.7  947.81    91.9  940.27
   102.5   937.2   127.2  936.32   130.7  934.73   148.3  920.62   162.4  914.11
   165.9  913.38   197.7  911.91   208.3  909.95   213.9  908.15   218.3   907.3
   229.4  907.12   296.4  907.44   301.4  908.14     307  910.01   319.5  911.76
   342.2  911.37   349.3  912.12   366.9  917.71   377.7  920.31   410.6  925.48
   423.3  931.16   437.4  934.72   451.5  944.38   472.7  955.71   481.3  962.49
#Mann= 3 ,-1,0
       0      .1       0   213.9    .045       0   301.4      .1       0
Bank Sta=213.9,301.4
XS Rating Curve= 0 ,0
Exp/Cntr(USF)=0,0
Exp/Cntr=0.3,0.1

Type RM Length L Ch R = 1 ,35106   ,300.3,300,299.2
XS GIS Cut Line= 6
1675190.70919767456384.8650871661675150.23519726456462.441375583
1675115.54268134456528.9353370821675069.28621218456617.593952417
1675035.21672651456684.4127164191674953.00835852456860.119932069
#Sta/Elev= 30
       0  999.81    52.4  972.97    70.9  962.14   108.5   945.4   126.4  935.13
   130.1  934.28     145  934.36     162  920.91   166.8  918.63   174.5  916.91
   178.2  914.05   181.9  909.66   185.6  906.96  192.74905.0956   208.2  904.41
  244.68905.0966   259.6  909.07   281.2   909.2   314.9  910.88   351.5  909.57
   362.3  908.44   384.1   909.6   416.7  909.17   427.5  908.17   452.9  909.37
   463.7  911.99     500  925.93   507.2   930.4   518.1  940.09   531.5  950.54
#Mann= 3 ,-1,0
       0      .1       0  192.74    .045       0  244.68      .1       0
Bank Sta=192.74,244.68
XS Rating Curve= 0 ,0
Exp/Cntr(USF)=0,0
Exp/Cntr=0.3,0.1

Type RM Length L Ch R = 1 ,34806   ,305.6,300,292.2
XS GIS Cut Line= 6
1674914.44006518456260.5579210821674875.30858175456338.820231751
1674841.76731026456405.9021185931674797.04561493456495.344525009
1674763.50434342456562.4264118371674649.22525944456780.551562052
#Sta/Elev= 30
       0 1001.17    25.2  990.43    58.9  973.86    69.2  966.74    77.2  960.01
    91.9  951.47   101.2  942.75   110.2  937.19   145.2  935.88   161.6  931.78
   172.6  921.64   191.4  906.73  195.39904.5047   201.9  903.19   229.2  903.16
  242.19904.5038   262.5  907.63   275.3  907.25   286.3  908.39   379.5  909.54
   411.7   907.2   430.2  908.12   474.7   907.6   496.1  909.16   510.7  913.99
   526.5  916.97   533.9  920.27   544.8  928.15   563.6  946.08   583.7   959.3
#Mann= 3 ,-1,0
       0      .1       0  195.39    .045       0  242.19      .1       0
Bank Sta=195.39,242.19
XS Rating Curve= 0 ,0
Exp/Cntr(USF)=0,0
Exp/Cntr=0.3,0.1

Type RM Length L Ch R = 1 ,34506   ,293.1,300,307.6
XS GIS Cut Line= 6
1674573.96699284456155.9186946751674557.01099001456241.760058418
1674542.47689834456315.3379952611674523.09832817 456413.44245784
1674508.56456459456487.020722762 1674467.0691466456731.422341469
#Sta/Elev= 30
       0  1011.3    16.5 1005.17    53.3  980.82      57   977.1    63.3  965.64
      70  956.59    90.1  937.11    93.4  934.89   103.5   935.4   120.2  932.95
   130.2     933   143.6  929.84   146.9  928.14     167  909.54   170.3  907.59
   177.1  906.61  185.33 903.582   193.7  903.06  238.87903.5819     254  906.14
   284.1  907.79   370.8  908.91   400.8  906.46   410.8  907.61   450.7  907.05
   510.6  908.58   520.6  913.42   547.2  939.69   580.5  964.67   585.4  969.54
#Mann= 3 ,-1,0
       0      .1       0  185.33    .045       0  238.87      .1       0
Bank Sta=185.33,238.87
XS Rating Curve= 0 ,0
Exp/Cntr(USF)=0,0
Exp/Cntr=0.3,0.1

Type RM Length L Ch R = 1 ,34206   ,385.6,371.3,355
XS GIS Cut Line= 6
1674351.62787059456067.4543046651674311.49671726456145.208742335
1674277.09849209456211.8552625921674231.23441058456300.717289582
1674139.93505875456539.726301549 1674225.6922334456762.771892851
#Sta/Elev= 30
       0 1037.66    18.1 1031.36    47.7 1011.02    62.4 1002.83    73.5  989.58
    80.9  977.12    91.9  955.39   114.1  936.48   117.8  934.99     151  933.04
   165.8  924.97   176.9  915.82   187.9  904.19  193.74901.8269   224.9   900.8
  242.48 901.828   265.3  905.99   286.4  904.65   297.6  906.06   437.5  908.44
   539.3  912.36   588.5  911.73   606.1  913.31   614.3  916.89   634.2  935.69
   648.2  945.01     663  952.14   680.3  957.03     698   966.8   757.3  990.48
#Mann= 5 ,-1,0
       0      .1       0  193.74    .045       0  242.48      .1       0
   492.5     .05       0  558.35      .1       0
Bank Sta=193.74,242.48
XS Rating Curve= 0 ,0
Exp/Cntr(USF)=0,0
Exp/Cntr=0.3,0.1

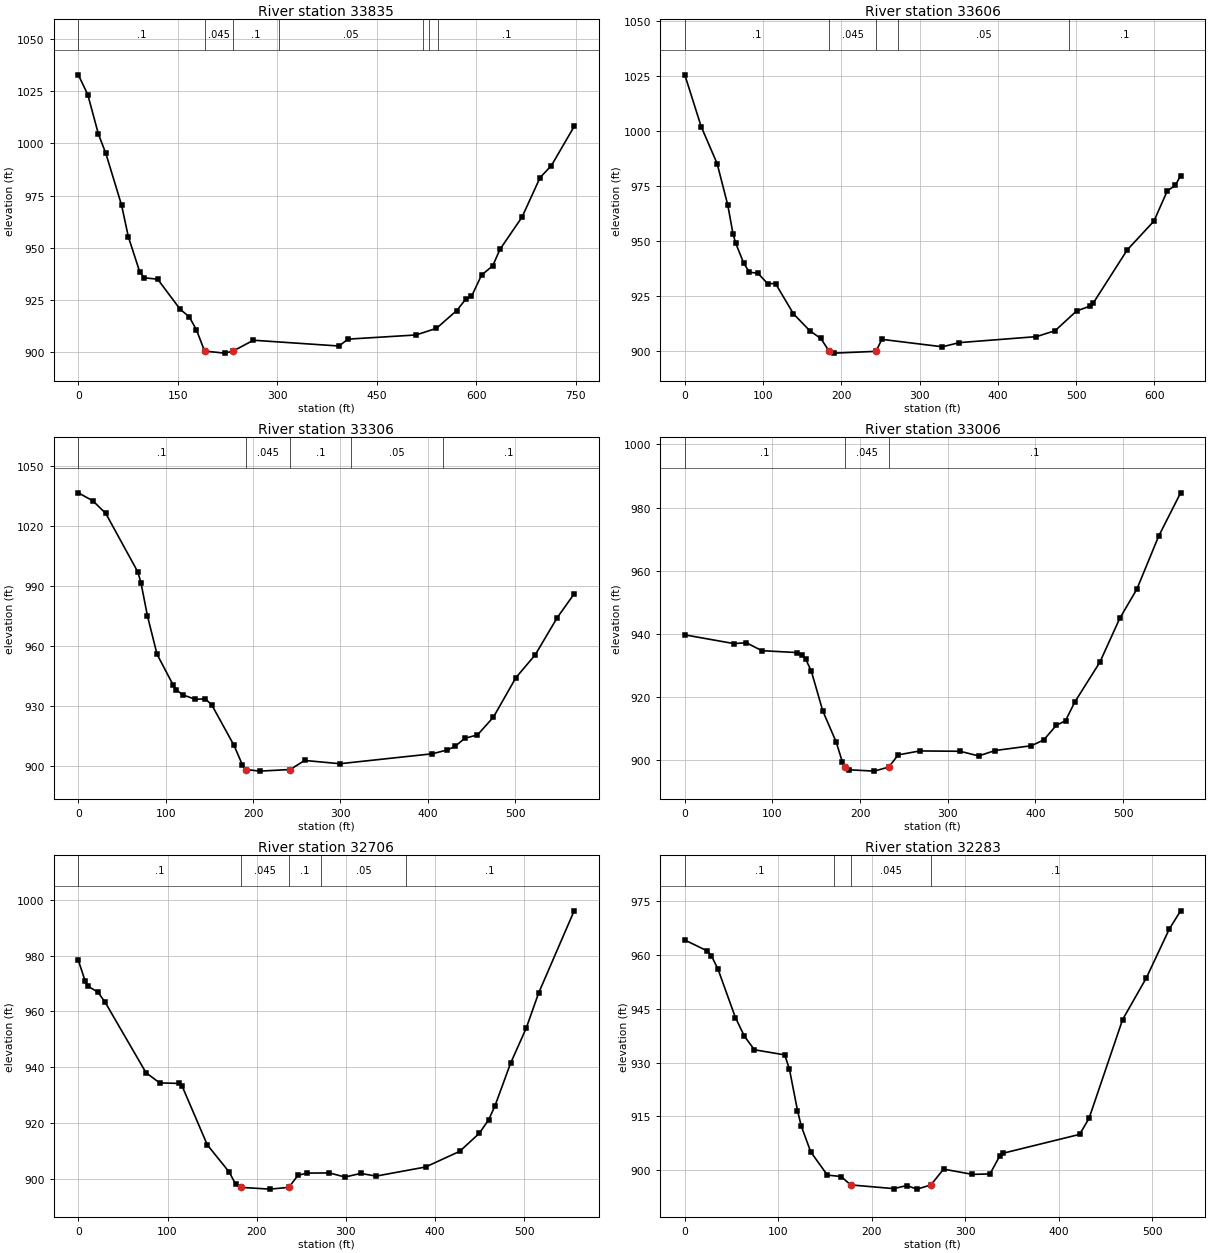
Type RM Length L Ch R = 1 ,33835   ,230.5,228.7,228.6
XS GIS Cut Line= 6
1673840.14925886456007.5434616731673882.90540694456164.317426331
1673902.02643169456262.7552215831673908.92438377456338.613009505
1673943.45247614456529.4387611971673887.97388293456736.870517765
#Sta/Elev= 30
       0 1032.83    14.2 1023.38    30.4 1004.32    41.4   995.3    65.2  970.47
    75.4  955.35    92.4  938.69    99.2  935.71   119.6  935.04   153.6  920.61
   167.1  917.09     178  910.87  190.37 900.639   220.6  899.66  233.31900.6401
     264  905.83   393.1  903.06   406.5  906.35   509.2  908.35     540  911.53
   570.5  920.04   584.1  925.42   592.8  926.77   607.9  936.98   624.9  941.47
   635.7  949.31     669  964.75   696.2  983.66   713.2  989.36   747.6 1008.11
#Mann= 7 ,-1,0
       0      .1       0  190.37    .045       0  233.31      .1       0
  302.78     .05       0  518.95      .1       0  528.95     .05       0
  542.87      .1       0
Bank Sta=190.37,233.31
XS Rating Curve= 0 ,0
Exp/Cntr(USF)=0,0
Exp/Cntr=0.3,0.1

Type RM Length L Ch R = 1 ,33606   ,305.3,300,293.5
XS GIS Cut Line= 6
1673618.82224959456076.4769244191673660.78870109456233.464143261
1673686.61476493456330.0718896691673705.98382068456402.527781501
1673720.71307036456453.9338778811673787.09750099456687.147377377
#Sta/Elev= 30
       0 1025.71    20.9 1002.17    41.3   985.3    54.9  966.43    61.6  953.29
      65  949.12    75.2  940.02    82.6  935.84    93.3   935.4   105.8  930.67
     116  930.65   138.8  916.91   160.1  909.06   173.7  905.73  184.59 899.826
   190.7  899.01  244.22 899.824   251.8  905.28   329.1  901.89   350.4  903.78
   449.3  906.52   473.2  909.24   500.5  918.18   517.5  920.39   522.1  921.93
   565.3  946.01   599.4  959.12   616.5   972.9   626.7  975.35   633.5  979.87
#Mann= 5 ,-1,0
       0      .1       0  184.59    .045       0  244.22      .1       0
   272.5     .05       0  490.97      .1       0
Bank Sta=184.59,244.22
XS Rating Curve= 0 ,0
Exp/Cntr(USF)=0,0
Exp/Cntr=0.3,0.1

Type RM Length L Ch R = 1 ,33306   ,298.1,300,302.4
XS GIS Cut Line= 6
  1673301.718225456206.4202340841673341.04951118456284.582151249
1673374.76237026456351.578080252 1673419.7124116456440.905985594
 1673453.4249426456507.9019145821673555.04808558456714.422133399
#Sta/Elev= 30
       0 1036.63    16.7 1032.61    31.4 1026.35    68.1  997.14    71.8  991.53
    79.1  975.24    90.1  956.02   108.5  940.72   112.2  938.24   119.5  935.77
     134  933.51   145.2  933.79   152.6  930.87   178.3  910.46   187.8  900.83
     192898.4669   207.7  897.66  242.54898.4658   259.1  902.99   299.5  901.36
   405.5  906.33   422.6  908.27   431.3  909.98   442.4  914.06     457  915.74
   475.2  924.58     501  944.33   523.1  955.72   548.3   974.3   567.7  986.18
#Mann= 5 ,-1,0
       0      .1       0     192    .045       0  242.54      .1       0
   312.5     .05       0   417.5      .1       0
Bank Sta=192,242.54
XS Rating Curve= 0 ,0
Exp/Cntr(USF)=0,0
Exp/Cntr=0.3,0.1

Type RM Length L Ch R = 1 ,33006   ,299.2,300,300.6
XS GIS Cut Line= 6
1673044.08521008456320.2375917581673076.62910825456401.460198343
1673104.52406558456471.079809755 1673141.7169046456563.905739591
1673169.61186193456633.5253510031673255.00950649456844.994209386
#Sta/Elev= 30
       0  939.71      56  936.95    70.2  937.23    87.8  934.71   127.9  934.11
   133.8  933.29     138     932   144.4  928.16   157.4  915.63   172.7  905.79
   179.7  899.52  182.75897.8958   186.8  897.02   216.2  896.59  232.77897.8957
   243.4  901.73   268.1  902.98     314  902.87   335.2   901.4     354  903.11
   395.4  904.63   409.5  906.47   423.7  911.05   434.3  912.55   444.9  918.46
   473.5  931.07   496.1   944.9   515.7  954.19   540.5  970.92   565.6  984.66
#Mann= 3 ,-1,0
       0      .1       0  182.75    .045       0  232.77      .1       0
Bank Sta=182.75,232.77
XS Rating Curve= 0 ,0
Exp/Cntr(USF)=0,0
Exp/Cntr=0.3,0.1

Type RM Length L Ch R = 1 ,32706   ,419.6,422.8,420.1
XS GIS Cut Line= 6
  1672775.900379456443.650074586 1672806.7864721456525.517364919
1672833.26017243456595.6897967611672868.55865826456689.252601758
1672895.03235859456759.4247055051672971.22138166456963.987759306
#Sta/Elev= 30
       0  978.31     7.8  970.73    11.3  968.94    21.9  966.92    30.1  963.26
    75.9  938.05    91.2  934.42     113  934.23   116.5  933.15   144.6  912.22
   169.1  902.51   176.2  898.22  181.92897.0203   214.7  896.39  235.98897.0212
   246.3  901.37   256.8  902.13   281.4  902.19   298.9  900.72   316.4  902.01
   333.9  901.06   389.2  904.31   427.5  909.92   449.5  916.37     460  921.25
     467  926.16   484.5  941.43     502  953.97     516  966.61   555.8  996.02
#Mann= 5 ,-1,0
       0      .1       0  181.92    .045       0  235.98      .1       0
   272.5     .05       0   367.5      .1       0
Bank Sta=181.92,235.98
XS Rating Curve= 0 ,0
Exp/Cntr(USF)=0,0
Exp/Cntr=0.3,0.1

Type RM Length L Ch R = 1 ,32283   ,375.3,384.2,383.9
XS GIS Cut Line= 2
1672398.45392577456608.5823585021672601.57064812457098.762547961
#Sta/Elev= 30
       0  964.12    24.1  961.08    28.3  959.81    35.4   956.1    54.2   942.5
    63.8  937.33    74.5  933.56     107  932.14     112  928.11   120.6  916.65
   124.5  912.43   134.8  905.11   152.6  898.67   167.2  898.27  177.65895.9301
   223.6   894.9   237.5  895.75   248.5  894.76  263.38895.9318   276.9  900.33
   307.8  898.87   326.6  898.99   337.2  904.07   340.8  904.77   422.5     910
   432.6  914.47   468.5  941.96     494  953.61   518.4  967.14   530.6  972.25
#Mann= 4 ,-1,0
       0      .1       0     160     .06       0  177.65    .045       0
  263.38      .1       0
Bank Sta=177.65,263.38
XS Rating Curve= 0 ,0
Exp/Cntr(USF)=0,0
Exp/Cntr=0.3,0.1

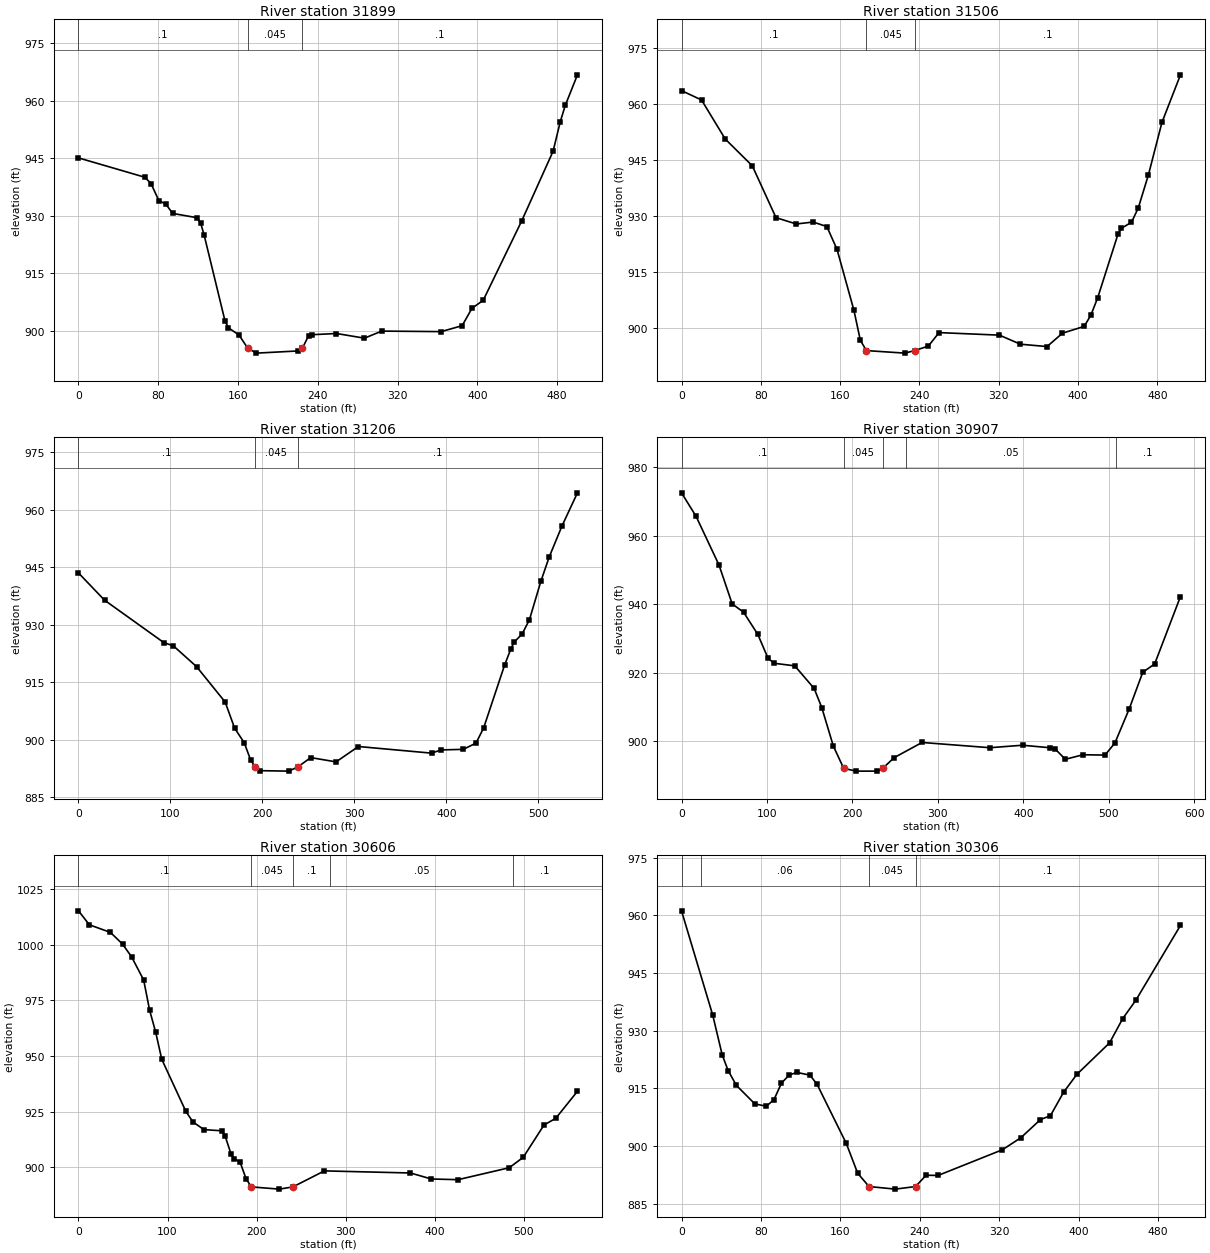
Type RM Length L Ch R = 1 ,31899   ,391.2,393,394.7
XS GIS Cut Line= 6
1672045.09365965456706.6677733371672075.12312715456788.853632585
1672100.86290507456859.2983735961672135.18239024456953.224694923
1672160.92184007457023.6697640131672219.26531073457175.697640329
#Sta/Elev= 30
       0  945.13    66.6  940.08    72.7  938.43    80.6  933.98    87.5  933.09
    94.5  930.64     119  929.52   122.5  928.11     126  924.99   146.9   902.6
   150.4   900.8   160.9  898.93  169.75895.4755   178.4   894.2   220.3  894.77
  224.52895.4744   230.8  898.79   234.3  899.01   258.7  899.32   286.7   898.1
   304.1  899.95   363.7  899.81   384.7  901.36   394.6  905.92   405.8  907.97
   444.5  928.74   475.9  946.88   483.1  954.59   488.1  958.83   500.3   966.8
#Mann= 3 ,-1,0
       0      .1       0  169.75    .045       0  224.52      .1       0
Bank Sta=169.75,224.52
XS Rating Curve= 0 ,0
Exp/Cntr(USF)=0,0
Exp/Cntr=0.3,0.1

Type RM Length L Ch R = 1 ,31506   ,301,300,299.3
XS GIS Cut Line= 6
1671677.78577735456802.3668768411671702.28572834456886.366708845
1671723.28568634456958.3668929191671751.28563035457054.367029011
1671772.28558834457126.3668850061671817.54938225457285.871600327
#Sta/Elev= 30
       0  963.62    20.2  961.11    44.1  950.67    71.4   943.5    95.3  929.64
   115.8  927.95   132.8  928.47   146.6  927.26   156.9  921.13   173.9  904.87
   180.4  896.83  186.53894.0853   225.2  893.41  235.11894.0849     249   895.3
   259.8   898.9   320.7  898.22   341.8   895.8   368.7  895.16   384.3  898.75
   406.2  900.56     413  903.61   419.8  908.22   440.3  925.24   443.7   926.8
   453.9   928.4   460.8  932.28     471  941.12   484.6   955.1   503.3  967.84
#Mann= 3 ,-1,0
       0      .1       0  186.53    .045       0  235.11      .1       0
Bank Sta=186.53,235.11
XS Rating Curve= 0 ,0
Exp/Cntr(USF)=0,0
Exp/Cntr=0.3,0.1

Type RM Length L Ch R = 1 ,31206   ,304.2,298.7,292.5
XS GIS Cut Line= 6
1671388.61345543456903.0422004161671415.74069776456986.231010422
 1671438.9919636457057.5356578381671469.99387009457152.608630419
1671493.24513592457223.9136059281671558.12481992 457418.47211881
#Sta/Elev= 30
       0  943.49    28.3   936.4    92.8  925.33   103.2  924.48   128.4  919.06
   159.5  909.83   169.8  903.01   180.2  899.23   187.1  894.79  192.17892.8735
   197.4  891.93   228.5  891.81  238.33892.8744   252.6  895.34   280.1  894.22
   304.4  898.23   383.9   896.5   394.3  897.34   418.5  897.49   432.3  899.12
   440.6  903.08   463.4  919.48   470.3  923.76   473.8  925.45   482.6  927.63
   490.4   931.3   502.8  941.29   511.8   947.6   525.7   955.7   542.6  964.39
#Mann= 3 ,-1,0
       0      .1       0  192.17    .045       0  238.33      .1       0
Bank Sta=192.17,238.33
XS Rating Curve= 0 ,0
Exp/Cntr(USF)=0,0
Exp/Cntr=0.3,0.1

Type RM Length L Ch R = 1 ,30907   ,316.2,301.3,281.5
XS GIS Cut Line= 6
1671068.76271717457040.0435668381671114.11367634457114.873469666
1671152.98597392457179.0134332631671207.08101009457263.160902753
1671255.57402334457321.4701693361671420.52565082457503.220467563
#Sta/Elev= 30
       0  972.55    17.1  965.65    43.9  951.44    59.3   940.1    72.6  937.69
    89.3   931.2   101.2  924.24   108.4  922.77   132.5  922.03   155.2  915.41
   164.1  909.85   177.6  898.62  189.74892.0908   204.4  891.28   229.2  891.28
  235.37892.0913   248.8  895.22   281.5  899.65   360.8  898.12     399  898.84
   431.1  898.11   437.5  897.66   449.1  894.74   469.8  896.06   495.5  895.97
   507.1   899.5   523.8  909.44   539.7  920.16   553.6  922.57   583.8  942.27
#Mann= 5 ,-1,0
       0      .1       0  189.74    .045       0  235.37      .1       0
   262.5     .05       0  508.37      .1       0
Bank Sta=189.74,235.37
XS Rating Curve= 0 ,0
Exp/Cntr(USF)=0,0
Exp/Cntr=0.3,0.1

Type RM Length L Ch R = 1 ,30606   ,315,300,277.8
XS GIS Cut Line= 6
1670827.04436859457421.9151784181670911.80863476457443.623140261
1670984.46400125457462.2300584171671081.33749518457487.039063916
1671155.16674384457501.0626579231671374.60752973457539.267886833
#Sta/Elev= 30
       0 1015.33    12.2 1009.05    35.9 1005.61    49.5 1000.35    59.6  994.64
    73.2  984.21    79.9  970.57    86.7  960.72    93.5  948.55   120.6  925.07
   128.5  920.35   140.9  916.86   161.2  916.34   164.6   914.1   171.4  905.81
   174.8  903.82   181.5  902.25   188.3  894.66  194.27891.0876   225.6  890.09
  240.79891.0855   276.2   898.3   372.9  897.35   396.2  894.66   426.2  894.34
   483.8  899.72   499.5  904.39   522.8  918.92   536.1  921.98   560.4  934.11
#Mann= 5 ,-1,0
       0      .1       0  194.27    .045       0  240.79      .1       0
   282.5     .05       0  487.65      .1       0
Bank Sta=194.27,240.79
XS Rating Curve= 0 ,0
Exp/Cntr(USF)=0,0
Exp/Cntr=0.3,0.1

Type RM Length L Ch R = 1 ,30306   ,302.7,300,297.2
XS GIS Cut Line= 6
1670933.15734534 457861.418236421671007.98659201457816.065964922
1671072.12622751 457777.193011181671157.64606959457725.362734258
1671221.78570509457686.4901085941671385.33384582 457663.78995825
#Sta/Elev= 30
       0  961.17    31.5  934.01      41  923.72      47  919.63    55.3   915.8
    73.9  910.99    85.4   910.4    93.1  912.08   100.7   916.4   108.4  918.49
   116.1  919.18   129.4  918.47   136.6  916.06     166  900.71   177.5  892.95
   188.9889.5217   215.4  888.85  235.71889.5232   246.4  892.46   258.4   892.4
   323.3  899.09   341.8   902.2   361.6  906.93   371.6  907.93   384.8     914
   398.2  918.66   431.2  926.86   444.4  933.16   457.7  937.95   502.6  957.38
#Mann= 4 ,-1,0
       0      .1       0      20     .06       0   188.9    .045       0
  235.71      .1       0
Bank Sta=188.9,235.71
XS Rating Curve= 0 ,0
Exp/Cntr(USF)=0,0
Exp/Cntr=0.3,0.1

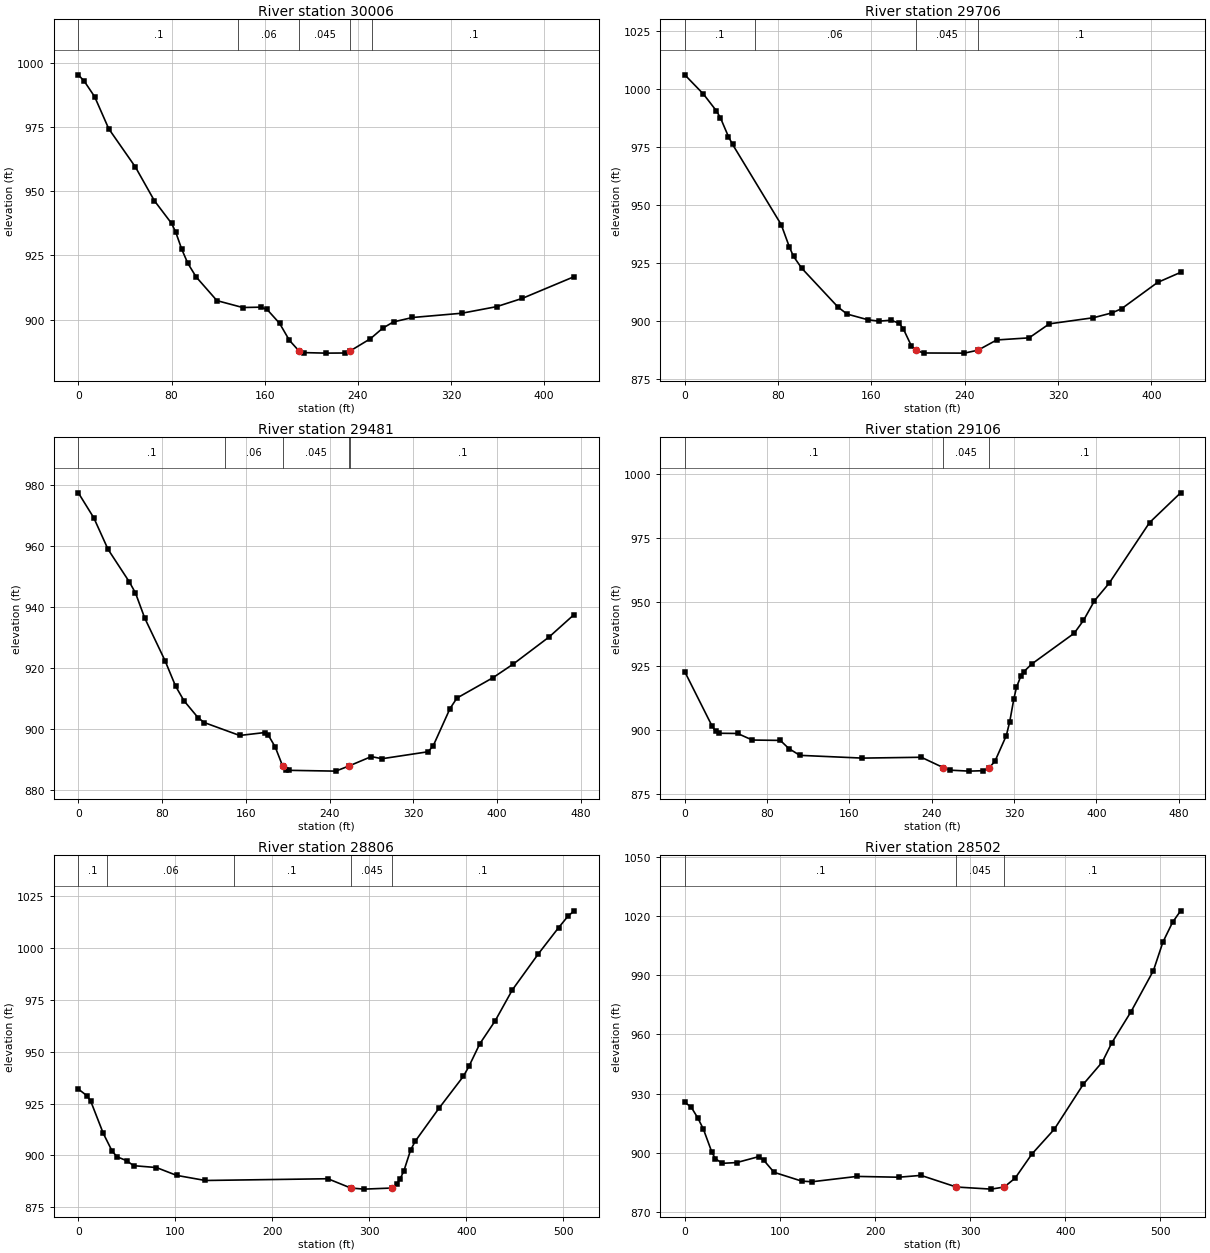
Type RM Length L Ch R = 1 ,30006   ,311.6,300,286.8
XS GIS Cut Line= 6
1671078.39754042458153.7021006791671146.50895275 458098.77406092
1671204.88974151458051.6924621761671282.73144934457988.917653337
1671341.11256617457941.8363826721671406.68494159457882.902445421
#Sta/Elev= 30
       0  995.33     5.2  992.77      14  986.82    26.1  974.34      49  959.44
    65.3  946.32    80.1  937.46    83.6  934.12    88.8  927.42      94  921.96
   101.1  916.68     119  907.43   141.1  904.75   156.8  904.88     162  904.01
   172.8  898.58   181.2  891.98  189.37887.8735   193.8  887.19   212.3  886.99
   228.6  887.04  233.52887.8755   250.8  892.61   261.3  896.69   270.6  899.15
   286.9  900.86   329.2  902.52   359.2  905.09   381.2  908.31   425.7  916.76
#Mann= 5 ,-1,0
       0      .1       0   137.5     .06       0  189.37    .045       0
  233.52     .06       0   252.5      .1       0
Bank Sta=189.37,233.52
XS Rating Curve= 0 ,0
Exp/Cntr(USF)=0,0
Exp/Cntr=0.3,0.1

Type RM Length L Ch R = 1 ,29706   ,224.4,224.5,220.8
XS GIS Cut Line= 6
1671434.36926943 458356.290606261671463.89709751458273.923645005
1671489.20675817458203.3230644171671522.95275368458109.189066336
1671547.15775776458038.1928172561671572.61275934457954.365229011
#Sta/Elev= 30
       0 1006.27      16  997.94      27  990.79    30.5  987.78    37.4  979.63
    40.9  976.29    82.7   941.6    89.7  931.92    93.2  927.95   100.2  922.85
   131.4  906.04   139.1  903.05   157.1  900.57   166.4  899.99   176.9  900.39
   183.8  899.05   187.3  896.73   194.3  889.25  197.83 887.449   204.7  886.25
   239.6  886.19  251.31887.4471   267.4  891.87   295.2  892.78   312.5  898.82
   350.4  901.47   366.2  903.55   374.5  905.36   405.3  916.68   425.1  921.04
#Mann= 4 ,-1,0
       0      .1       0      60     .06       0  197.83    .045       0
  251.31      .1       0
Bank Sta=197.83,251.31
XS Rating Curve= 0 ,0
Exp/Cntr(USF)=0,0
Exp/Cntr=0.3,0.1

Type RM Length L Ch R = 1 ,29481   ,374.4,375.5,376.2
XS GIS Cut Line= 3
1671667.83592007458410.8227352631671761.43875131458063.667300151
1671820.33442462457965.910161568
#Sta/Elev= 30
       0  977.41    14.8  969.19    28.4  958.86    48.8  948.14    54.6  944.54
    63.4  936.34    82.8  922.36    92.9  913.99   100.9   909.2   114.3  903.66
   120.2  902.04   154.1  897.79   177.9  898.74   181.2  898.07   188.1  894.01
  195.14  887.81   198.3  886.56   201.7  886.35   245.9  886.09   258.8  887.81
   279.9  890.86   290.1  890.16   334.2  892.45   339.1  894.44   355.1  906.63
   361.7  910.06   396.2  916.76   415.4   921.2   449.8  930.12   473.7  937.48
#Mann= 5 ,-1,0
       0      .1       0     140     .06       0  195.14    .045       0
   258.8     .06       0     260      .1       0
Bank Sta=195.14,258.8
XS Rating Curve= 0 ,0
Exp/Cntr(USF)=0,0
Exp/Cntr=0.3,0.1

Type RM Length L Ch R = 1 ,29106   ,298.5,300,302.1
XS GIS Cut Line= 6
1671978.56558268 458453.676743911672034.40087776458320.659772009
1672064.46216933458251.9479671721672104.54411018458160.332008675
1672134.60540175458091.620531917  1672169.677182458011.456650257
#Sta/Elev= 30
       0  922.75    26.4   901.6      30  899.49    33.5  898.71    51.3  898.63
    65.6  896.06    92.8  895.92   101.1  892.74   111.8  890.08   172.5     889
   229.8  889.33  250.99885.3207   257.6  884.29   276.3  883.91     290  884.08
  295.98885.3205   301.4  887.79   312.4  897.78   315.7  903.16   319.8  912.27
   322.3  916.66   326.5  921.02   329.2  922.69   337.2   925.8   378.4  937.81
   387.4  942.81   398.1  950.51   412.4  957.39   451.6  981.06   481.8  992.69
#Mann= 3 ,-1,0
       0      .1       0  250.99    .045       0  295.98      .1       0
Bank Sta=250.99,295.98
XS Rating Curve= 0 ,0
Exp/Cntr(USF)=0,0
Exp/Cntr=0.3,0.1

Type RM Length L Ch R = 1 ,28806   ,285.9,303.6,323.5
XS GIS Cut Line= 6
1672214.85108368458601.3829074871672294.47778542458447.159847096
1672330.09746484458381.1583386661672377.59080817458293.156218082
1672413.21081567458227.1543815881672454.76749109458150.152567089
#Sta/Elev= 30
       0  931.99       9  928.71    12.7  926.24    25.7  910.66    34.9  902.04
      40  899.35    49.7  897.53      57   895.1    80.5   894.2   101.3  890.43
   130.9  887.97   257.2  888.81  280.88 884.338   294.5  883.81  323.44 884.338
   328.1   886.1   331.8  888.82   335.5  892.49   342.5  902.62   347.3  906.88
   371.6  922.64   396.9  938.11   402.6  942.86   413.8  953.74   429.7  964.84
   447.4  979.73   474.1  997.01     495 1009.64   504.7 1015.17   511.1 1017.77
#Mann= 5 ,-1,0
       0      .1       0      30     .06       0     160      .1       0
  280.88    .045       0  323.44      .1       0
Bank Sta=280.88,323.44
XS Rating Curve= 0 ,0
Exp/Cntr(USF)=0,0
Exp/Cntr=0.3,0.1

Type RM Length L Ch R = 1 ,28502   ,285.5,296.4,306.1
XS GIS Cut Line= 6
1672289.62074818458659.4768894941672454.19957884458581.049999252
1672524.68008092458552.3745316711672620.80620101458523.906740844
1672694.04916476458507.7683216781672779.49978125 458488.94060342
#Sta/Elev= 30
       0   925.5     6.6  923.19    13.8  917.52    19.6  911.89    28.4  900.34
      32  897.05    39.3  894.63    54.6  895.03    77.5     898    82.9  896.26
    93.8  890.09     123  885.62   133.8  885.31     181  888.01   224.8   887.6
   248.3  888.53  285.43882.6398   322.1  881.57  335.77 882.641   347.3  887.17
   364.9  899.37   388.4   911.9   419.1  934.83   438.8  945.92   448.9  955.71
   469.1  971.49   492.6  992.26   502.6 1006.72   512.7 1016.72   521.2 1022.54
#Mann= 3 ,-1,0
       0      .1       0  285.43    .045       0  335.77      .1       0
Bank Sta=285.43,335.77
XS Rating Curve= 0 ,0
Exp/Cntr(USF)=0,0
Exp/Cntr=0.3,0.1