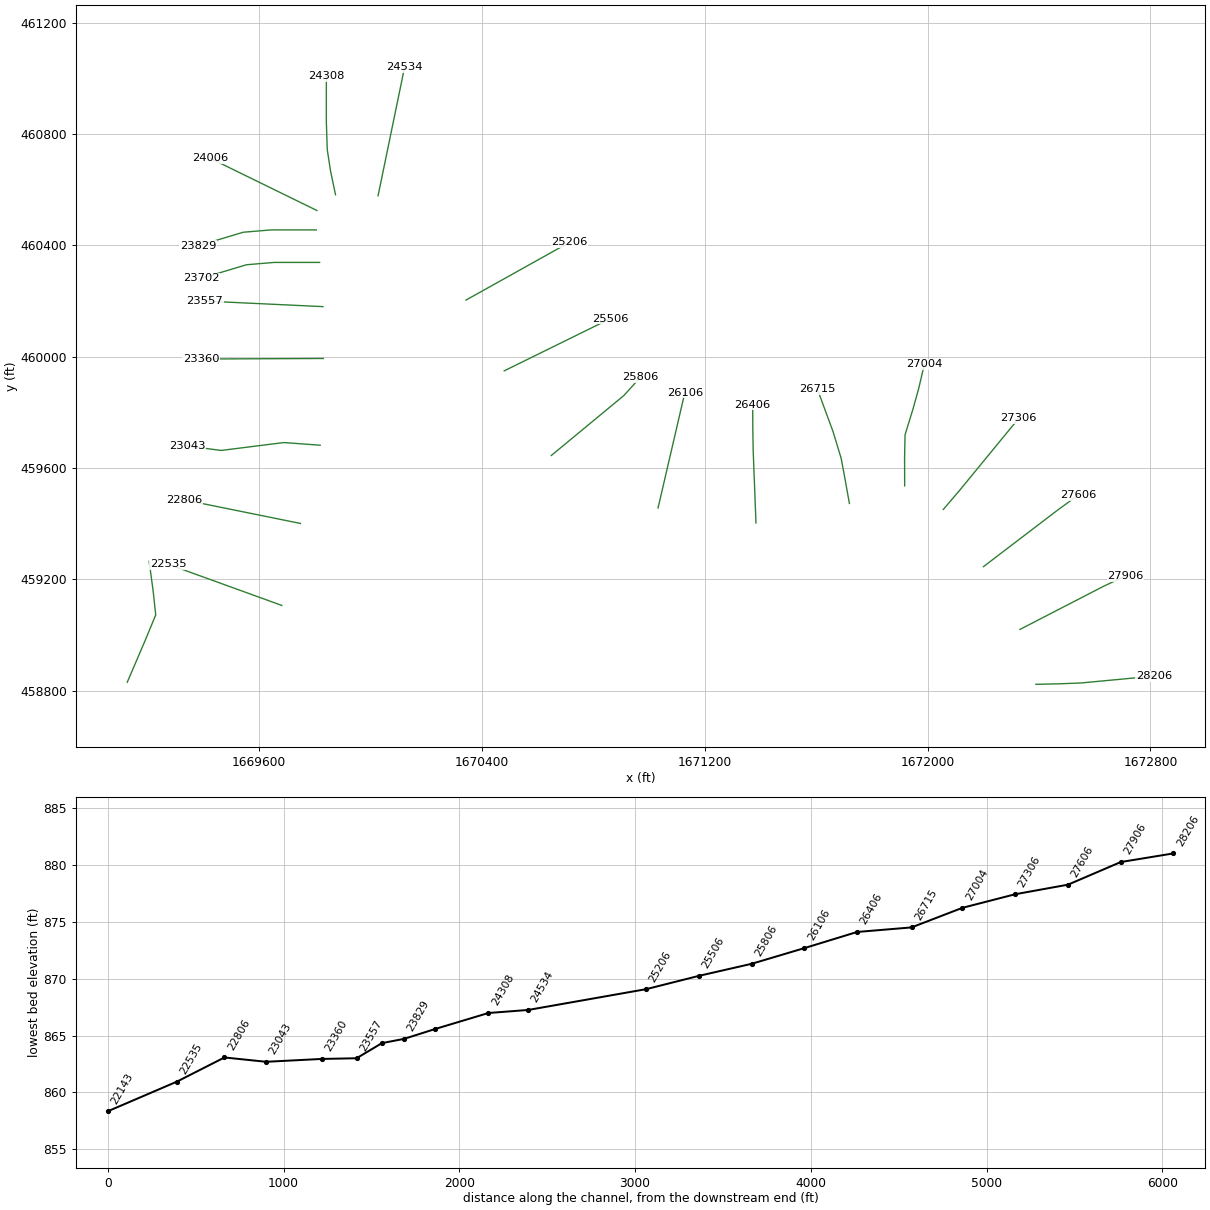
HEC-RAS study PenFrkFshCk.prj: PenFrkFshCk

--- PenFrkFshCk.g01 (geometry) --- (continued)

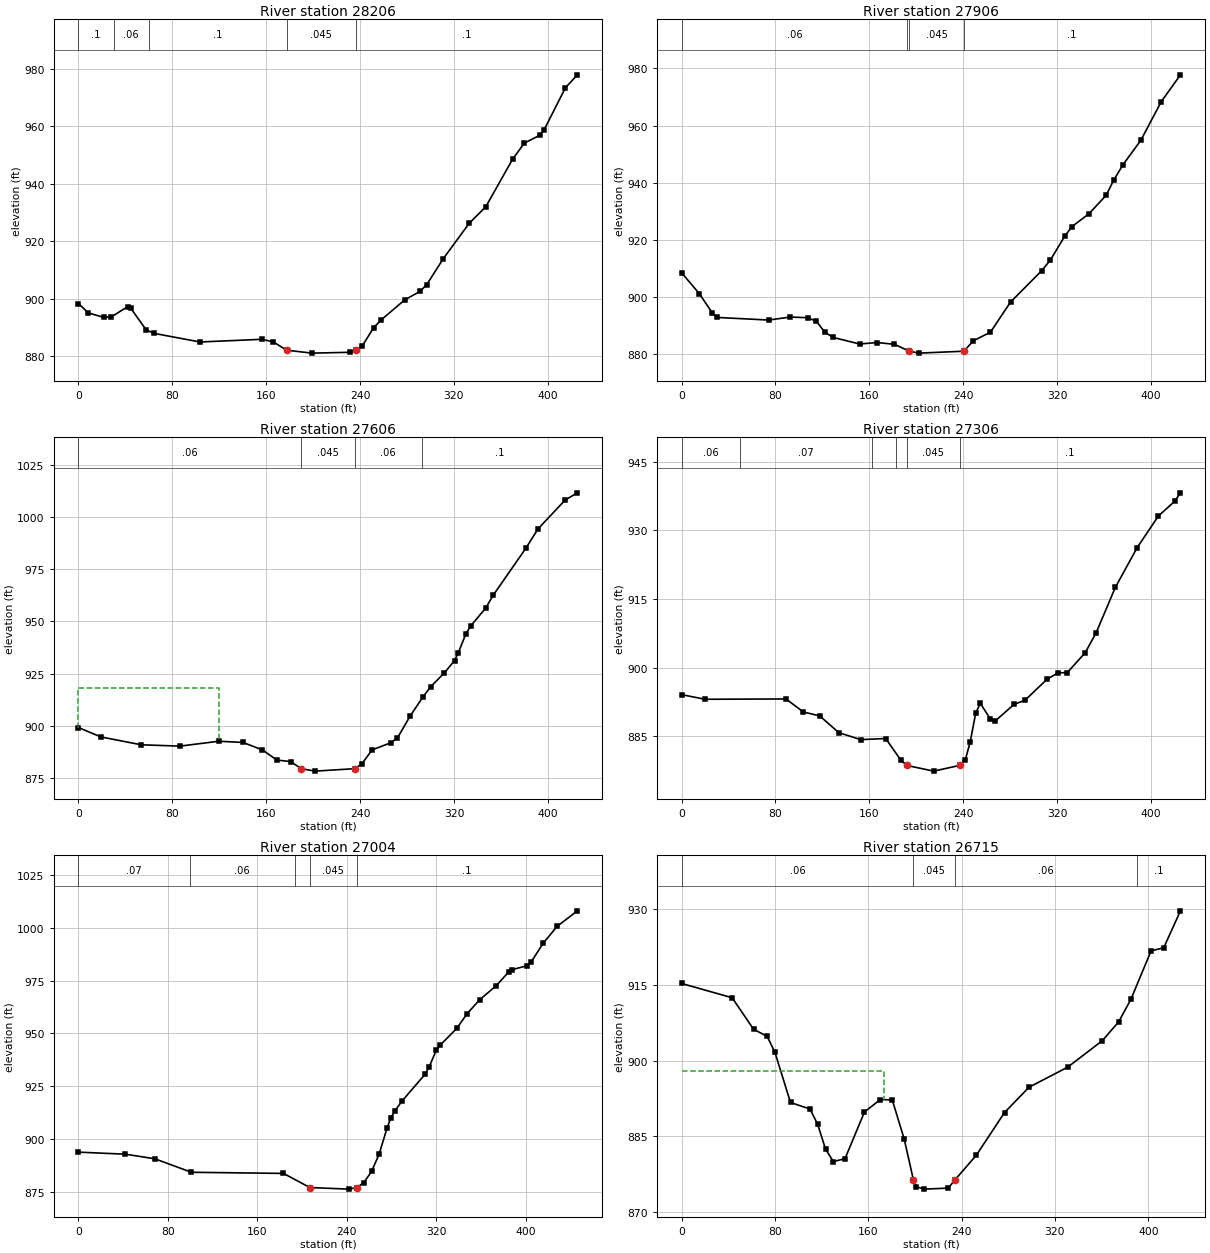
Type RM Length L Ch R = 1 ,28206   ,290,300,309.7
XS GIS Cut Line= 6
 1672388.9031215458822.6266158371672476.59848417458824.657123595
1672551.64918709 458827.638744921672651.20935543458837.008804917
1672725.87915359458844.0366780011672812.99446492458852.235808596
#Sta/Elev= 30
       0  898.28     8.4  894.99    21.5  893.47      28  893.62    41.8  897.17
    44.5  896.67    57.6  889.17    64.1  887.92   103.5   884.9   156.1  885.82
   165.9  884.98  177.33882.0438   198.9  881.02   231.8  881.31  236.79882.0436
   241.7  883.41   251.6  889.88   257.8   892.5     278  899.53   291.2  902.52
   296.9  904.88   310.9  913.86   333.1  926.21   347.2  931.96   370.2  948.61
   380.1  954.11   393.3  956.83   396.6  958.48   415.1  973.37   425.3  977.84
#Mann= 5 ,-1,0
       0      .1       0      30     .06       0      60      .1       0
  177.33    .045       0  236.79      .1       0
Bank Sta=177.33,236.79
XS Rating Curve= 0 ,0
Exp/Cntr(USF)=0,0
Exp/Cntr=0.3,0.1

Type RM Length L Ch R = 1 ,27906   ,296,300,304
XS GIS Cut Line= 6
1672331.36058567459019.7987936741672409.09796301459059.962755337
1672475.73004758459094.3888675871672564.57271767459140.291006759
1672631.24974968459174.6298488381672710.48220275459211.900443584
#Sta/Elev= 30
       0  908.46    15.1  901.13    26.2  894.36    29.9  892.77    74.2  891.85
    92.8  892.91   107.4  892.66   114.8  891.45   122.2  887.54   129.3  885.75
   151.7  883.46   166.5  883.97   181.3  883.36  194.14880.9282   202.3  880.26
  240.59880.9299   248.6  884.57   263.2   887.6   280.3  898.14   306.8  909.11
   314.2  912.83   326.5  921.23   332.6  924.56   347.2  929.12   361.7  935.51
   368.3  940.92   376.2  946.31   391.3   954.8   408.8   968.4   425.1  977.76
#Mann= 4 ,-1,0
       0     .06       0   192.5      .1       0  194.14    .045       0
  240.59      .1       0
Bank Sta=194.14,240.59
XS Rating Curve= 0 ,0
Exp/Cntr(USF)=0,0
Exp/Cntr=0.3,0.1

Type RM Length L Ch R = 1 ,27606   ,295,300,305.4
XS GIS Cut Line= 6
1672200.61379993459245.4568069281672270.17205976459298.540690258
1672329.79333159459344.0412554291672409.28857942459404.708456919
1672468.91017935459450.2086940111672539.73451276459501.633459926
#Sta/Elev= 30
       0  899.14    19.1  894.65    53.4  890.89    86.4  890.24   119.4  892.58
   140.1  892.01   156.6  888.45     169  883.56   180.6  882.85  189.85879.4313
   201.4  878.27  235.11879.4318   241.5   881.8     250   888.4   266.3  891.93
   271.7  894.18   282.5  904.66   293.3  913.69     300   918.7   311.7  925.37
   320.3   931.2   323.4  934.77   329.9  943.93     334  947.73   346.9  956.41
   353.3  962.55   381.2  985.13   391.5  994.34   414.7  1008.2     425 1011.56
#Mann= 4 ,-1,0
       0     .06       0  189.85    .045       0  235.11     .06       0
   292.5      .1       0
#XS Ineff= 2 , 0
           119.6  917.87
Permanent Ineff=
       F       F
Bank Sta=189.85,235.11
XS Rating Curve= 0 ,0
Exp/Cntr(USF)=0,0
Exp/Cntr=0.3,0.1

Type RM Length L Ch R = 1 ,27306   ,291.9,301.4,308.9
XS GIS Cut Line= 6
1672056.27813059459450.8297557531672113.08904059 459517.40016067
1672160.66309242459575.3806877581672224.09505217 459652.68794784
1672271.66877593459710.6681468341672327.17161767459778.312040418
#Sta/Elev= 30
       0  894.14      20  893.12      89  893.19   103.7  890.35   117.7  889.49
     134  885.83   152.6  884.31   173.9  884.55   186.6   879.9  191.72 878.679
   214.8  877.43  236.89 878.679   241.8  879.94   245.9  883.81   250.6  890.12
   254.5  892.24     263  888.84   267.2  888.38   283.2  891.99   292.7  892.94
   311.2  897.45   320.5  898.88   328.6  898.95   343.9   903.3   353.2  907.66
   369.5  917.54   388.1  926.23   406.2  933.14     420  936.33     425   938.2
#Mann= 6 ,-1,0
       0     .06       0      50     .07       0  162.52     .06       0
  182.52      .1       0  191.72    .045       0  236.89      .1       0
Bank Sta=191.72,236.89
XS Rating Curve= 0 ,0
Exp/Cntr(USF)=0,0
Exp/Cntr=0.3,0.1

Type RM Length L Ch R = 1 ,27004   ,269.2,289,296.2
XS GIS Cut Line= 6
1671917.58877543459535.6422501651671917.25872359459635.141395003
1671918.94080684459718.8059258461671948.35774276459814.757833675
1671968.34162667459887.0398413391671988.25464459459972.242098749
#Sta/Elev= 30
       0  893.76    41.9  892.78    68.2  890.62     101  884.21   183.2  883.68
  206.83 876.993   241.4  876.23  248.88876.9917   255.1  879.37     262  884.63
   268.8  892.89   275.7  905.01   279.1  909.84   282.5  913.07   289.4   918.1
   309.8  930.67   313.2  933.87     320  942.26   323.4  944.53   338.3  952.49
   347.2  959.26   358.5  965.92   373.3  972.59   384.4  979.04   387.8  980.25
   401.3  982.15   404.6  983.83   415.4  992.77   427.9 1000.78     446 1008.11
#Mann= 5 ,-1,0
       0     .07       0    99.5     .06       0  193.18      .1       0
  206.83    .045       0  248.88      .1       0
Bank Sta=206.83,248.88
XS Rating Curve= 0 ,0
Exp/Cntr(USF)=0,0
Exp/Cntr=0.3,0.1

Type RM Length L Ch R = 1 ,26715   ,314.6,309.5,303.4
XS GIS Cut Line= 6
1671719.12697658459472.560969966 1671703.5082414459560.056201803
1671689.49448991459634.8211441371671660.39776333459730.672330382
1671634.46999366459801.0478457981671604.22071033459883.152996543
#Sta/Elev= 30
       0   915.3    43.4  912.46    61.7  906.23    73.4  904.79      80  901.68
    93.4  891.69   110.1  890.39   116.7  887.35   123.4  882.46   130.1  879.98
   140.1  880.54   156.8  889.82   170.3  892.26   180.6  892.21   190.9  884.39
   198.7  876.37   201.1     875     208  874.51   228.6  874.71   234.6 876.416
   252.6  881.22   276.8  889.69   297.8  894.72   330.9  898.69   360.7  903.96
   374.7  907.71   385.2  912.19   402.4  921.76   413.2  922.36   427.6   929.7
#Mann= 4 ,-1,0
       0     .06       0   198.7    .045       0   234.6     .06       0
  390.12      .1       0
#XS Ineff= 2 , 0
          173.65  897.91
Permanent Ineff=
       F       F
Bank Sta=198.7,234.6
XS Rating Curve= 0 ,0
Exp/Cntr(USF)=0,0
Exp/Cntr=0.3,0.1

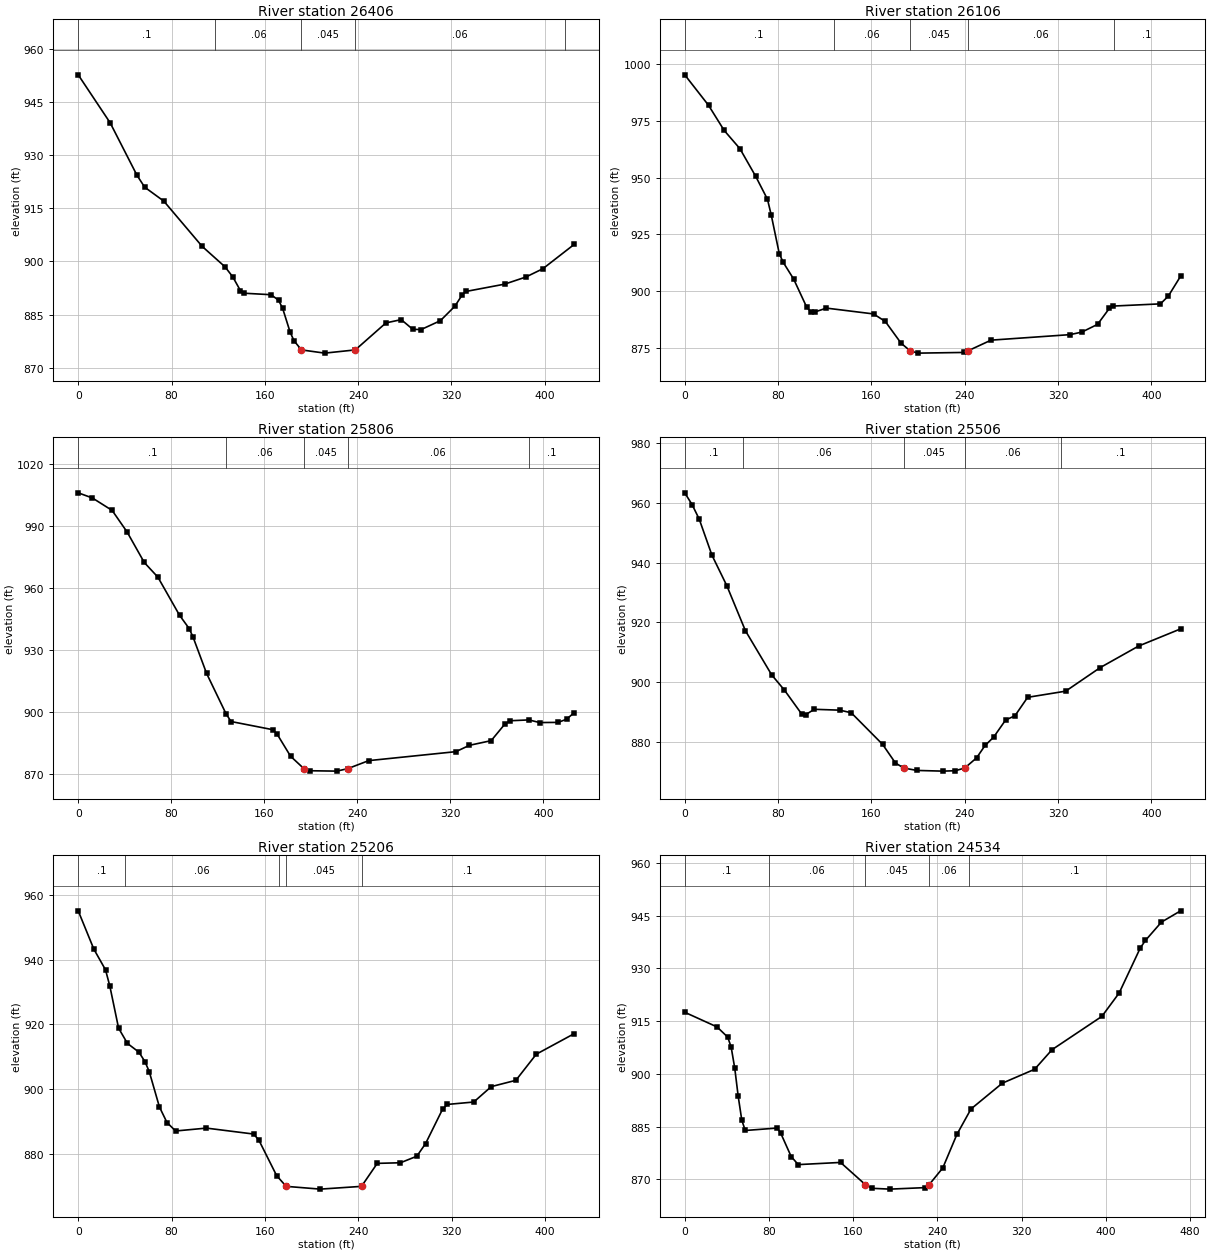
Type RM Length L Ch R = 1 ,26406   ,305.5,300,293
XS GIS Cut Line= 6
 1671383.7381371459402.5631200081671380.37528293459489.998312593
1671377.49274276459564.9430445881671373.64957459459664.869025841
1671372.39990517 459739.876421751671371.92484051 459827.42283459
#Sta/Elev= 30
       0  952.72    27.4  939.16    50.4  924.33      57  920.98    73.4  917.04
   106.2  904.28   125.9  898.47   132.5  895.65     139   891.8   142.3  891.03
   165.3  890.61   171.7  889.07   175.2  886.81   181.7     880     185  877.61
  191.35875.0225   211.3  874.11  237.55875.0216   263.8  882.65   276.9  883.57
   286.8  880.84   293.9  880.76   310.5  883.28   322.9  887.36   329.4  890.67
   332.7  891.55   365.5  893.59   383.7   895.6   398.3  897.94   425.1   904.8
#Mann= 5 ,-1,0
       0      .1       0   117.5     .06       0  191.35    .045       0
  237.55     .06       0  417.52      .1       0
Bank Sta=191.35,237.55
XS Rating Curve= 0 ,0
Exp/Cntr(USF)=0,0
Exp/Cntr=0.3,0.1

Type RM Length L Ch R = 1 ,26106   ,311.4,300,285.1
XS GIS Cut Line= 6
1671032.15517884 459456.060716421671051.94155659459541.294141755
1671068.90116835459614.3514103441671091.51398401459711.760992423
1671108.47326767459784.8185890911671128.25964542459870.052014425
#Sta/Elev= 30
       0  995.38    20.4  981.94    33.8  970.86    47.3  962.82    60.8  950.64
    70.9  940.52    74.2  933.42      81   916.6    84.3  912.79    93.3  905.39
   104.6  892.87   107.9  891.04   111.3  890.79   121.4  892.54   161.8  889.97
   171.9  886.65   185.4  877.08  193.22873.6845   199.9  872.69   239.3  872.99
  242.67873.6837   262.5  878.41   330.2  880.84   340.3  881.96   353.8  885.37
   363.9  892.41   367.3  893.44   407.7  894.41   414.4  897.79     425  906.62
#Mann= 5 ,-1,0
       0      .1       0   127.5     .06       0  193.22    .045       0
  242.67     .06       0   367.5      .1       0
Bank Sta=193.22,242.67
XS Rating Curve= 0 ,0
Exp/Cntr(USF)=0,0
Exp/Cntr=0.3,0.1

Type RM Length L Ch R = 1 ,25806   ,304.2,300,295.3
XS GIS Cut Line= 6
1670649.05555134459644.7726093381670716.48684692459700.533324584
1670774.28528775459748.3281764981670851.34976618459812.054427013
1670909.14820701459859.8489508331670968.88890117 459925.70183751
#Sta/Elev= 30
       0 1006.18    12.2 1003.68    29.2  997.64      42  987.24    56.8  972.43
    68.5  965.32    87.1  946.88    95.4  940.41    98.8  936.21   110.4  918.65
   127.1  899.12   131.4  895.35   167.4  891.38     171  889.27   182.6  878.53
  194.09872.5068     199   871.5   222.3  871.31  231.76872.5069   249.8   876.4
   324.8  880.75   336.4  883.82   355.1  886.08   366.6  893.93   371.3  895.72
   387.5  896.13   396.8  894.85   412.7  894.93   420.1  896.51   426.4  899.65
#Mann= 5 ,-1,0
       0      .1       0   127.5     .06       0  194.09    .045       0
  231.76     .06       0   387.5      .1       0
Bank Sta=194.09,231.76
XS Rating Curve= 0 ,0
Exp/Cntr(USF)=0,0
Exp/Cntr=0.3,0.1

Type RM Length L Ch R = 1 ,25506   ,298.8,300,301.5
XS GIS Cut Line= 6
1670480.02373718459948.8382741661670558.52620484459987.485506594
1670625.81412801460020.6117526741670715.53146826460064.779971421
1670782.81906334460097.9058894221670861.32185909460136.553121835
#Sta/Elev= 30
       0  963.38     6.3  959.44    12.4  954.59    23.3  942.52      36  932.36
      52  917.24    74.5  902.47    85.5  897.33   100.1  889.43   103.5  889.12
   111.1  890.94     133  890.65   142.7  889.78   169.6  879.19   180.6  872.96
  187.77871.2811     199  870.48   221.1  870.25   231.8  870.38  239.97871.2821
   250.1  874.68   257.4  878.83   264.7   881.6     275  887.35     283  888.77
   293.9  894.95   326.5  897.01   356.1   904.9     389  912.11     425  917.85
#Mann= 5 ,-1,0
       0      .1       0      50     .06       0  187.77    .045       0
  239.97     .06       0   322.5      .1       0
Bank Sta=187.77,239.97
XS Rating Curve= 0 ,0
Exp/Cntr(USF)=0,0
Exp/Cntr=0.3,0.1

Type RM Length L Ch R = 1 ,25206   ,640.6,671.7,694.2
XS GIS Cut Line= 6
1670342.76056026460203.0808759181670419.15542059460245.742864087
1670484.63691692460282.3103762571670571.94546933460331.067496583
1670637.42696567460367.6350087521670713.82182601460410.296996921
#Sta/Elev= 30
       0  955.09    13.4  943.25    23.4  936.86    27.1  931.84    34.6  918.83
    42.2  914.11      52  911.42    57.2  908.49    60.9  905.38    69.6  894.48
    76.1  889.65    83.5  887.05   109.9  887.94   150.4   886.1   154.9  884.17
   170.1  873.23  178.23869.9351   207.5  869.08   242.8869.9343   256.3  877.04
   276.2  877.23   290.2  879.25   297.7  883.15   312.4  893.87   316.5  895.26
     339     896     354  900.76   375.1  902.71   392.6  910.78     425  917.11
#Mann= 5 ,-1,0
       0      .1       0      40     .06       0   172.5      .1       0
  178.23    .045       0   242.8      .1       0
Bank Sta=178.23,242.8
XS Rating Curve= 0 ,0
Exp/Cntr(USF)=0,0
Exp/Cntr=0.3,0.1

Type RM Length L Ch R = 1 ,24534   ,216.4,226.7,232.7
XS GIS Cut Line= 2
1670027.01555101460577.6457220851670122.09642688 461038.98316448
#Sta/Elev= 30
       0  917.53    30.7  913.36    40.8  910.47    44.1  907.62    47.5  901.63
    50.8  893.59    54.2  886.84    57.5  883.92    87.7  884.61      91  883.27
   101.1  876.51   107.8  874.22     148  874.84  171.43868.5633   178.1  867.48
   194.9  867.25   228.4  867.68  232.27868.5641   245.1  873.28   258.5   882.8
   271.9  890.04   301.7  897.38   332.3  901.32   348.9   906.9   396.2  916.36
   412.6     923   432.7  935.82   437.6  937.96   452.8  943.17     471  946.37
#Mann= 5 ,-1,0
       0      .1       0      80     .06       0  171.43    .045       0
  232.27     .06       0     270      .1       0
Bank Sta=171.43,232.27
XS Rating Curve= 0 ,0
Exp/Cntr(USF)=0,0
Exp/Cntr=0.3,0.1

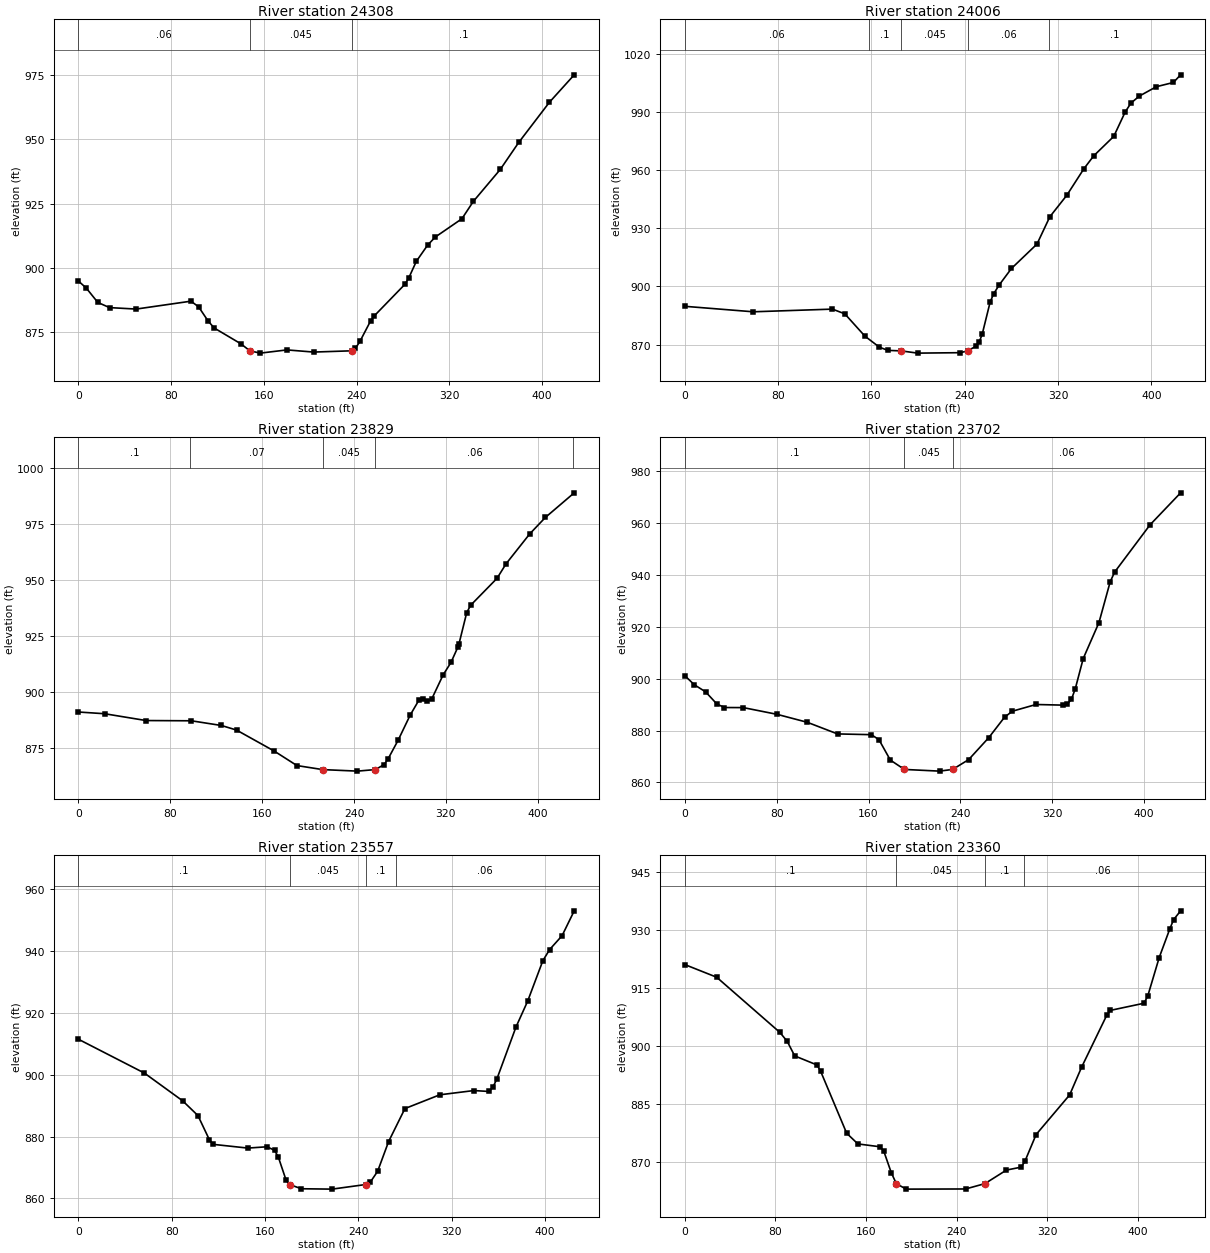
Type RM Length L Ch R = 1 ,24308   ,248.8,301.7,327
XS GIS Cut Line= 6
1669874.19522442460581.4462609291669855.99414533460668.946085915
1669844.61359067460743.9462639991669841.30027708460843.946392089
1669841.30027708460918.9462420941669841.30027708461006.446067095
#Sta/Elev= 30
       0  895.01     6.8  892.27    16.8  886.67    26.9  884.66    49.9  884.09
    97.2  887.16   103.8  884.93   111.7  879.62   117.1  876.77   140.3  870.58
  147.93867.8893   156.9  866.98     180  868.23     203  867.39  236.48867.8914
   239.1  868.86   242.9   871.5   252.2  879.54   255.5  881.53   281.7  893.69
     285  896.11   291.6  902.64   301.4  908.96     308  912.08   330.9  919.16
   340.8  925.92     364  938.31   379.9  948.78   406.4   964.4   427.8  975.06
#Mann= 3 ,-1,0
       0     .06       0  147.93    .045       0  236.48      .1       0
Bank Sta=147.93,236.48
XS Rating Curve= 0 ,0
Exp/Cntr(USF)=0,0
Exp/Cntr=0.3,0.1

Type RM Length L Ch R = 1 ,24006   ,164,177,190.9
XS GIS Cut Line= 6
1669807.56838918460524.7777390931669728.98127601460563.253055841
1669661.62117451460596.2316644191669571.80737776460640.202705085
1669504.44694817460673.1813136791669425.85983501460711.656302333
#Sta/Elev= 30
       0  889.74    58.7  886.91   126.6  888.29   137.2  885.85   154.4  874.35
   166.8  868.66   174.1     867  185.55866.7333   199.6  865.58   236.2  865.81
  242.51 866.733     250  869.31   252.5  871.57   254.9  875.23   261.7  891.83
   264.7  896.14   269.6  900.83     280  909.26   301.9  921.86   312.9  935.93
   327.5  947.07   342.1  960.73   350.5  967.37   367.7  977.43   377.5  990.02
   382.4  994.58   389.6  998.22   404.2 1003.06   418.8 1005.24     425 1009.19
#Mann= 5 ,-1,0
       0     .06       0   157.5      .1       0  185.55    .045       0
  242.51     .06       0   312.5      .1       0
Bank Sta=185.55,242.51
XS Rating Curve= 0 ,0
Exp/Cntr(USF)=0,0
Exp/Cntr=0.3,0.1

Type RM Length L Ch R = 1 ,23829   ,123.9,127.2,124.9
XS GIS Cut Line= 6
1669805.36953849460455.1176811741669717.86971349460455.117681174
1669642.86986348460455.1176811741669542.86973541460446.715138925
1669468.14055415460424.2745670061669381.16205357460398.101719094
#Sta/Elev= 30
       0  891.09    22.9  890.32      59  887.28    98.4  887.17   124.6  885.07
   137.7  883.04   170.6  873.64   190.3  867.19  212.74865.3909     243  864.71
   258.7865.4113   266.2  867.64   269.6  870.13   278.4   878.5   288.9  889.71
   296.8  896.65   300.4  896.89   303.9  895.98   307.5  896.72   317.6  907.68
   324.4  913.19   330.3  919.93   331.3  921.32   338.1  935.41   341.5   938.7
   364.5  950.74   372.4  957.24   392.9  970.52   406.6  977.91   431.7  988.89
#Mann= 5 ,-1,0
       0      .1       0    97.5     .07       0  212.74    .045       0
   258.7     .06       0  430.88      .1       0
Bank Sta=212.74,258.7
XS Rating Curve= 0 ,0
Exp/Cntr(USF)=0,0
Exp/Cntr=0.3,0.1

Type RM Length L Ch R = 1 ,23702   ,149.8,144.3,141.3
XS GIS Cut Line= 6
1669817.03785843460338.3224033421669729.53803343460338.322403342
1669654.53818342460338.3224033421669554.53805535460329.919861093
1669479.80887409460307.4792891741669392.83037351460281.306441262
#Sta/Elev= 30
       0  901.17     8.3  897.66    18.2  894.89      28   890.2    34.6  888.86
      51  888.83    80.5  886.22   106.8  883.15     133  878.68   162.5  878.39
   169.1  876.45     179  868.58  191.25864.9827   221.8  864.33   233.2864.9818
   247.2  868.78   264.7  877.25   278.4  885.12   285.2  887.44   305.8  890.03
   329.7  889.78   333.2  890.28   336.6  891.97     340  896.11   346.9  907.75
   360.6  921.61   370.4  937.39   374.3  941.13   405.1  959.34   431.7  971.67
#Mann= 3 ,-1,0
       0      .1       0  191.25    .045       0   233.2     .06       0
Bank Sta=191.25,233.2
XS Rating Curve= 0 ,0
Exp/Cntr(USF)=0,0
Exp/Cntr=0.3,0.1

Type RM Length L Ch R = 1 ,23557   ,195.7,197.8,200
XS GIS Cut Line= 6
1669829.11277458460179.5020809711669741.70940608460183.608371967
  1669666.791905460187.1280499781669566.90201291460191.820953974
1669491.98483992 460195.340631971669404.58114333460199.446922967
#Sta/Elev= 30
       0  911.51    56.6  900.55    89.4  891.57   102.5   886.8   112.4  878.91
   115.7  877.48   145.2  876.28   161.7   876.7   168.2  875.56   171.5  873.27
   178.1  865.85     181864.4879   191.2  863.12   217.5     863  246.26864.4862
   250.3   865.3   256.5  868.76   265.9  878.37   279.9  889.06   309.8  893.52
     339  894.89   352.2  894.59   355.4  896.06   358.7  898.62   375.1  915.46
   385.1  923.82   398.1  936.89   403.9   940.5   414.6     945     425  953.04
#Mann= 4 ,-1,0
       0      .1       0     181    .045       0  246.26      .1       0
   272.5     .06       0
Bank Sta=181,246.26
XS Rating Curve= 0 ,0
Exp/Cntr(USF)=0,0
Exp/Cntr=0.3,0.1

Type RM Length L Ch R = 1 ,23360   ,312.5,316.7,318.9
XS GIS Cut Line= 2
1669830.32395749459993.2252833291669392.39563425459991.337661246
#Sta/Elev= 30
       0  921.01    28.2  917.73      84  903.47    90.5  901.15    97.1  897.39
   116.8  895.04     120  893.42     143  877.39   152.9  874.63   172.5  873.89
   175.8  872.73   182.4  867.18  186.83864.3645   195.5  862.94     248  862.98
  265.11864.3652   284.1  867.87   297.2  868.63   300.5  870.21   310.3  877.06
   339.9   887.3   350.4  894.43   372.7  907.92   375.9  909.16   405.5     911
   408.8   912.8     419  922.83   428.4  930.27   431.7  932.62   437.9   934.9
#Mann= 4 ,-1,0
       0      .1       0  186.83    .045       0  265.11      .1       0
     300     .06       0
Bank Sta=186.83,265.11
XS Rating Curve= 0 ,0
Exp/Cntr(USF)=0,0
Exp/Cntr=0.3,0.1

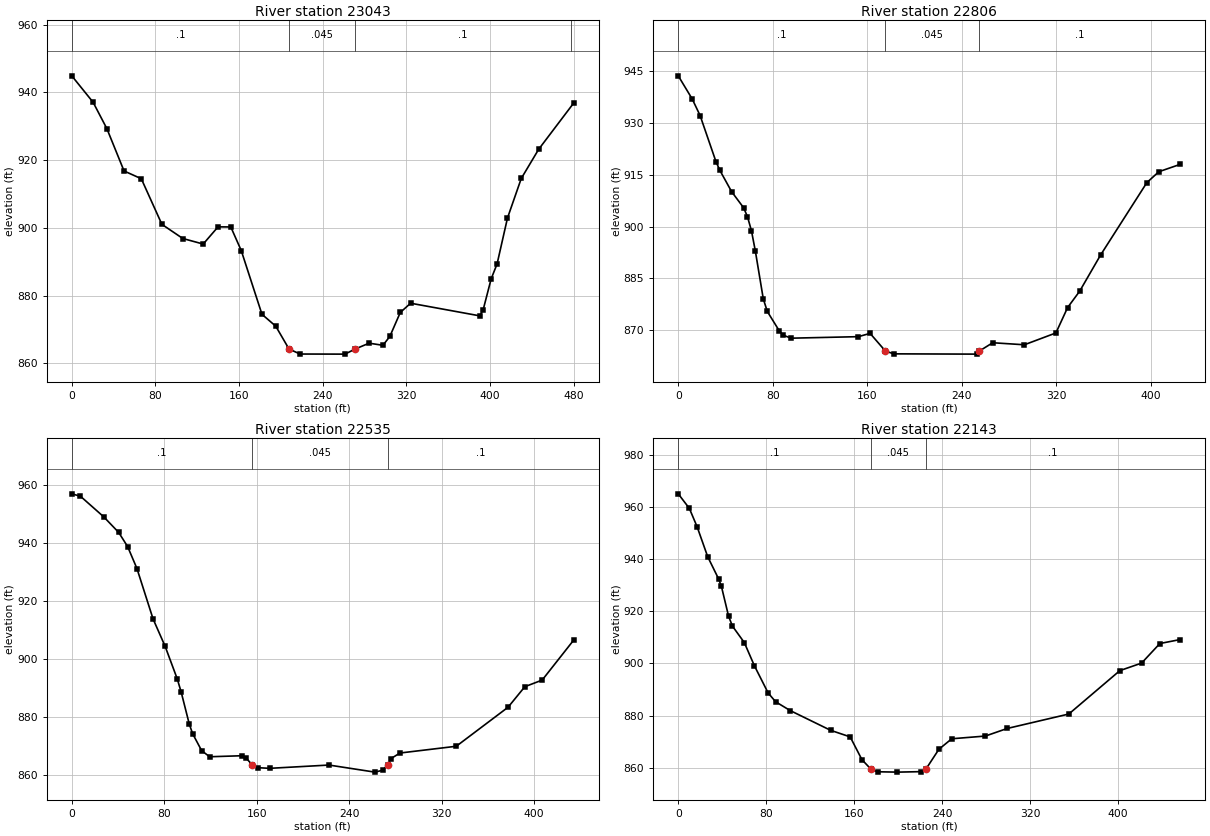
Type RM Length L Ch R = 1 ,23043   ,248.8,237.1,228.4
XS GIS Cut Line= 4
1669819.25218701459681.6328685941669688.75230127459691.205750064
 1669464.1252734 459662.891418821669342.22294918459678.602672025
#Sta/Elev= 30
       0  944.91    20.4   937.1    33.6  929.29      50   916.8    66.5  914.51
    86.2  901.03   106.2  896.85   125.7  895.21   139.9  900.29   152.1  900.26
   162.1  893.28   181.9  874.46   195.1  870.94  207.76864.2041   218.3  862.72
   261.3  862.69  271.07864.2034   284.4  865.92   297.6   865.3   304.2  867.91
   314.2     875   324.1  877.73   390.2     874   393.5  875.83   401.1  884.91
   406.8  889.36   416.7  902.87   429.9  914.58   446.5  923.18   480.2  936.93
#Mann= 4 ,-1,0
       0      .1       0  207.76    .045       0  271.07      .1       0
  477.26     .07       0
Bank Sta=207.76,271.07
XS Rating Curve= 0 ,0
Exp/Cntr(USF)=0,0
Exp/Cntr=0.3,0.1

Type RM Length L Ch R = 1 ,22806   ,279.5,271.1,263.9
XS GIS Cut Line= 6
1669748.05899376459400.6910765021669662.30325976 459418.07391575
1669588.79815742 459432.973492251669490.79146367 459452.83959426
1669417.28603326 459467.739170761669331.53029926459485.122010008
#Sta/Elev= 30
       0  943.71    11.8  937.02    18.5  932.21    31.9  918.88    35.2  916.34
    45.2  910.14    55.3   905.5    58.6  902.91      62  898.78    65.3  892.89
      72  879.07    75.4  875.43    85.4  869.89    88.8  868.57    95.5  867.69
   152.4  868.13   162.4  869.08  175.37863.9606   182.5  863.15   252.8  863.07
  254.89863.9633   266.2  866.37     293  865.78   319.7  869.21   329.6  876.57
   339.8   881.3   357.5  891.78   396.7  912.78   406.8  915.92     425  918.07
#Mann= 3 ,-1,0
       0      .1       0  175.37    .045       0  254.89      .1       0
Bank Sta=175.37,254.89
XS Rating Curve= 0 ,0
Exp/Cntr(USF)=0,0
Exp/Cntr=0.3,0.1

Type RM Length L Ch R = 1 ,22535   ,472.1,392.2,349.7
XS GIS Cut Line= 2
1669681.25612134459106.1627019151669272.96855208459254.082681666
#Sta/Elev= 30
       0  956.91     7.5  956.08    27.8  948.92    40.6  943.59    48.3  938.73
    56.4  931.12    70.3  913.79    80.8  904.28    91.3  893.02    94.7  888.46
   101.7  877.42   104.6  874.15   112.3  868.38   119.2  866.24   147.1  866.59
   150.6   865.9   155.9  863.52     161  862.47   171.2  862.25   222.5  863.38
   262.2  860.94   269.2  861.61   273.2  863.52   276.2  865.63   283.9  867.53
   332.6  869.86   377.4  883.32   391.9   890.4   406.9  892.68   434.3  906.54
#Mann= 3 ,-1,0
       0      .1       0   155.9    .045       0   273.2      .1       0
Bank Sta=155.9,273.2
XS Rating Curve= 0 ,0
Exp/Cntr(USF)=0,0
Exp/Cntr=0.3,0.1

Type RM Length L Ch R = 1 ,22143   ,221.3,213.9,206.9
XS GIS Cut Line= 6
1669126.57946985458830.1330442461669161.04692061458910.558408323
1669190.59082478458979.4946221591669228.73641778459071.942928079
 1669219.7042836459156.3374443231669205.00261401459264.645298573
#Sta/Elev= 30
       0  964.94    10.1  959.37    17.2  952.29    26.8  940.85    36.8  932.28
    39.3  929.45    45.8  918.06    49.3  914.27    60.1  907.97    69.3  899.06
    81.8  888.65    88.6  885.29   101.8  881.93   138.6  874.36   156.4  871.84
   167.1  863.11  175.35859.4543   181.3  858.48   199.4  858.34   220.4  858.52
  225.24 859.452   237.1  867.09   248.8  871.12   279.4  872.16   299.2  875.06
   355.3   880.6   401.7  897.22   421.5  900.11   438.1   907.6   456.7  909.13
#Mann= 3 ,-1,0
       0      .1       0  175.35    .045       0  225.24      .1       0
Bank Sta=175.35,225.24
XS Rating Curve= 0 ,0
Exp/Cntr(USF)=0,0
Exp/Cntr=0.3,0.1