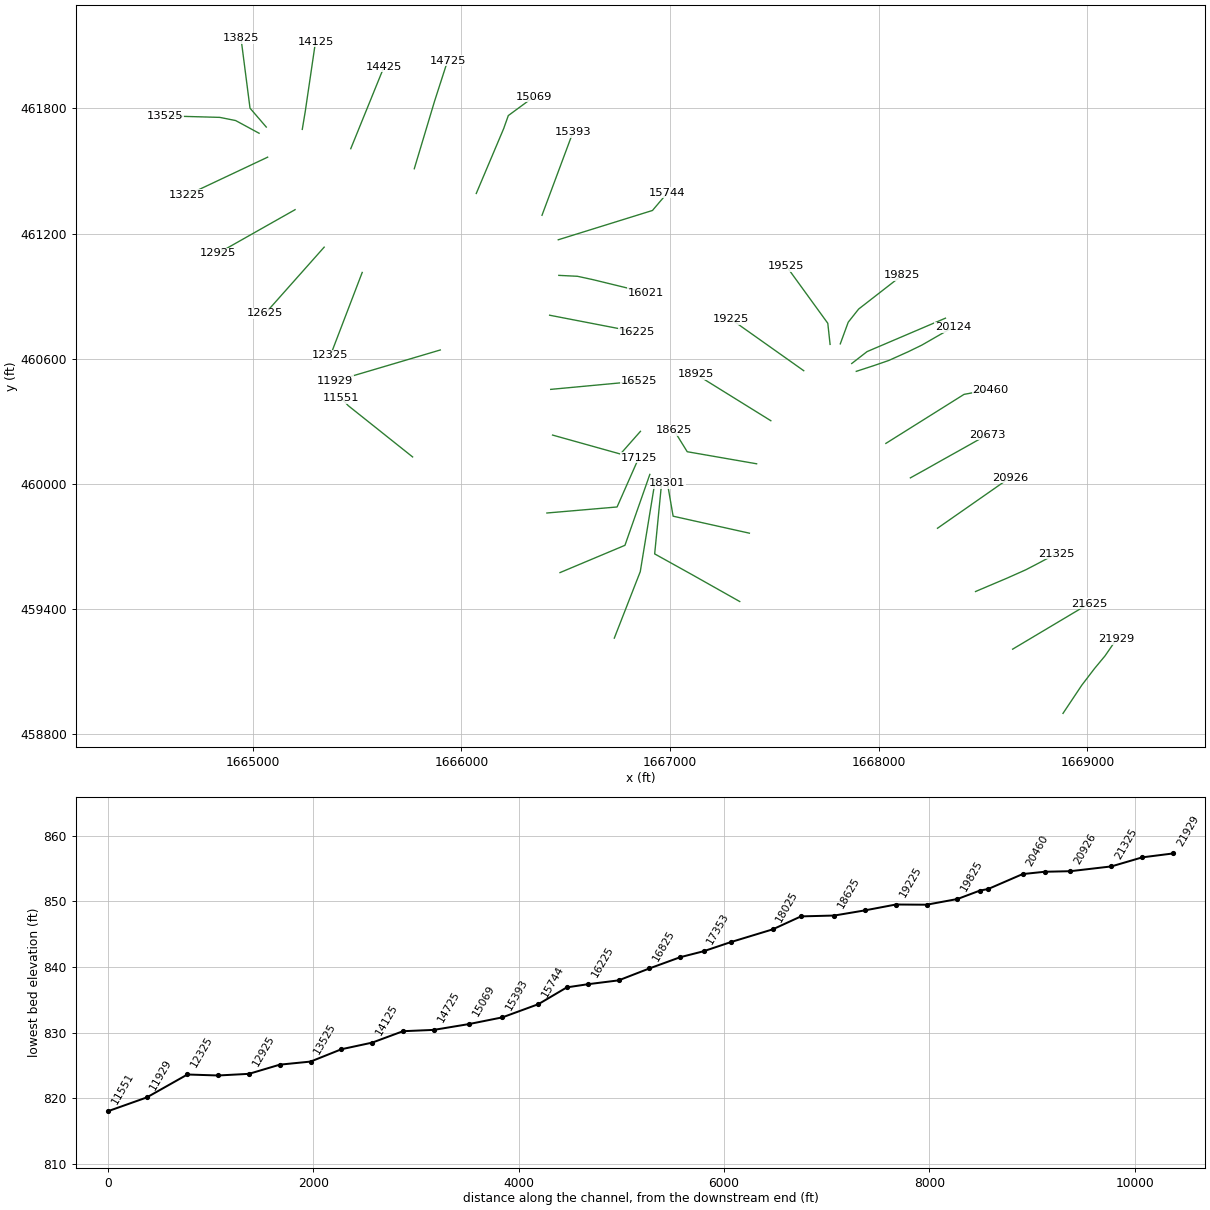
HEC-RAS study PenFrkFshCk.prj: PenFrkFshCk

--- PenFrkFshCk.g01 (geometry) --- (continued)

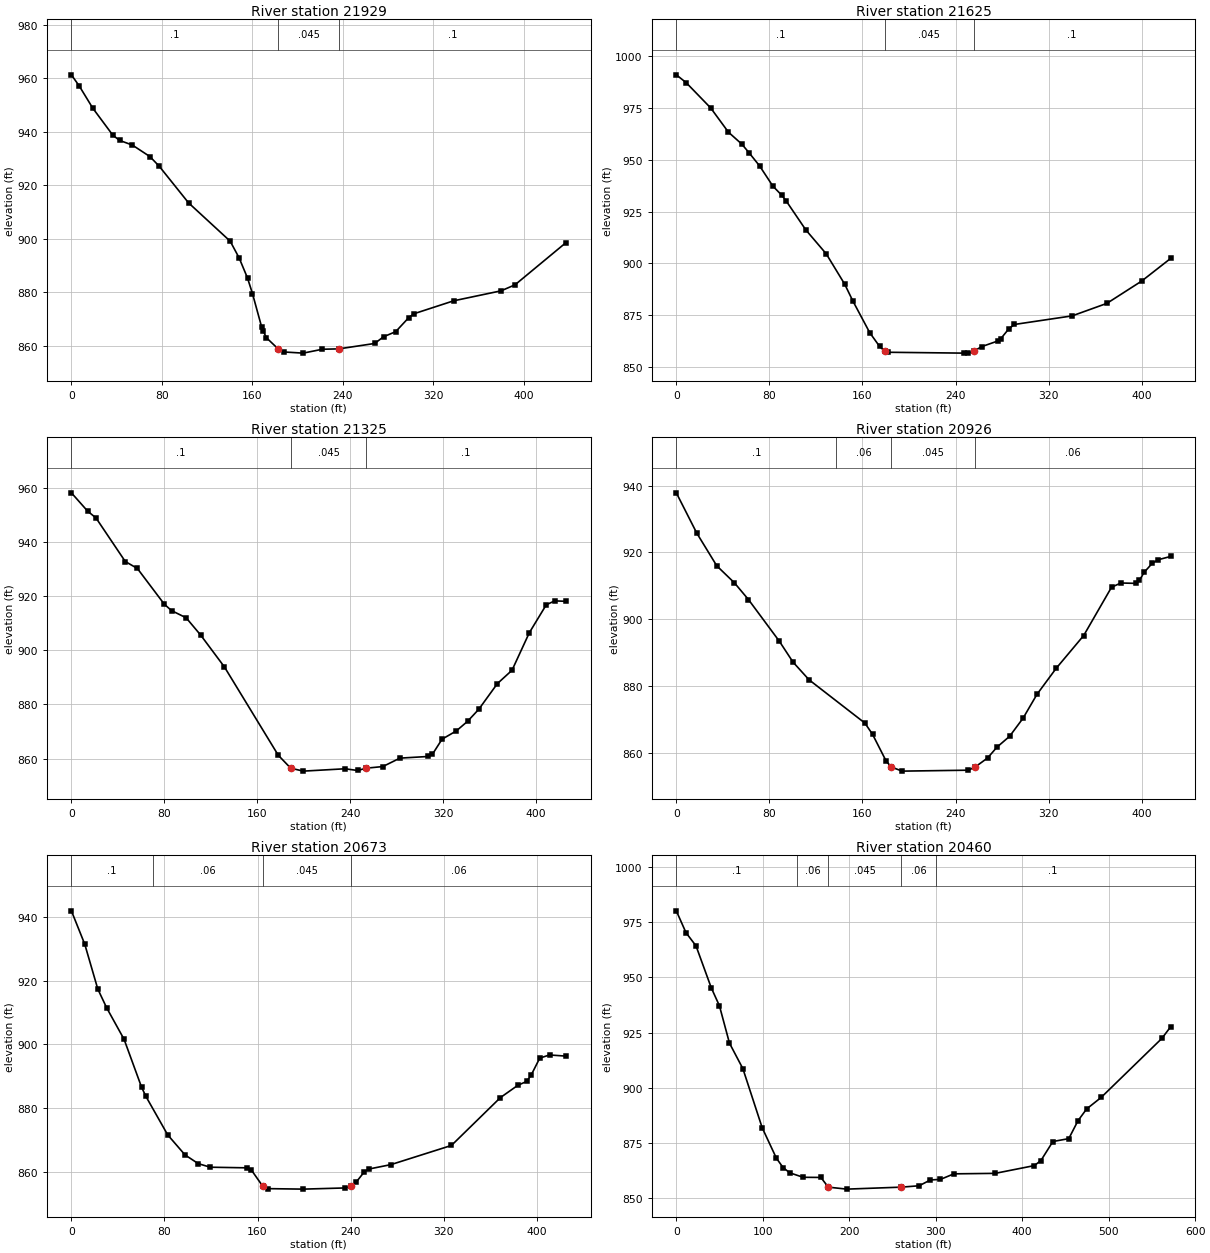
Type RM Length L Ch R = 1 ,21929   ,313.6,303.2,291.2
XS GIS Cut Line= 6
1668882.88159026458899.7773801681668931.41758242458972.582024589
1668973.01986143459034.9860992581669033.81567159 459114.64046751
1669084.41990109459175.6797154991669138.38534434459254.006986678
#Sta/Elev= 30
       0  961.34     7.1  957.07    18.9  948.89    36.6   938.8    42.6  936.83
    53.9  935.09    69.4  930.79    77.6   927.2   103.6  913.48   140.4  899.15
   148.3  892.91   155.7   885.4   160.1  879.57   168.2  867.09   169.8  865.41
   172.4  863.08  182.77858.9105     188  857.75   204.9  857.32   221.9  858.77
  236.45858.9108   268.1  860.93     276  863.44   286.7  865.34   298.3  870.61
     303  872.06     338  876.88   379.9  880.61   392.2  882.85   437.1  898.57
#Mann= 3 ,-1,0
       0      .1       0  182.77    .045       0  236.45      .1       0
Bank Sta=182.77,236.45
XS Rating Curve= 0 ,0
Exp/Cntr(USF)=0,0
Exp/Cntr=0.3,0.1

Type RM Length L Ch R = 1 ,21625   ,303.3,300.9,295.9
XS GIS Cut Line= 6
1668641.60254526459207.6543890831668716.76053143459252.460073754
1668781.18133435459290.8651806711668867.07617567459342.071771175
 1668931.4969786459380.4762219191669006.65496476 459425.28190659
#Sta/Elev= 30
       0  990.94     8.4  987.21    29.6  974.94    44.8  963.29    56.3  957.53
    62.5  953.38    71.6  947.01      83  937.28    90.7  932.83    94.5  930.08
   111.3  916.17   128.9  904.59   144.8  889.92   151.8  881.83   166.3  866.57
   174.7  859.99  179.12857.6584   182.3  857.13   247.3  856.72   251.1  856.74
  255.66 857.658   262.5  859.85   276.4  862.58   278.8   863.6     286  868.56
   290.7  870.55   340.3  874.69   370.1  880.71   400.1   891.5     425  902.42
#Mann= 3 ,-1,0
       0      .1       0  179.12    .045       0  255.66      .1       0
Bank Sta=179.12,255.66
XS Rating Curve= 0 ,0
Exp/Cntr(USF)=0,0
Exp/Cntr=0.3,0.1

Type RM Length L Ch R = 1 ,21325   ,393.6,398.7,406.4
XS GIS Cut Line= 6
1668463.77284843  459484.00193351668544.32386842459518.175093502
1668613.36736551459547.4663735031668704.74087043459588.135911584
1668771.45431967459622.9193065911668848.85311501459664.522897929
#Sta/Elev= 30
       0  958.17      14   951.4    21.2  948.88    46.4  932.79    56.8  930.22
      80  917.01    86.2  914.66    98.8  911.99   111.3   905.6   131.7  893.86
   178.1   861.2  188.79 856.434   199.6  855.34   235.6  856.21   246.3  855.58
  253.99856.4354   268.1  857.03   282.8  860.14     307  860.75   310.7  861.51
   319.1  867.15   331.3  870.18     341  873.73   350.7  878.19   366.7  887.68
   379.3  892.61   394.2  906.48   408.8  916.81   416.1  918.25   425.6  918.08
#Mann= 3 ,-1,0
       0      .1       0  188.79    .045       0  253.99      .1       0
Bank Sta=188.79,253.99
XS Rating Curve= 0 ,0
Exp/Cntr(USF)=0,0
Exp/Cntr=0.3,0.1

Type RM Length L Ch R = 1 ,20926   ,256.4,253,249
XS GIS Cut Line= 6
 1668281.4708916459787.3170459881668353.22173236 459837.39765449
1668414.72259361459880.3237497371668496.72341386459937.558871494
1668558.22427511 459980.485294821668629.97511586460030.565903322
#Sta/Elev= 30
       0  937.82    17.6  925.77    34.8  915.99      50  910.89      62  905.92
    88.6  893.43   100.3  887.22   114.1  881.92   162.1  868.98   168.7  865.61
   180.4   857.6  184.89855.8378   194.1  854.61   251.1  854.89  256.89855.8397
   267.6  858.55   275.6  861.76   286.5  865.02   298.1  870.45     310  877.55
   326.5  885.33   350.2  895.16   374.1  909.58   382.1  910.86   394.9  910.75
   398.1  911.63   402.1  914.03     409   916.7   414.1  917.81     425   918.8
#Mann= 4 ,-1,0
       0      .1       0   137.5     .06       0  184.89    .045       0
  256.89     .06       0
Bank Sta=184.89,256.89
XS Rating Curve= 0 ,0
Exp/Cntr(USF)=0,0
Exp/Cntr=0.3,0.1

Type RM Length L Ch R = 1 ,20673   ,210.8,212.9,214.8
XS GIS Cut Line= 6
1668151.69625717460028.8604427481668228.19774459460071.328205576
1668293.47615734460108.2228168311668380.76764943 460157.01274549
1668446.19140309460193.718708834 1668522.4448595460236.680565154
#Sta/Elev= 30
       0  941.91    11.5  931.42    22.7  917.35    30.3  911.47    45.3  901.56
    60.3  886.56      64  883.67    82.8  871.55    97.7  865.26   109.1  862.52
   119.4   861.4   150.7  861.21   154.4  860.68  164.32855.5256   169.4  854.67
   199.5  854.52   235.1  854.89  240.48 855.526   244.6  856.62   251.9     860
   255.9  860.84   274.7  862.22   326.7  868.24   368.8  883.27   383.8  887.13
   391.3  888.33   395.1  890.24   402.6  895.66     411  896.65     425  896.29
#Mann= 4 ,-1,0
       0      .1       0      70     .06       0  164.32    .045       0
  240.48     .06       0
Bank Sta=164.32,240.48
XS Rating Curve= 0 ,0
Exp/Cntr(USF)=0,0
Exp/Cntr=0.3,0.1

Type RM Length L Ch R = 1 ,20460   ,342,336.1,327.9
XS GIS Cut Line= 3
1668034.17265776460194.0785973371668408.94452906 460429.26598448
1668536.17490529 460452.36456259
#Sta/Elev= 30
       0  980.19    11.2   970.3    22.8  964.31    40.4  945.37    49.9  937.16
    61.5  920.26      77  908.72    99.3  881.99   115.8  868.14   123.5  863.94
   131.2  861.56   146.7  859.53   167.2  859.46  175.76855.0714   197.1  854.17
  260.44855.0711   280.8  855.69   293.9  858.33   305.5  858.58     321  861.09
   368.8  861.31   414.1  864.83   421.7  867.13   435.5  875.72   453.9  877.04
   464.6  885.18   474.6  890.49   491.3  895.67   561.6  922.43   571.8  927.72
#Mann= 5 ,-1,0
       0      .1       0     140     .06       0  175.76    .045       0
  260.44     .06       0     300      .1       0
Bank Sta=175.76,260.44
XS Rating Curve= 0 ,0
Exp/Cntr(USF)=0,0
Exp/Cntr=0.3,0.1

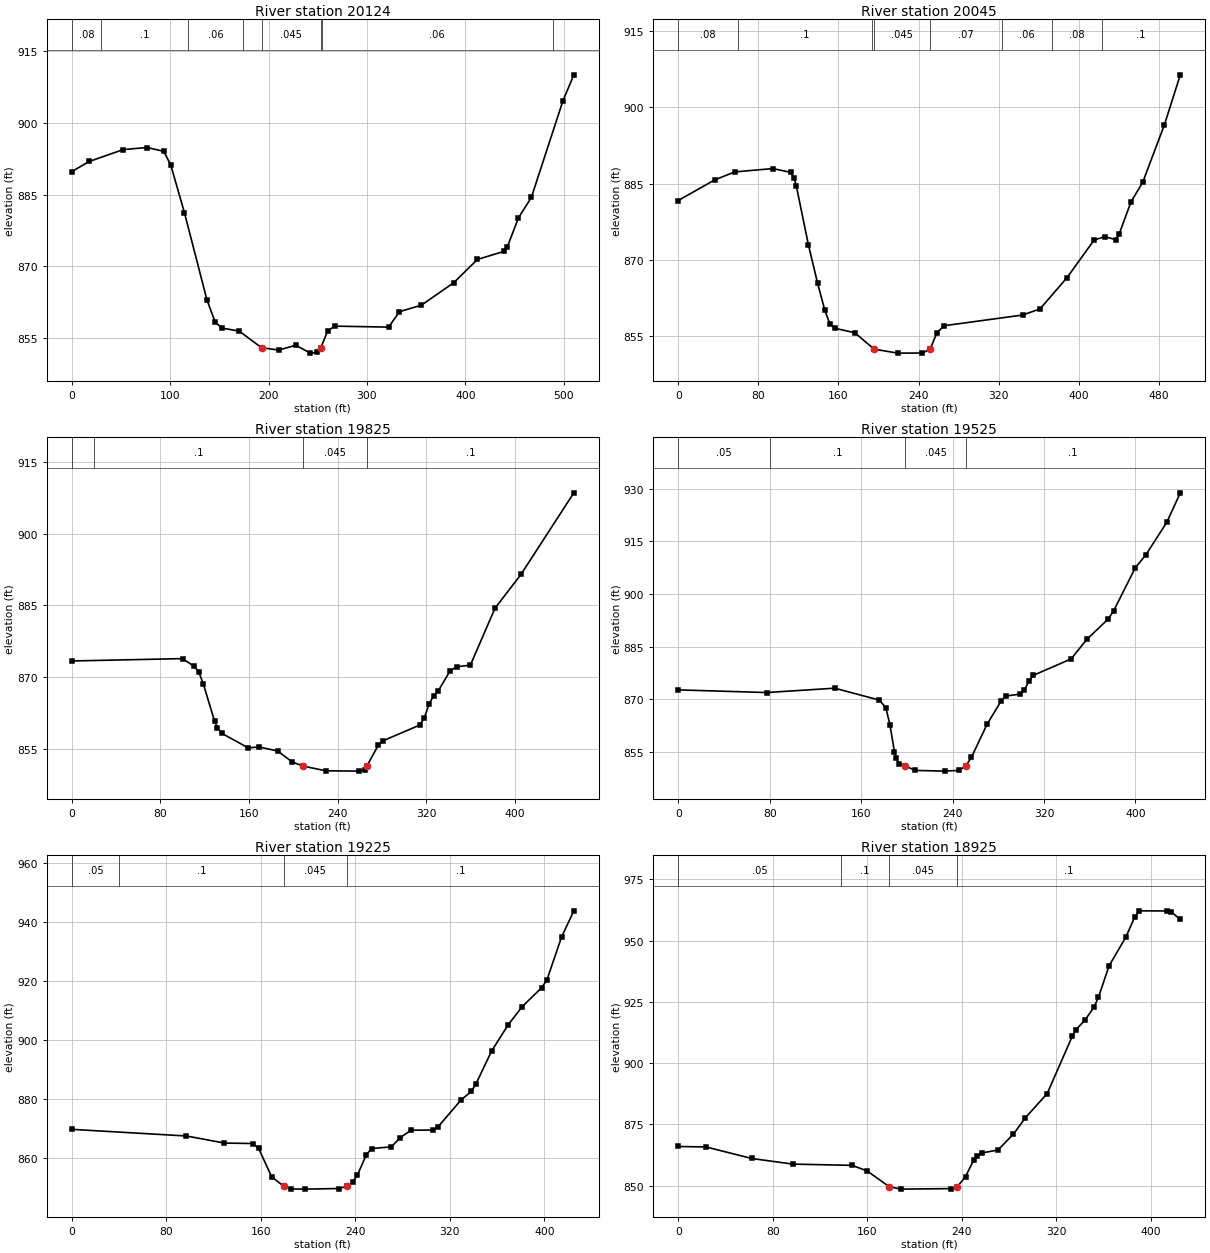
Type RM Length L Ch R = 1 ,20124   ,79.5,79.1,78.8
XS GIS Cut Line= 6
1667892.30483125460539.4811217491667976.27349535460566.885922596
1668047.69067533460591.5197315961668138.97330117460632.470109001
1668206.42592217460665.2597415891668354.96266374460750.704482245
#Sta/Elev= 30
       0  889.83    17.7  891.95    52.2  894.43    76.4  894.87    93.5  894.07
   100.6  891.21   114.5  881.26   137.3  863.08   145.7  858.38   152.6  857.13
   170.2  856.49  192.85  853.03   210.3  852.53   227.6  853.53   242.6  851.89
   249.3  852.04  253.19853.0322   260.1  856.55   267.4  857.53   322.1  857.33
     333  860.55   355.4  861.92   388.1  866.59   412.3  871.47   439.5  873.17
   442.6  874.04   453.9  880.13   467.1  884.43   499.3  904.68   510.3  910.06
#Mann= 8 ,-1,0
       0     .08       0      30      .1       0  118.33     .06       0
  173.87     .07       0  192.85    .045       0  253.19     .07       0
  253.87     .06       0  488.92      .1       0
Bank Sta=192.85,253.19
XS Rating Curve= 0 ,0
Exp/Cntr(USF)=0,0
Exp/Cntr=0.3,0.1

Type RM Length L Ch R = 1 ,20045   ,212.6,219.4,227.1
XS GIS Cut Line= 3
1667870.51476933460577.0347419811667944.08030075460634.130378302
1668319.59390886460794.437357204
#Sta/Elev= 30
       0  881.68    36.4  885.73    56.4   887.3    94.4  887.96   112.2  887.22
   115.8  886.07   117.9  884.57     130  872.97   139.1  865.45   146.4  860.09
   151.4  857.43   156.4  856.55   176.4  855.66  195.58852.4431   219.2  851.66
   243.9  851.68   251.6  852.45   258.4   855.7   265.6  857.05   344.1  859.16
   361.4  860.37   388.1  866.47   415.4  873.93   426.1  874.56   436.8  873.99
   440.4  875.13   452.1  881.38   463.9  885.28   485.6  896.62   501.4   906.4
#Mann= 8 ,-1,0
       0     .08       0      60      .1       0  193.12     .07       0
  195.58    .045       0   251.6     .07       0  323.12     .06       0
  373.12     .08       0  423.12      .1       0
Bank Sta=195.58,251.6
XS Rating Curve= 0 ,0
Exp/Cntr(USF)=0,0
Exp/Cntr=0.3,0.1

Type RM Length L Ch R = 1 ,19825   ,249.4,300,336.3
XS GIS Cut Line= 6
1667815.74461693460671.2915536761667853.67433108460775.024942011
1667903.66373242460838.1147108381667982.59927009460899.508616924
1668041.80059525460945.5538004191668110.86902668460999.273509249
#Sta/Elev= 30
       0  873.38     100  873.87   110.5  872.26   114.7  871.06   118.9  868.53
   128.9  860.84   131.5  859.42   135.6  858.25   159.3  855.23   169.1  855.42
   185.9  854.57     199   852.3  208.64851.4335   229.4  850.44   259.3  850.37
   264.4  850.68  266.53851.4343   276.8  855.78   280.8  856.68   314.2  859.99
   318.4  861.49   322.5  864.29   326.7  866.13   330.9  867.11   341.6  871.29
   347.5  872.16     360  872.52   382.2   884.4   405.7  891.47   453.4   908.5
#Mann= 4 ,-1,0
       0     .05       0      20      .1       0  208.64    .045       0
  266.53      .1       0
Bank Sta=208.64,266.53
XS Rating Curve= 0 ,0
Exp/Cntr(USF)=0,0
Exp/Cntr=0.3,0.1

Type RM Length L Ch R = 1 ,19525   ,289.6,300,307.1
XS GIS Cut Line= 6
1667766.83165701460668.7249577491667755.84873934460769.891422093
1667711.82586151460830.612101167 1667653.1291285460911.573225334
1667609.10657875460972.2942325031667557.74677335461043.134970084
#Sta/Elev= 30
       0  872.67    77.3  871.91   136.9  873.15     176  869.75   181.6  867.61
   185.2  862.79   189.2  854.96   190.7  853.29   193.3   851.5  198.68850.9954
   207.2  849.71     233   849.5     246  849.72   251.6850.9934   256.5  853.41
   270.3  862.91   282.4  869.43   286.5  870.91     299  871.45   302.7  872.52
   306.7  875.08   310.8  876.83   343.7  881.49   357.5  887.06   376.3  892.91
     381  895.24   399.9  907.48   409.2  911.19   427.5  920.49   439.3  928.86
#Mann= 4 ,-1,0
       0     .05       0      80      .1       0  198.68    .045       0
   251.6      .1       0
Bank Sta=198.68,251.6
XS Rating Curve= 0 ,0
Exp/Cntr(USF)=0,0
Exp/Cntr=0.3,0.1

Type RM Length L Ch R = 1 ,19225   ,297.9,300,301.3
XS GIS Cut Line= 6
 1667640.5189175460542.6330183451667569.11682934460593.209360749
1667507.91485201460636.5606520031667426.31232493460694.362373665
1667365.11067568460737.7136649191667293.70858751460788.290335417
#Sta/Elev= 30
       0  869.81      97  867.56   129.2  865.16   153.3     865   158.1   863.4
   169.2  853.72  179.37 850.526   185.5  849.59   197.6  849.53   226.2  849.74
  233.07850.5261   237.7  851.94   241.7  854.21   249.4  861.25   253.8  863.28
   270.6  863.89   277.9  866.95   287.1  869.51   306.1  869.58   310.1  870.69
   329.4  879.73   338.2  882.66   342.3  885.36   355.3  896.32   369.4  905.27
   381.2  911.41   397.7  917.83   402.2   920.5   414.6  935.06     425  943.94
#Mann= 4 ,-1,0
       0     .05       0      40      .1       0  179.37    .045       0
  233.07      .1       0
Bank Sta=179.37,233.07
XS Rating Curve= 0 ,0
Exp/Cntr(USF)=0,0
Exp/Cntr=0.3,0.1

Type RM Length L Ch R = 1 ,18925   ,286.2,300,309.1
XS GIS Cut Line= 6
1667482.99987559460302.7873694151667408.65652034460348.931634083
1667344.93355067460388.4840484261667259.96948175 460441.22016342
1667196.24651209460480.7722496691667121.90282875460526.916514337
#Sta/Elev= 30
       0  866.03    23.6  865.83    62.1  861.14      97  858.84   147.2  858.33
   159.8  856.08  178.61849.6361   188.4  848.64   231.3  848.85  236.27849.6335
   243.2  853.77   250.3  860.65   252.7  862.16   257.5  863.42   270.7   864.6
   283.7  871.04   293.9  877.76   312.3  887.58   333.7  911.13   336.4  913.52
   344.1  917.44   351.8  922.69   355.7  926.82   364.7  939.69   378.9  951.39
   386.6  959.73   390.4   962.1   413.6  962.04   417.5  961.52     425  958.67
#Mann= 4 ,-1,0
       0     .05       0   137.5      .1       0  178.61    .045       0
  236.27      .1       0
Bank Sta=178.61,236.27
XS Rating Curve= 0 ,0
Exp/Cntr(USF)=0,0
Exp/Cntr=0.3,0.1

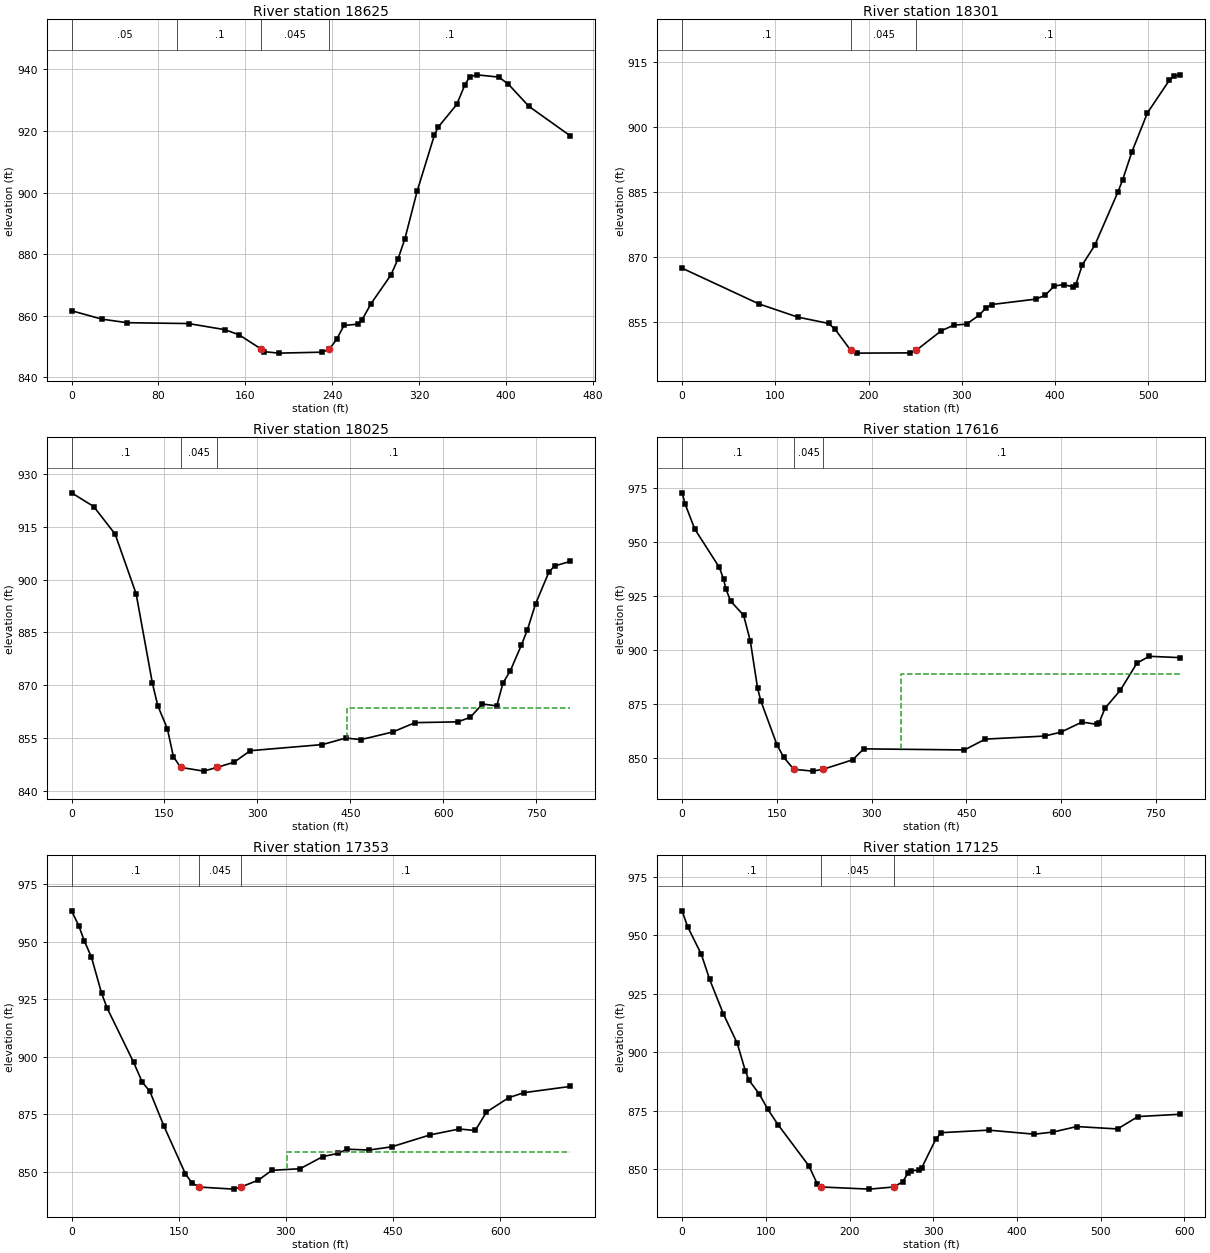
Type RM Length L Ch R = 1 ,18625   ,326.1,324.4,322.6
XS GIS Cut Line= 6
1667414.81858151460096.3442127561667328.61271717460111.336636841
1667254.72178884460124.1873329281667156.20066042460141.321156919
1667082.30973209460154.1718530061667018.34299651460257.530898258
#Sta/Elev= 30
       0  861.61    27.8  858.89    51.1  857.73   107.7  857.45     141  855.48
   154.3   853.8   174.8849.1367   177.6  848.31   190.9  847.85   230.9  848.16
  237.45849.1371   244.2  852.38   250.9  856.83   264.2  857.28   267.5  858.62
   275.9  863.95   294.2  873.24   300.8  878.54     307  884.95   318.3  900.42
   334.1  918.53   337.5  921.15   354.8  928.59   362.3  934.98   366.7  937.54
   373.2  938.21   393.5  937.48   402.4  935.16   421.2  927.99   459.1  918.47
#Mann= 4 ,-1,0
       0     .05       0    97.5      .1       0   174.8    .045       0
  237.45      .1       0
Bank Sta=174.8,237.45
XS Rating Curve= 0 ,0
Exp/Cntr(USF)=0,0
Exp/Cntr=0.3,0.1

Type RM Length L Ch R = 1 ,18301   ,284.6,275.6,269.7
XS GIS Cut Line= 3
1667380.19430692459763.6539466041667014.72809094459845.045491998
1666987.38377309460002.923747368
#Sta/Elev= 30
       0  867.35    82.7  859.07   123.9  856.05   157.2  854.58     164  853.26
  180.97848.3403   187.5  847.72   244.6  847.78  250.98848.3395   278.2  852.92
   291.7  854.19   305.1  854.42   318.6  856.49   326.4  858.26     332  858.95
   379.3   860.2   389.3  861.07   399.3  863.24   409.3  863.56   419.3  863.03
   422.3   863.5   429.3  868.14   442.6  872.62   467.7  885.06   472.6  887.81
   482.6   894.3   499.2  903.26   522.5  910.73   527.8  911.74   534.6  912.03
#Mann= 3 ,-1,0
       0      .1       0  180.97    .045       0  250.98      .1       0
Bank Sta=180.97,250.98
XS Rating Curve= 0 ,0
Exp/Cntr(USF)=0,0
Exp/Cntr=0.3,0.1

Type RM Length L Ch R = 1 ,18025   ,449.7,409.9,373.7
XS GIS Cut Line= 6
1667333.88075125  459436.02565151667257.65518193459478.989476338
1667192.31869842459515.8155181711667105.20371518   459564.917126
1666926.28837428 459664.316498651666959.20853843460000.333841588
#Sta/Elev= 30
       0  924.55    35.7  920.67    70.3  912.86   104.2  895.97   130.5  870.63
   139.2  864.26   154.7  857.72   164.4  849.85  176.02846.8071   213.4  845.74
     235846.8075   262.4  848.26   288.6  851.53     405  853.26     443  855.11
   467.2  854.66   518.5  856.82   554.7  859.47     624  859.69   643.8     861
   663.5  864.75   686.6  864.21   696.5  870.65   708.4  874.14   726.2  881.38
   736.1   885.8   749.2  893.09   770.8  902.13   779.8  903.82   804.8  905.12
#Mann= 3 ,-1,0
       0      .1       0  176.02    .045       0     235      .1       0
#XS Ineff= 2 , 0
                          445.22          863.71
Permanent Ineff=
       F       F
Bank Sta=176.02,235
XS Rating Curve= 0 ,0
Exp/Cntr(USF)=0,0
Exp/Cntr=0.3,0.1

Type RM Length L Ch R = 1 ,17616   ,279,262.1,240.1
XS GIS Cut Line= 3
1666732.83048162459260.4945039151666857.34041137459579.408268409
1666929.45361217460020.171091156
#Sta/Elev= 30
       0  972.91     4.9  967.67    19.9  956.17      59   938.3    65.7  932.86
    69.2  928.38      77  922.62    97.4   916.1     108  904.15   119.5  882.28
   124.6  876.42   150.2  855.99   160.8  850.25  176.74844.6526   206.6  843.79
  223.31844.6537     270  849.03   287.6  854.12   446.9  853.62   480.1  858.64
   573.9  860.06   599.6  861.87   633.1  866.55   656.7  865.49   659.7  865.95
   669.6  873.02   693.9  881.37     720  893.89   739.4  897.06     789  896.44
#Mann= 3 ,-1,0
       0      .1       0  176.74    .045       0  223.31      .1       0
#XS Ineff= 2 , 0
                          347.31          888.68
Permanent Ineff=
       F       F
Bank Sta=176.74,223.31
XS Rating Curve= 0 ,0
Exp/Cntr(USF)=0,0
Exp/Cntr=0.3,0.1

Type RM Length L Ch R = 1 ,17353   ,239.4,228,218.1
XS GIS Cut Line= 6
1666472.79656918459574.7162841531666553.46110601459608.640756993
1666622.60827743459637.7079560731666714.78591459459676.418508573
1666783.92094693459705.4939097441666903.12580142460045.461470159
#Sta/Elev= 30
       0  963.38      10  956.92    17.9  950.25    27.8  943.24      42  927.55
    49.7  921.15    86.9  897.49    98.9  888.94   109.6  884.91   129.5  869.65
   159.4  849.04   168.2  845.23  178.32843.3181     227  842.41  236.94 843.318
   261.5  846.32   280.4  850.58   319.9  851.28   351.5  856.52   372.3  857.91
   386.2  859.77   416.5   859.4   448.1   860.8   502.2     866   542.7  868.54
   565.2   867.9   580.9  875.93   612.2  882.19   633.5  884.35   697.8  887.03
#Mann= 3 ,-1,0
       0      .1       0  178.32    .045       0  236.94      .1       0
#XS Ineff= 2 , 0
                          301.23          858.58
Permanent Ineff=
       F       F
Bank Sta=178.32,236.94
XS Rating Curve= 0 ,0
Exp/Cntr(USF)=0,0
Exp/Cntr=0.3,0.1

Type RM Length L Ch R = 1 ,17125   ,314.7,300,286.7
XS GIS Cut Line= 6
1666409.88620818459860.3551834231666497.06385534459867.860417753
1666571.78745918459874.2931476681666671.41882159459882.870886415
1666746.14242542459889.3039444241666850.25934318460125.097108006
#Sta/Elev= 30
       0  960.35     6.5  953.64      23  941.77    32.8  931.15    49.3  916.32
    65.8  903.84    75.6  891.94    79.8  888.04    92.1  882.17   102.4  875.59
   114.6  869.02   151.4  851.44   161.3  843.89  166.31842.4131   223.8   841.5
  252.81842.4131   263.3   844.6   269.9  848.31   273.2  849.37   283.1  849.58
   286.4  850.73   302.9  862.72   309.4  865.61   366.2  866.69   420.8  864.96
   443.2  865.89   471.4  868.22   520.1   867.2   544.5  872.49   595.3  873.48
#Mann= 3 ,-1,0
       0      .1       0  166.31    .045       0  252.81      .1       0
Bank Sta=166.31,252.81
XS Rating Curve= 0 ,0
Exp/Cntr(USF)=0,0
Exp/Cntr=0.3,0.1

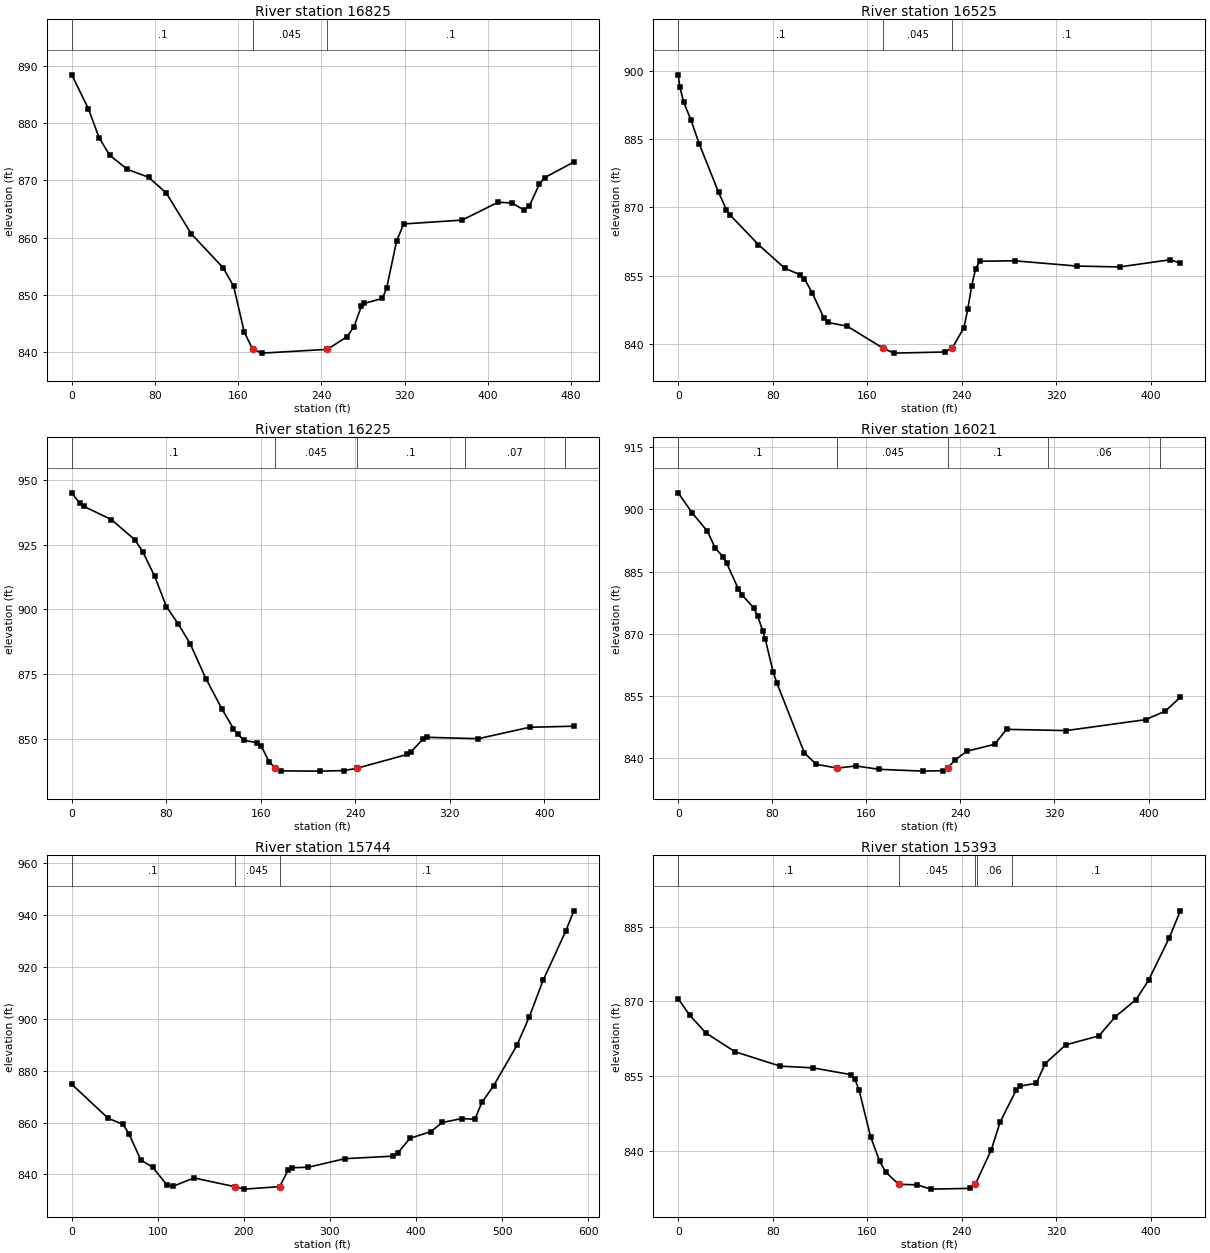
Type RM Length L Ch R = 1 ,16825   ,285.1,300,311.4
XS GIS Cut Line= 6
1666437.08792542460233.9646724161666521.35809809460210.410913751
1666593.58958092460190.2216496771666689.89844343460163.303396419
1666762.13025434460143.1144604241666858.25309359460252.002366006
#Sta/Elev= 30
       0  888.48    15.9  882.58    26.2  877.51    36.4  874.43    53.4  871.94
    73.9  870.56    90.9  867.79   114.7   860.7   145.4  854.75   155.6  851.51
   165.8  843.48  174.03840.4485   182.9  839.79  245.84840.4493   264.6  842.67
   271.4  844.43   278.3  847.95   281.1  848.48   298.7  849.37   302.8  851.23
   312.3   859.4   319.1  862.39   375.2  863.06   409.9  866.19   423.4  866.05
   434.7  864.83   439.7  865.46   449.6  869.36   454.5  870.48   482.7  873.23
#Mann= 3 ,-1,0
       0      .1       0  174.03    .045       0  245.84      .1       0
Bank Sta=174.03,245.84
XS Rating Curve= 0 ,0
Exp/Cntr(USF)=0,0
Exp/Cntr=0.3,0.1

Type RM Length L Ch R = 1 ,16525   ,310.4,300,291.7
XS GIS Cut Line= 6
1666428.20014793460453.0488799211666515.32005243460461.196829513
1666589.99411568460468.1810675111666689.55953334460477.493056759
1666764.23359659460484.477294758 1666851.3535011460492.625244334
#Sta/Elev= 30
       0  899.09     1.3  896.45     4.6  893.09    10.7  889.22    17.8   883.9
    34.2  873.25    40.8  869.47    44.1  868.25    67.9  861.79    90.3  856.59
   103.4  855.18   106.7  854.35   113.3  851.28   123.2  845.73   126.5  844.71
     143  843.89  173.35839.0656   182.4  837.97   225.4  838.22  231.97839.0657
   241.8  843.57   245.1  847.61   248.4  852.71   251.7  856.51   255.3  858.15
   284.7  858.25   337.4  857.09   373.6   856.9   416.5  858.48     425  857.71
#Mann= 3 ,-1,0
       0      .1       0  173.35    .045       0  231.97      .1       0
Bank Sta=173.35,231.97
XS Rating Curve= 0 ,0
Exp/Cntr(USF)=0,0
Exp/Cntr=0.3,0.1

Type RM Length L Ch R = 1 ,16225   ,210.1,204.7,204
XS GIS Cut Line= 6
 1666422.9842791460808.5701505091666508.89355609460791.961587921
1666582.52989176460777.7253959181666680.71211009460758.743806586
1666754.34844576460744.5076145831666840.25772275460727.898723915
#Sta/Elev= 30
       0  945.15     6.6  941.17      10  939.96    33.4  934.82    53.4  926.99
    60.1  922.32    70.1  912.95    80.1  901.08      90  894.48   100.2  886.72
   113.5  873.24   126.9  861.61   136.9   853.8   140.3  851.66   146.1  849.28
     157  848.35   160.3  847.15     167  841.05  172.45838.4579     177  837.47
   210.5  837.38   230.5   837.6  241.12838.4597     284  843.85   287.3  844.89
   297.3  849.84   300.7  850.48   344.1  849.94   387.6  854.37     425  854.77
#Mann= 5 ,-1,0
       0      .1       0  172.45    .045       0  241.12      .1       0
   332.5     .07       0   417.5      .1       0
Bank Sta=172.45,241.12
XS Rating Curve= 0 ,0
Exp/Cntr(USF)=0,0
Exp/Cntr=0.3,0.1

Type RM Length L Ch R = 1 ,16021   ,254.2,277,288.7
XS GIS Cut Line= 6
1666467.02985918460999.6463112741666556.36629469460995.200125939
 1666629.6945601 460979.33171936 1666726.8479091460955.641806117
1666799.71292085460937.8741251141666884.72226527460917.145163945
#Sta/Elev= 30
       0  903.97    11.7  899.19    24.8  894.72    31.4  890.69      38  888.59
    41.2  887.04    51.1  880.79    54.4  879.32    64.2  876.27    67.5  874.32
      72  870.62    74.1  868.63    80.7  860.81    83.9  858.14   107.3  841.28
   117.4  838.54  135.33837.6345     151  838.15   171.1  837.33   207.9   836.9
   225.2  837.01  229.09837.6357   235.3  839.56   245.4   841.7   269.1  843.37
   279.2  846.97   329.9  846.67   397.4   849.3   414.3  851.37     427   854.7
#Mann= 5 ,-1,0
       0      .1       0  135.33    .045       0  229.09      .1       0
  314.47     .06       0  409.47      .1       0
Bank Sta=135.33,229.09
XS Rating Curve= 0 ,0
Exp/Cntr(USF)=0,0
Exp/Cntr=0.3,0.1

Type RM Length L Ch R = 1 ,15744   ,317.2,350.3,372.3
XS GIS Cut Line= 3
1666464.47048925461170.3217584371666915.83546148461310.785497196
1666987.36846106461395.251362187
#Sta/Elev= 30
       0  874.74    42.4  861.59    59.6  859.33    66.4  855.68    80.2  845.56
    93.9  842.82   111.1  835.75     118  835.48     142  838.65  189.26835.2938
   200.4  834.34  241.61835.2929   251.2  841.57   255.4  842.59   274.8  842.77
   317.3  846.07   373.2  847.05   379.1  848.39   392.9  853.92   416.9  856.46
   430.7  860.03     453  861.52   468.4  861.27   476.6  867.81   490.1  874.12
   517.2  889.75   531.7  900.77   547.6  914.74   573.9   933.7   583.4  941.58
#Mann= 3 ,-1,0
       0      .1       0  189.26    .045       0  241.61      .1       0
Bank Sta=189.26,241.61
XS Rating Curve= 0 ,0
Exp/Cntr(USF)=0,0
Exp/Cntr=0.3,0.1

Type RM Length L Ch R = 1 ,15393   ,325,324.7,321.7
XS GIS Cut Line= 6
1666386.48894267461287.7884596751666417.02923591461369.785999091
1666443.20634891461440.0696511881666478.10916625461533.780421765
1666504.28627925461604.0637457681666534.82624441461686.061285184
#Sta/Elev= 30
       0  870.52     9.8  867.21    23.5  863.65      48  859.91    86.3  857.01
   113.8  856.67   146.1  855.31   149.6  854.36   153.1  852.18   162.8  842.87
   170.6  837.88   175.6  835.75  186.65833.2954   202.1  833.19   213.8  832.33
     247  832.48  251.46 833.296   264.9  840.16   272.5   845.8   286.1  852.22
   289.6  853.02   303.1  853.58   310.6  857.53   328.1  861.29   356.1  863.09
   370.1  866.95   387.6  870.38   398.1  874.24   415.7  882.79     425  888.18
#Mann= 5 ,-1,0
       0      .1       0  186.65    .045       0  251.46      .1       0
   252.5     .06       0   282.5      .1       0
Bank Sta=186.65,251.46
XS Rating Curve= 0 ,0
Exp/Cntr(USF)=0,0
Exp/Cntr=0.3,0.1

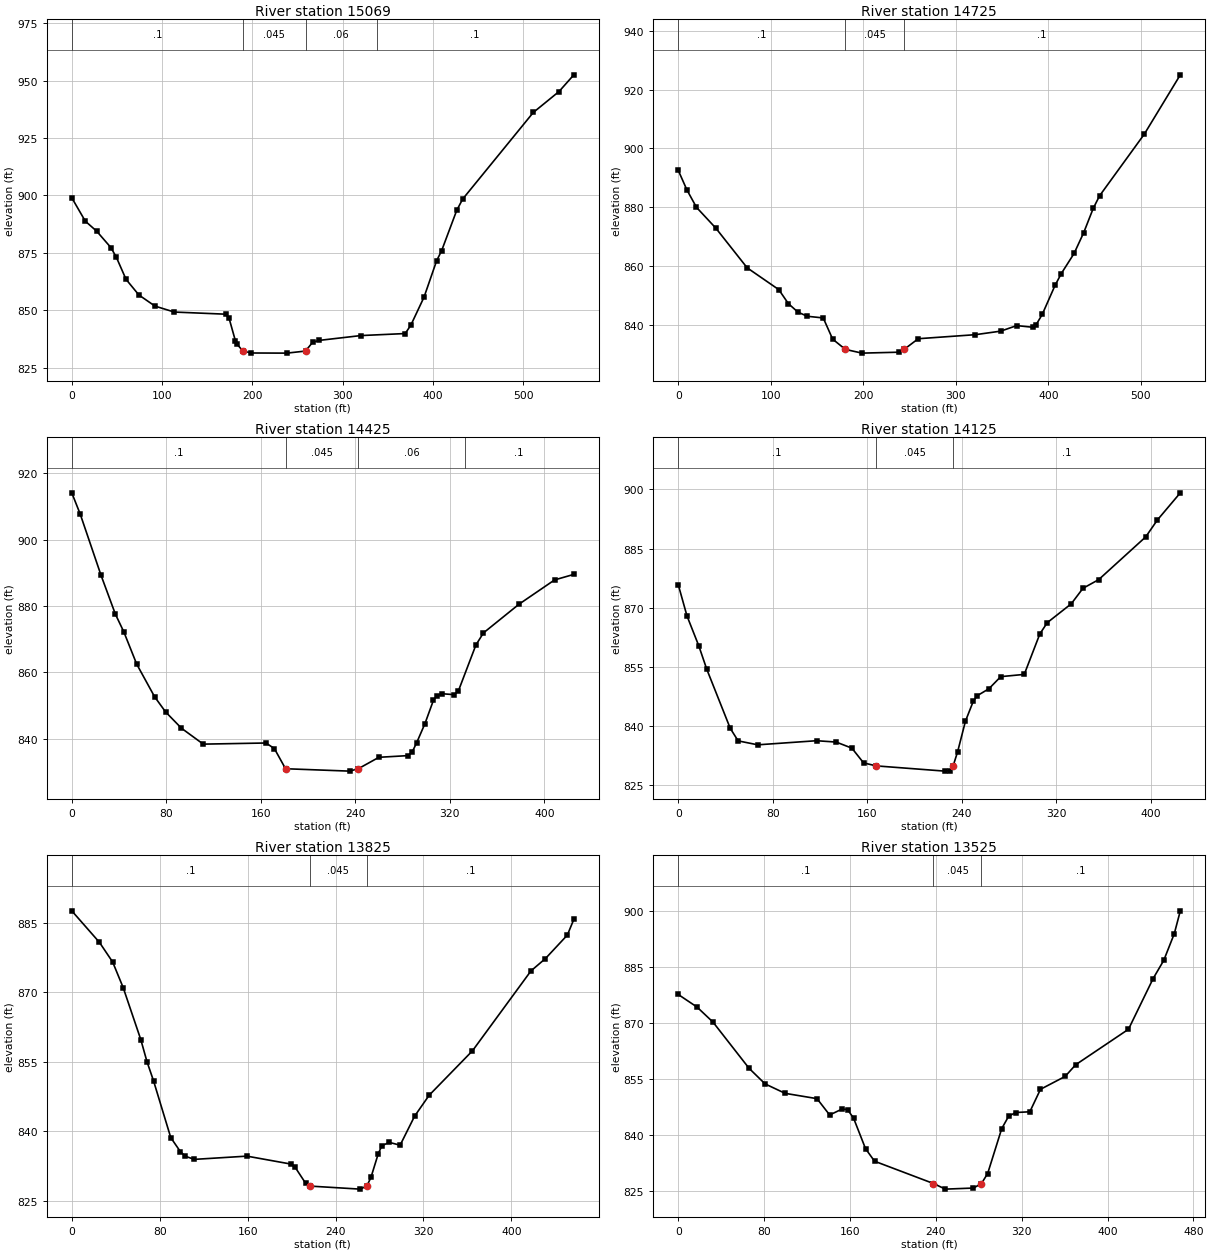
Type RM Length L Ch R = 1 ,15069   ,339.9,343.3,347
XS GIS Cut Line= 6
1666071.43155567461392.2909802531666105.48824608461472.891212764
1666134.67946067461541.9773606691666202.79251341461703.177825677
1666224.96577914461765.7024191761666347.57520723461855.779678415
#Sta/Elev= 30
       0  899.01      15  888.81    27.6  884.44    43.3  877.32    49.4  873.06
    60.1  863.46    74.3  856.66    92.1  851.81   113.5  849.21   170.5  848.28
   174.1  846.66   181.2  836.68   182.8  835.31  189.54832.2106     199  831.37
   238.2  831.31  258.84832.2109   266.7  836.02   273.8  836.85   320.1  838.96
   369.2  839.84   375.4  843.42   390.1  855.71   404.1  871.63   409.5  875.87
   426.3  893.52   432.9  898.45   511.1  936.18   539.6  945.31     556  952.58
#Mann= 4 ,-1,0
       0      .1       0  189.54    .045       0  258.84     .06       0
   337.5      .1       0
Bank Sta=189.54,258.84
XS Rating Curve= 0 ,0
Exp/Cntr(USF)=0,0
Exp/Cntr=0.3,0.1

Type RM Length L Ch R = 1 ,14725   ,302.8,300,297
XS GIS Cut Line= 6
1665774.46359451461510.8354782611665799.60626076461594.645678088
1665821.15707067461666.4824766671665849.89192134461762.265093505
1665871.44273126461834.1018920841665934.33783917462029.281794817
#Sta/Elev= 30
       0  892.57     9.4  885.89    19.7  879.99    40.6  872.92    74.5  859.42
   108.7     852     119  847.26   129.3  844.37   139.5  842.95   156.7  842.38
   166.9  835.17  180.65831.6837   198.6  830.42   238.9  830.74  244.08831.6826
   259.4  835.32   321.1  836.69   348.6   837.9   365.8  839.78     383  839.22
   386.5  839.94   393.4  843.59   407.2  853.43     414  857.48   427.8  864.31
   438.2  871.38   448.5  879.64   455.4  883.93   503.7  904.87   542.6  925.03
#Mann= 3 ,-1,0
       0      .1       0  180.65    .045       0  244.08      .1       0
Bank Sta=180.65,244.08
XS Rating Curve= 0 ,0
Exp/Cntr(USF)=0,0
Exp/Cntr=0.3,0.1

Type RM Length L Ch R = 1 ,14425   ,289.6,300,305
XS GIS Cut Line= 6
1665470.12890135461606.9789867551665503.04025283461688.053627759
1665531.25017017461757.5462709221665568.86262776461850.202909753
 1665597.0725451461919.6955529151665629.98389658 462000.77019392
#Sta/Elev= 30
       0  914.13     7.2  907.67    24.8  889.24    36.9  877.56      44  872.26
      55  862.45    70.1  852.65    79.4  848.08    92.8  843.17   111.3  838.36
   164.4   838.7   171.5  837.02  180.95830.9423   235.2  830.22  242.53830.9417
     260  834.39   284.8   834.9   288.3   836.1   291.9  838.74     299  844.58
   306.1  851.54   308.9  852.89   313.1  853.57   323.8  853.27   327.3  854.43
   342.1  868.25   348.5   871.9   378.7  880.58   408.7  887.87     425  889.54
#Mann= 4 ,-1,0
       0      .1       0  180.95    .045       0  242.53     .06       0
   332.5      .1       0
Bank Sta=180.95,242.53
XS Rating Curve= 0 ,0
Exp/Cntr(USF)=0,0
Exp/Cntr=0.3,0.1

Type RM Length L Ch R = 1 ,14125   ,291,300,306.1
XS GIS Cut Line= 6
1665237.75141335461699.4850353451665252.08668651 461785.81786792
1665262.99873817461860.0201473391665277.54792167461958.955973089
1665288.45997334462033.1579244291665301.19091901462119.726648927
#Sta/Elev= 30
       0  875.83     7.4  867.89    17.4  860.29    24.1  854.39      44  839.36
    50.7  836.16    67.3  835.16   117.1   836.2   133.7  835.86     147  834.31
   156.9  830.57  167.59829.8105   225.7  828.48   229.9  828.63  232.69829.8101
   236.5   833.4   243.1  841.14   249.8  846.26   253.1  847.63     263   849.4
     273  852.47   292.9  853.04   306.1  863.32   312.4  866.18   332.7  870.97
   342.6   874.9   355.9   877.1   395.7  887.95   405.6  892.25     425  899.14
#Mann= 3 ,-1,0
       0      .1       0  167.59    .045       0  232.69      .1       0
Bank Sta=167.59,232.69
XS Rating Curve= 0 ,0
Exp/Cntr(USF)=0,0
Exp/Cntr=0.3,0.1

Type RM Length L Ch R = 1 ,13825   ,266.9,300,334.3
XS GIS Cut Line= 6
1665065.19795267461710.6858003441664987.33327901461801.258781925
1664977.75488609461875.644788012 1664964.9812896461974.825692013
1664955.40158434462049.2113700061664944.22476943462135.994661003
#Sta/Elev= 30
       0  887.53    25.2  880.72    37.2  876.49    46.8  870.95    62.8  859.75
    68.5  854.93    74.4  850.85    90.1  838.58    98.8  835.58   103.1  834.59
   111.5  833.89   159.4  834.59   199.6  832.87   202.9  832.32   212.8  828.74
  216.68828.1267   262.4  827.47  268.52828.1269   272.3  830.03   278.9   835.1
   282.2  836.84   288.9  837.56   298.8  836.95     312  843.22   325.3  847.75
   364.6  857.31   417.9  874.57   431.1  877.24     451   882.3   456.9   885.7
#Mann= 3 ,-1,0
       0      .1       0  216.68    .045       0  268.52      .1       0
Bank Sta=216.68,268.52
XS Rating Curve= 0 ,0
Exp/Cntr(USF)=0,0
Exp/Cntr=0.3,0.1

Type RM Length L Ch R = 1 ,13525   ,291.6,300,313.9
XS GIS Cut Line= 6
1665030.82827076461680.9653873441664918.59358709461741.817955926
1664842.43100975461757.0400383321664742.46959551461759.816935673
1664667.49828875461761.8992805931664580.03225634461764.329065755
#Sta/Elev= 30
       0  877.68    17.5  874.31    32.4  870.28      66  857.92    80.9  853.75
    99.6  851.22   129.3   849.8   141.1  845.43   152.7  847.03   157.8  846.86
   163.4  844.56   174.5  836.42   182.9  833.06  237.82827.0863   248.9  825.59
   275.1  825.88  282.52827.0875   288.3  829.77   301.4  841.78   307.9  845.12
   314.5  846.09   327.6  846.29   337.5   852.3   360.5  855.75   370.3  858.87
   419.5  868.37   442.5  881.95   452.4  886.82   462.2  893.96   467.8  900.06
#Mann= 3 ,-1,0
       0      .1       0  237.82    .045       0  282.52      .1       0
Bank Sta=237.82,282.52
XS Rating Curve= 0 ,0
Exp/Cntr(USF)=0,0
Exp/Cntr=0.3,0.1

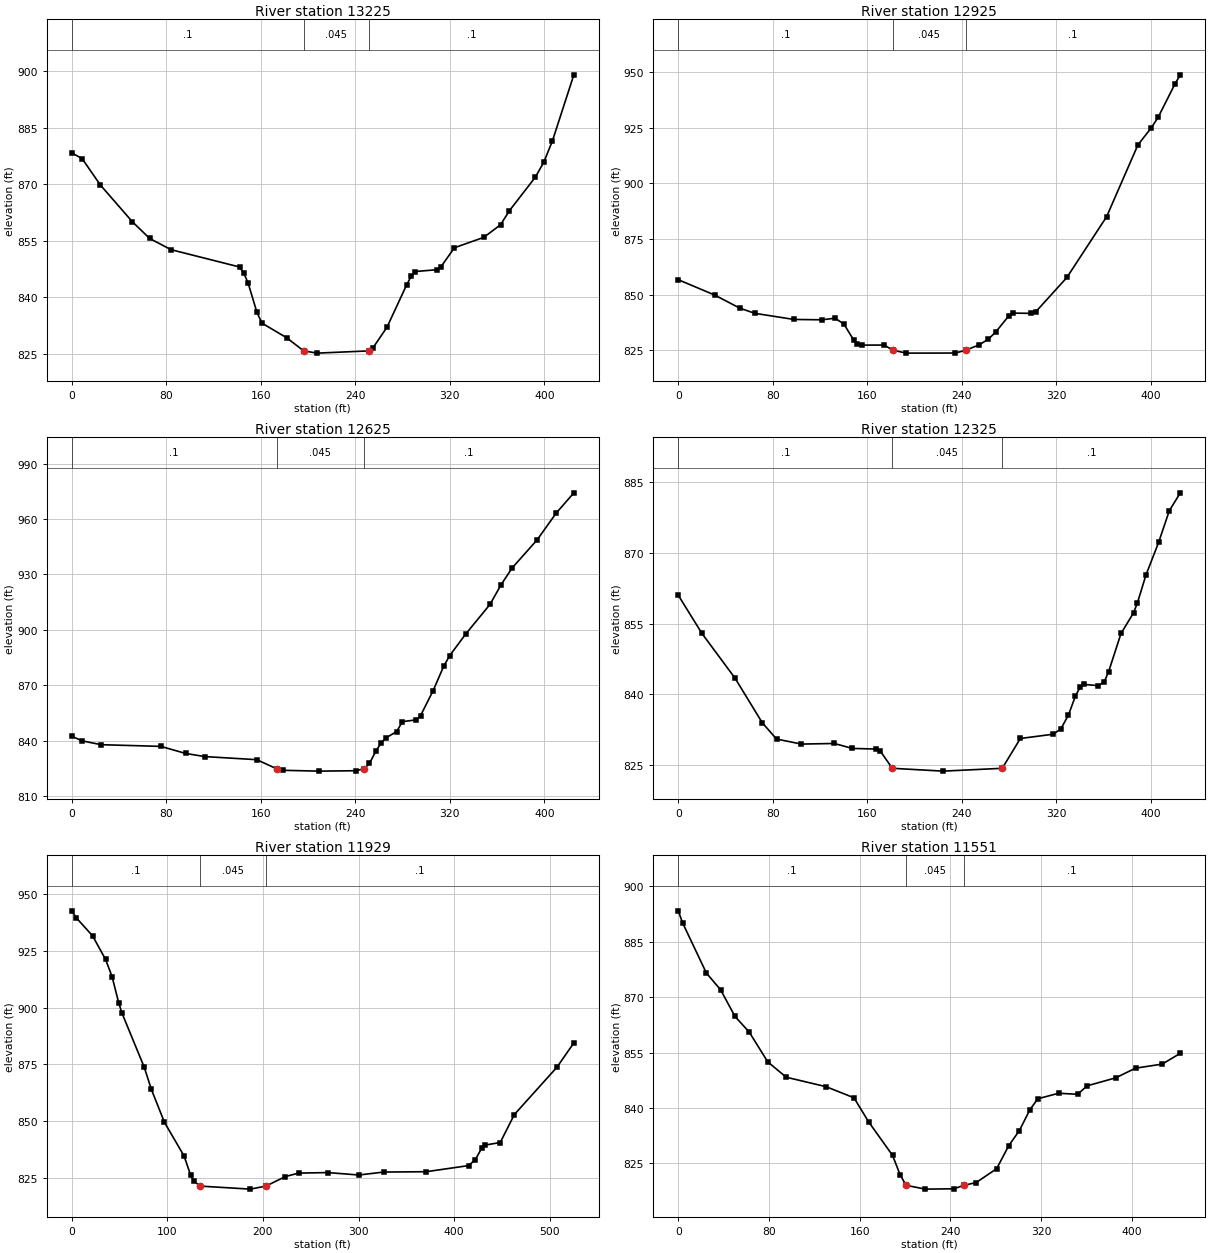
Type RM Length L Ch R = 1 ,13225   ,298.6,300,302.7
XS GIS Cut Line= 6
1665071.72976376461566.2500655951664992.60295351461528.898106173
1664924.77992642461496.8820940851664834.34900492461454.193859249
1664766.52597784461422.177847177 1664687.3988395461384.825887755
#Sta/Elev= 30
       0  878.29     8.8  876.75    24.2  869.76    51.3     860    65.9  855.57
      84  852.59     142  847.99   145.7  846.32   149.3   843.7   156.6  836.08
   160.9   833.1     182  829.18  196.27825.7166   207.8  825.12  251.65825.7162
   254.8  826.44   266.9  832.04   283.5  843.27   287.2  845.48   290.8  846.79
   308.9  847.26   312.6  848.08   323.9   853.1   348.8  855.86     363  859.22
   370.4  862.91   392.4  871.83   399.6  875.84   406.9   881.5     425  899.01
#Mann= 3 ,-1,0
       0      .1       0  196.27    .045       0  251.65      .1       0
Bank Sta=196.27,251.65
XS Rating Curve= 0 ,0
Exp/Cntr(USF)=0,0
Exp/Cntr=0.3,0.1

Type RM Length L Ch R = 1 ,12925   ,288.2,300,310.7
XS GIS Cut Line= 6
1665203.20817535461314.5327212511665127.05248776461271.444880918
1665061.77637158461234.5122120081664974.74144067461185.269200251
1664909.46499643461148.3365313411664833.30930884461105.248691007
#Sta/Elev= 30
       0  856.71      31  849.77    52.1  843.92    64.9  841.59    97.9  838.85
   121.5  838.69   132.8   839.4   140.3  836.74   148.4   829.7   151.6  827.98
   155.4  827.32   174.3  827.35   181.7825.0467   193.1  823.72   234.6  823.76
  243.35825.0469   254.4  827.35   262.5  829.97   268.8  833.24   279.8  840.43
   283.2   841.7   298.6  841.59   302.5   842.2     329  857.71   362.6  884.99
   389.1  917.25   400.4   924.9   406.3  929.71   420.5  944.69     425  948.73
#Mann= 3 ,-1,0
       0      .1       0   181.7    .045       0  243.35      .1       0
Bank Sta=181.7,243.35
XS Rating Curve= 0 ,0
Exp/Cntr(USF)=0,0
Exp/Cntr=0.3,0.1

Type RM Length L Ch R = 1 ,12625   ,286.9,300,318.5
XS GIS Cut Line= 6
1665342.67180717461134.947122425 1665284.5748105461069.517791346
1665234.77733792461013.4355544151665168.38081717460938.659457251
1665118.58334459460882.5772203361665060.48634793460817.147889256
#Sta/Elev= 30
       0  842.39     8.6  839.87      25  837.78    75.4  836.87    96.3  833.06
   112.5  831.35   156.6  829.67  173.31824.7886   178.5  823.92   209.2  823.47
   240.4  823.69   247.6824.7886     252  827.63   257.5  834.41   261.9  838.76
   265.9  841.45     275   844.9   279.9  850.27   291.5  851.22   295.2  853.49
   305.8  866.94   314.9  880.36   319.9  886.01   333.3  897.59     354  913.74
   363.5  924.51   372.8  933.53     394  948.77     410  963.16     425  974.19
#Mann= 3 ,-1,0
       0      .1       0  173.31    .045       0   247.6      .1       0
Bank Sta=173.31,247.6
XS Rating Curve= 0 ,0
Exp/Cntr(USF)=0,0
Exp/Cntr=0.3,0.1

Type RM Length L Ch R = 1 ,12325   ,415.2,396,345
XS GIS Cut Line= 6
1665524.94572084461013.5887693321665493.67052092  460931.8691165
1665466.86283176460861.8236529231665431.11946492460768.429810837
1665404.31210384 460698.384347261665373.03690392460616.664694428
#Sta/Elev= 30
       0  861.03      20  852.92    48.1  843.38    71.1  833.92    83.2  830.44
   104.3  829.37   132.1   829.5   147.3  828.45   167.6  828.31   171.1  827.86
  181.21 824.221   224.2  823.62  274.27824.2205   289.6  830.56   317.5  831.47
     324  832.65   330.3  835.54   336.2  839.57   340.4  841.57   343.2  842.06
   355.7   841.8   360.7  842.64   364.3  844.76   374.8  852.89   385.4  857.27
   388.7   859.4   395.9   865.3   406.6  872.23   415.7  878.99     425  882.79
#Mann= 3 ,-1,0
       0      .1       0  181.21    .045       0  274.27      .1       0
Bank Sta=181.21,274.27
XS Rating Curve= 0 ,0
Exp/Cntr(USF)=0,0
Exp/Cntr=0.3,0.1

Type RM Length L Ch R = 1 ,11929   ,396.8,378.4,335.4
XS GIS Cut Line= 2
1665899.07623276460641.9561071181665395.51468636460492.913683553
#Sta/Elev= 30
       0  942.55     4.6  939.54    21.7  931.58    35.3  921.22    42.2  913.55
      49  902.21    52.5  897.58    75.9  873.64    83.2  864.07    96.9  849.55
   117.5  834.67   124.3  826.32   127.7  823.61  134.43  821.45   186.8  820.12
     203  821.45   223.5  825.65   237.2  827.17     268   827.4   300.3  826.33
   326.2  827.63   370.7  827.78   415.1  830.47     422  833.04   428.8  838.08
   432.2  839.49   448.2  840.63     463  852.95   507.5  873.74   525.2  884.45
#Mann= 3 ,-1,0
       0      .1       0  134.43    .045       0     203      .1       0
Bank Sta=134.43,203
XS Rating Curve= 0 ,0
Exp/Cntr(USF)=0,0
Exp/Cntr=0.3,0.1

Type RM Length L Ch R = 1 ,11551   ,458.5,452.2,444.1
XS GIS Cut Line= 3
1665766.49553395460129.1719727111665458.59121348460374.524944075
1665425.04124777460410.086730348
#Sta/Elev= 30
       0  893.35     3.9  890.05    24.8  876.52    37.4  871.95      50  864.78
    62.6  860.52    78.9  852.47    95.2  848.31   130.3  845.75   154.9  842.75
   167.8  836.25   188.9  827.16   195.6  821.92  200.85819.0536   217.8  818.02
     243  818.11  251.84 819.054   262.6  819.79   280.7  823.55   291.4  829.81
   300.7  833.85     310  839.51     317  842.48   335.3  843.97   352.1  843.69
   360.4  845.97   385.6  848.14   403.1  850.76   426.6  851.86   442.6  854.78
#Mann= 3 ,-1,0
       0      .1       0  200.85    .045       0  251.84      .1       0
Bank Sta=200.85,251.84
XS Rating Curve= 0 ,0
Exp/Cntr(USF)=0,0
Exp/Cntr=0.3,0.1