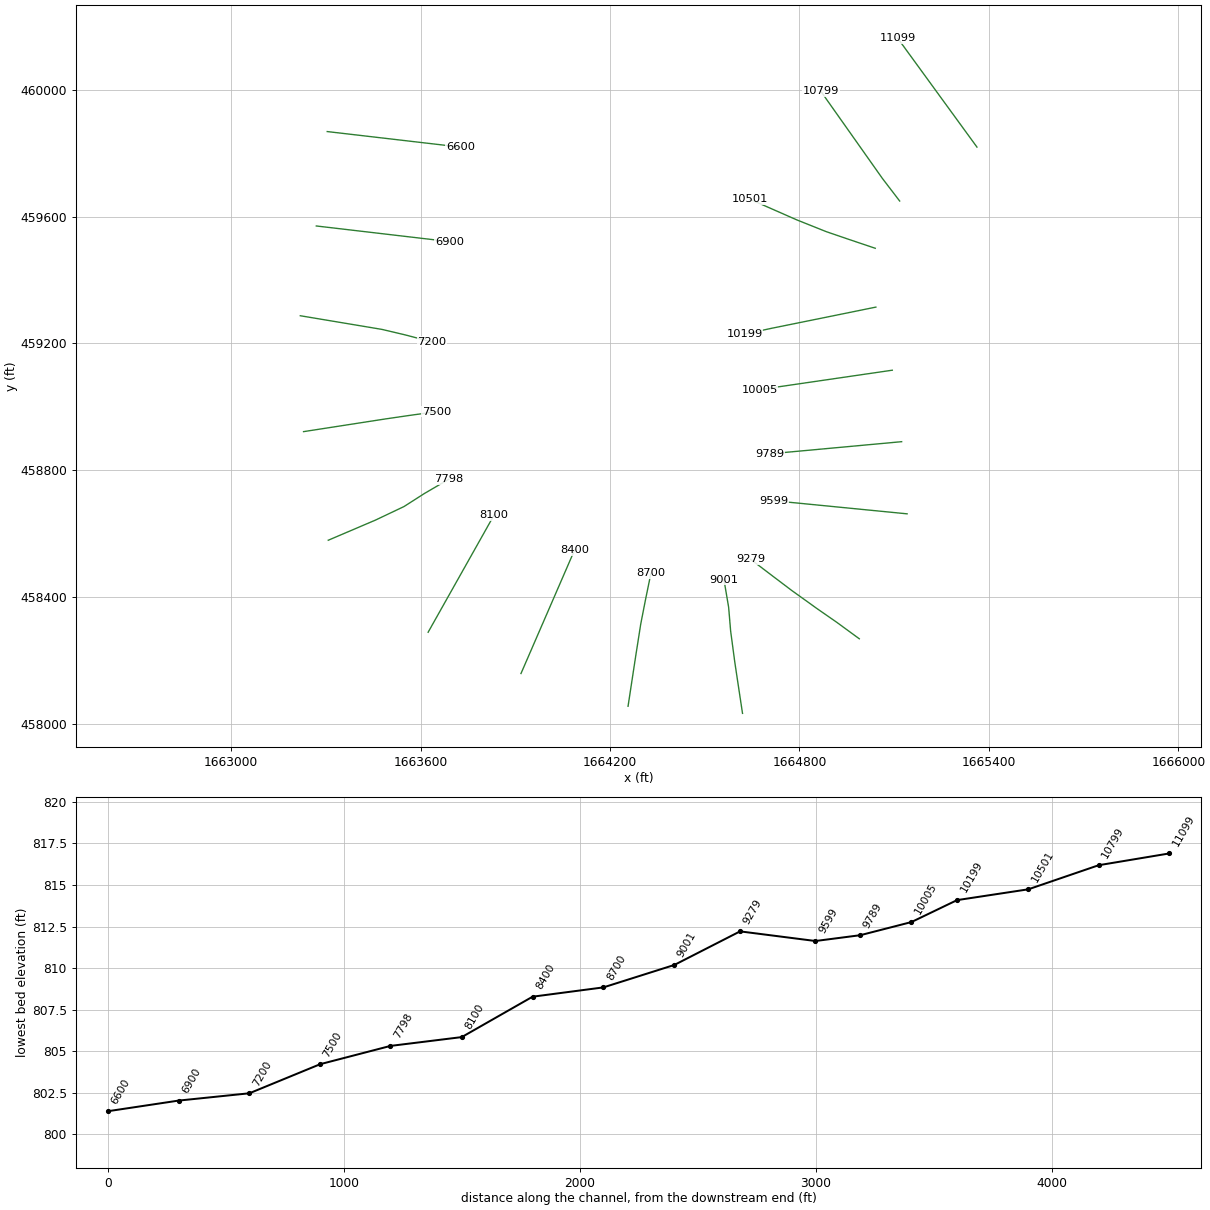
HEC-RAS study PenFrkFshCk.prj: PenFrkFshCk

--- PenFrkFshCk.g01 (geometry) --- (continued)

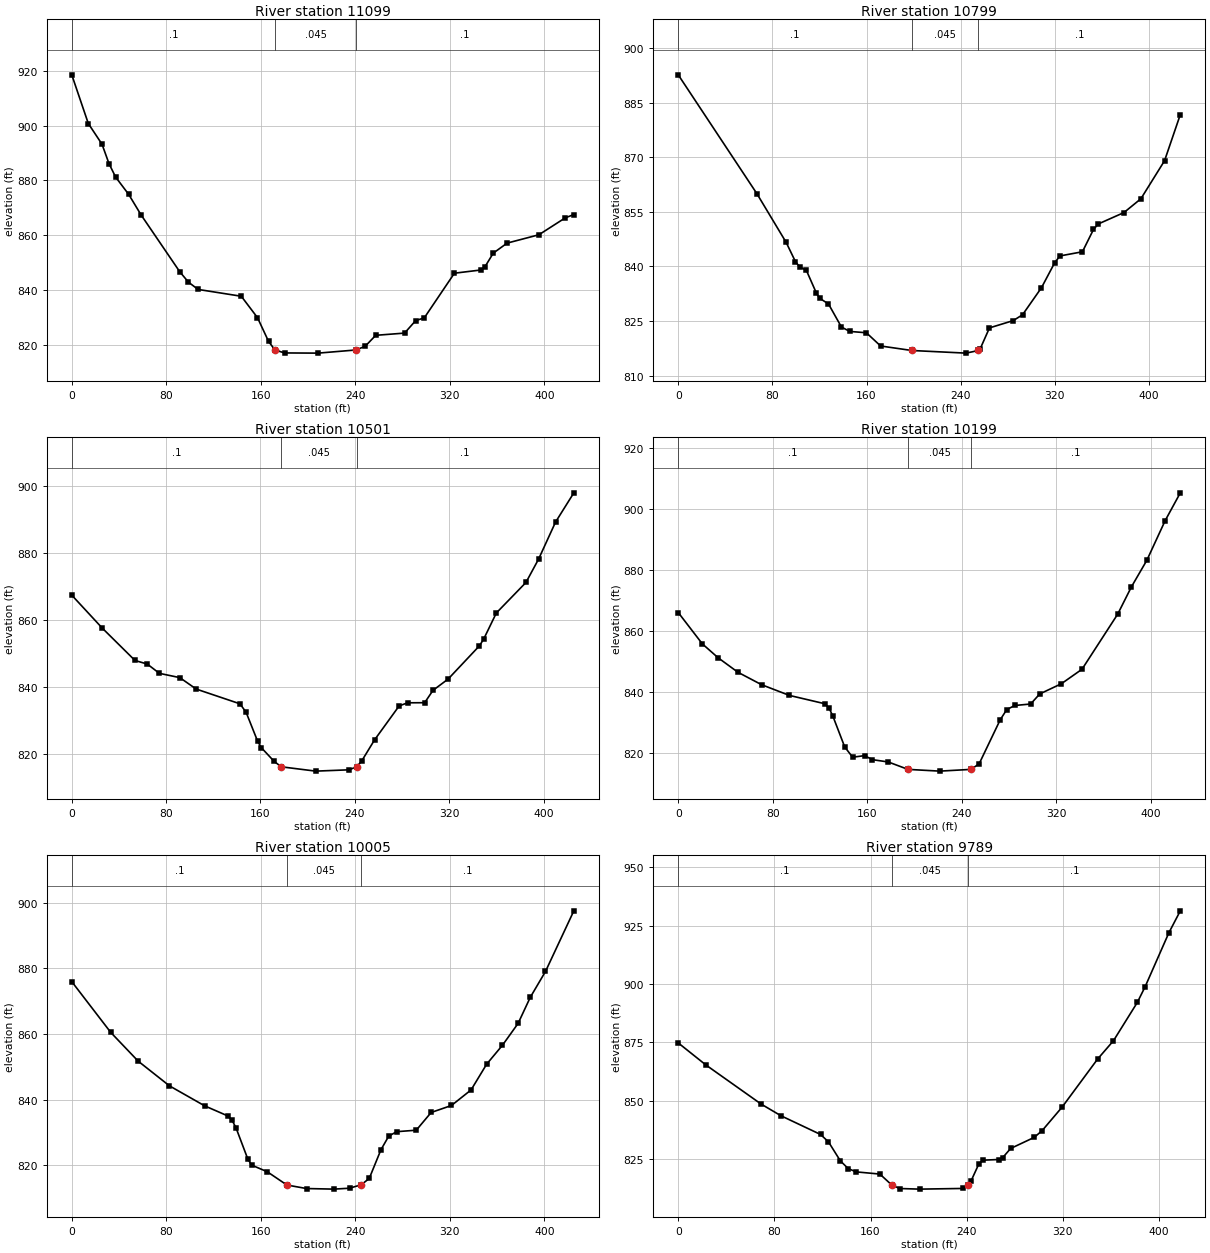
Type RM Length L Ch R = 1 ,11099   ,301.2,300,299.2
XS GIS Cut Line= 6
1665362.12452418 459819.35067226  1665310.497987459889.997512594
1665266.24676317459950.5518534181665207.24556884460031.291193262
1665162.99434501460091.8455340861665111.36813593 460162.49237442
#Sta/Elev= 30
       0  918.62      14  900.82    25.6  893.26    31.5  886.18    37.1  881.26
    48.2  874.91    58.6  867.46    91.5  846.59    98.8  842.83   106.9  840.18
   143.5  837.69   157.2  829.87   166.6  821.17  172.01818.0537   180.1  816.97
   208.5   816.9  240.55 818.054   248.4  819.42   257.3  823.41   281.7  824.22
   291.1  828.78   298.4  829.79   323.9  846.11   346.7  847.31   349.8  848.49
   356.8  853.45   368.5  857.11   395.4  860.16   417.8  866.36     425  867.55
#Mann= 3 ,-1,0
       0      .1       0  172.01    .045       0  240.55      .1       0
Bank Sta=172.01,240.55
XS Rating Curve= 0 ,0
Exp/Cntr(USF)=0,0
Exp/Cntr=0.3,0.1

Type RM Length L Ch R = 1 ,10799   ,286.7,298.3,319.5
XS GIS Cut Line= 6
1665117.28675926459649.3303430081665062.96108051459720.030989006
1665019.57599667459781.209016249 1664961.7329365459862.782015845
1664918.35047734459923.9616835121664867.73804575459995.338181168
#Sta/Elev= 30
       0  892.61    66.8     860    91.7  846.61    99.6  841.32   103.2  839.88
   108.9  838.92   117.5  832.61   120.2  831.26   127.7  829.69   138.7  823.35
   145.8  822.15   159.9  821.78     172  818.15  198.48816.9132   244.6  816.19
  255.17816.9128   256.4  817.21   264.5  823.12   284.7  825.12   292.6  826.72
   308.7  834.15   319.9  840.99   324.4  842.88   343.5  844.02   352.9  850.14
     357  851.66   378.8  854.79   393.2  858.58   413.3  869.02   426.7   881.7
#Mann= 3 ,-1,0
       0      .1       0  198.48    .045       0  255.17      .1       0
Bank Sta=198.48,255.17
XS Rating Curve= 0 ,0
Exp/Cntr(USF)=0,0
Exp/Cntr=0.3,0.1

Type RM Length L Ch R = 1 ,10501   ,285.2,301.9,319.4
XS GIS Cut Line= 6
1665040.00344926459500.1629904211664956.71883893459528.112737671
1664885.46799718459552.3797495071664792.48819625459589.349163756
1664723.79410793459619.4511376771664643.65089551459654.569833845
#Sta/Elev= 30
       0  867.36    25.9  857.49    53.6  847.83      64  846.76    74.3  843.98
    91.6   842.7   105.5  839.28   142.6  834.87   147.8  832.35   157.5  823.75
   160.7  821.76   171.5  817.69  177.57 816.036   206.8  814.74   235.1  815.13
  241.49816.0355   245.7   817.7   256.7  824.07   277.6  834.25   284.8  835.17
   299.2   835.2   306.3   838.9   319.1  842.27   345.7  852.23   349.3  854.26
     360  862.04   385.1  871.16   395.8  878.14   410.2  889.22   425.7  897.96
#Mann= 3 ,-1,0
       0      .1       0  177.57    .045       0  241.49      .1       0
Bank Sta=177.57,241.49
XS Rating Curve= 0 ,0
Exp/Cntr(USF)=0,0
Exp/Cntr=0.3,0.1

Type RM Length L Ch R = 1 ,10199   ,196.9,193.3,192.4
XS GIS Cut Line= 6
1665042.03264467459314.611196175 1664956.2647716459297.156178594
 1664882.7353911459282.2707096791664784.71294934459262.475145593
1664711.21178401459247.6372487551664625.65519659459229.259004667
#Sta/Elev= 30
       0  866.06    20.4  855.79    33.8  851.22    50.6  846.47    70.6   842.4
    94.1   838.9   124.2  836.16   127.6  834.81   130.9  832.11   140.9  822.03
   147.6  818.65   157.7  819.16   164.4  817.84   177.8  817.09  194.49814.6613
   221.3  814.09  247.83814.6615   254.7  816.48   272.6  830.95   278.1  834.26
   284.9   835.6   298.3  836.08     306  839.38   324.3  842.72   341.8  847.48
     372  865.53   383.6  874.46   396.7   883.2   412.2  896.19     425  905.28
#Mann= 3 ,-1,0
       0      .1       0  194.49    .045       0  247.83      .1       0
Bank Sta=194.49,247.83
XS Rating Curve= 0 ,0
Exp/Cntr(USF)=0,0
Exp/Cntr=0.3,0.1

Type RM Length L Ch R = 1 ,10005   ,218.1,216.6,214.8
XS GIS Cut Line= 6
1665094.00302084459115.5138860871665007.41428325459102.919423096
1664933.19527158 459092.12384101   1664834.23648459077.730169006
1664760.01746833 459066.934586921664673.42873076459054.340123929
#Sta/Elev= 30
       0  875.98      33  860.51    56.2  851.76    82.7  844.23   112.5  838.14
   132.4  835.02   135.7  833.73     139  831.47     149  821.95   152.3  820.08
   165.6  818.04   182.1  814.02   198.7  812.95   221.9  812.77   235.2  813.05
   245.1  814.12   251.8  816.02   261.7  824.76   268.3  828.91     275  830.27
   291.6  830.72   304.2  836.12   321.4  838.25     338  842.99   351.2  850.84
   364.5  856.57   377.8  863.25   388.1  871.19     401  879.08     425  897.55
#Mann= 3 ,-1,0
       0      .1       0   182.1    .045       0   245.1      .1       0
Bank Sta=182.1,245.1
XS Rating Curve= 0 ,0
Exp/Cntr(USF)=0,0
Exp/Cntr=0.3,0.1

Type RM Length L Ch R = 1 ,9789    ,197.2,190,186.3
XS GIS Cut Line= 2
1665123.54271176458890.0058392871664707.51229304458851.815546943
#Sta/Elev= 30
       0  874.72    22.9   865.3      69  848.47    85.5  843.46   118.4  835.44
     125  832.28   134.9  824.11   141.5  820.77   148.1  819.38   167.8  818.44
   177.7  813.74   184.3  812.24   200.8  811.98     237  812.27   241.3  813.77
   243.6  815.41   250.2  822.84   253.5   824.4   266.7  824.69     270   825.5
   276.6  829.42   296.3   834.2   302.9  837.13   319.4  847.15     349  867.81
   362.2  875.68     382  892.07   388.6  898.92   408.3     922   417.8   931.4
#Mann= 3 ,-1,0
       0      .1       0   177.7    .045       0   241.3      .1       0
Bank Sta=177.7,241.3
XS Rating Curve= 0 ,0
Exp/Cntr(USF)=0,0
Exp/Cntr=0.3,0.1

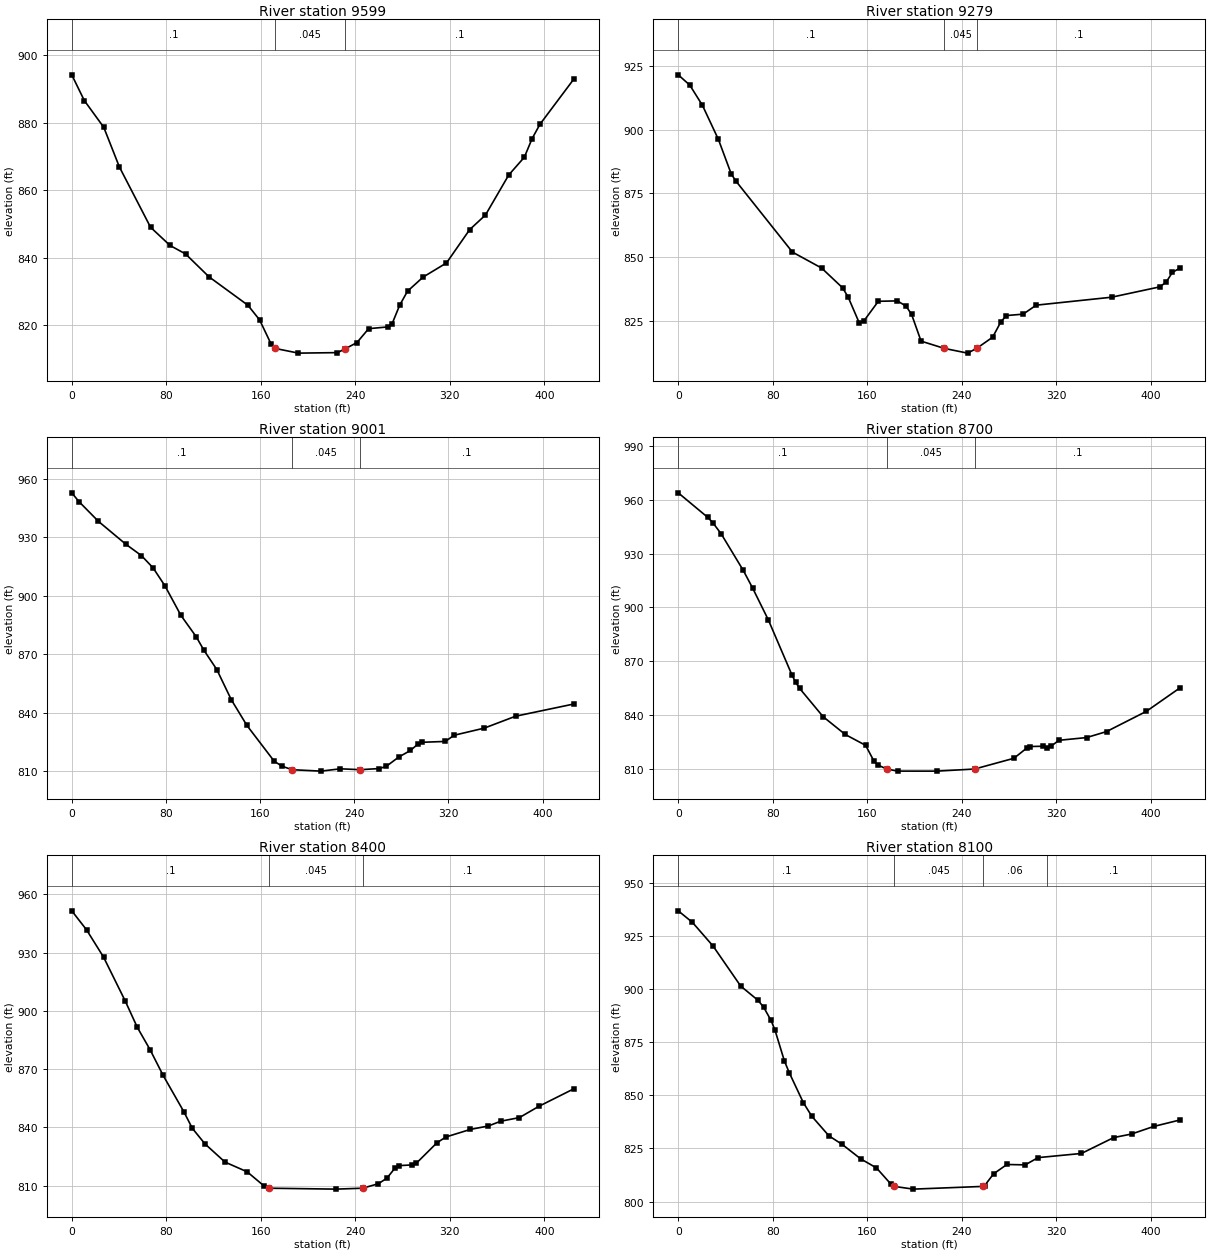
Type RM Length L Ch R = 1 ,9599    ,336.1,319.6,308.7
XS GIS Cut Line= 6
1665140.86610842458662.4081042561665053.78163692458670.927116096
1664979.13808542458678.2292668371664879.61302201 458687.96546784
1664804.96914242458695.2676185821664717.88499901458703.786630422
#Sta/Elev= 30
       0   894.2    10.6  886.58    27.1  878.62    40.3  866.87    66.7  848.97
    83.2  843.57    96.3  841.06   116.1  834.29   149.1  825.84     159  821.49
   168.9   814.2   172.2  813.02   191.9  811.63   224.9  811.78   231.7  812.96
   241.4  814.76   251.3  818.89   267.8  819.41   271.1   820.3   277.6  825.87
   284.2     830   297.4  834.19   317.2  838.39   336.8  848.26   350.2  852.61
   369.9  864.49   383.1  869.76   389.7   875.3   396.3  879.52     425  892.95
#Mann= 3 ,-1,0
       0      .1       0   172.2    .045       0   231.7      .1       0
Bank Sta=172.2,231.7
XS Rating Curve= 0 ,0
Exp/Cntr(USF)=0,0
Exp/Cntr=0.3,0.1

Type RM Length L Ch R = 1 ,9279    ,294.1,278.4,254.6
XS GIS Cut Line= 6
1664989.40863034 458268.237148941664918.69551718458319.758371353
1664857.00108677458362.4062519371664775.61017344458420.525230199
1664715.64310177458465.6711372731664645.82434377458518.548656195
#Sta/Elev= 30
       0  921.47     9.8  917.42    20.5  909.48      34  896.12    44.9  882.52
      49  879.65    96.7  851.87   121.4  845.61   139.1  837.87   143.8  834.28
   153.3  824.04   157.3  824.92   169.4  832.56   185.5  832.72   192.9  830.66
   197.6  827.39   205.6  816.92  225.24814.0695     245  812.21  252.67814.0703
   266.2  818.46   273.2  824.52   277.9  826.96     292  827.51   303.1  831.04
   366.9  834.16   407.8  838.23   413.2  840.15   418.4  843.91   425.1  845.69
#Mann= 3 ,-1,0
       0      .1       0  225.24    .045       0  252.67      .1       0
Bank Sta=225.24,252.67
XS Rating Curve= 0 ,0
Exp/Cntr(USF)=0,0
Exp/Cntr=0.3,0.1

Type RM Length L Ch R = 1 ,9001    ,308.9,300.6,290.7
XS GIS Cut Line= 6
1664619.59352893458032.8778672521664606.48561551458119.390489504
1664595.25007367458193.5438845011664581.98139942458292.674919844
1664575.63889243 458367.570111261664560.72389601458455.169017419
#Sta/Elev= 30
       0  952.76     6.1  948.26    22.7  938.12    45.9  926.44    59.2  920.59
    69.1  914.29    79.1  905.17    92.7  889.99   105.6  879.13   112.3  872.08
   123.2  862.23   135.5  846.78   148.8  833.58     172  815.24   178.6  812.72
  187.07810.9286   211.7  810.19   228.2  811.38  245.04810.9294   261.3  811.51
   267.1  812.61   277.8  817.42   287.7  820.77   294.3  824.18   297.6  824.97
   317.3   825.4   324.8  828.57   350.4  832.22     377  838.32   426.5  844.58
#Mann= 3 ,-1,0
       0      .1       0  187.07    .045       0  245.04      .1       0
Bank Sta=187.07,245.04
XS Rating Curve= 0 ,0
Exp/Cntr(USF)=0,0
Exp/Cntr=0.3,0.1

Type RM Length L Ch R = 1 ,8700    ,310.5,300.2,291
XS GIS Cut Line= 6
1664257.07883401458055.3827435081664270.31732459458141.875352666
1664281.66474284458216.0120154171664297.26543343458314.788720757
 1664311.7109426458388.4513030951664329.36215401458474.268388674
#Sta/Elev= 30
       0  963.85    25.1  950.12    29.2  947.28    36.4  940.98    55.1  920.61
      63   910.8    76.3  893.09    96.2  862.56    99.5  858.24   102.8  854.92
   122.7  839.16   141.4  829.27   158.7   823.2   165.9  814.24   169.2  812.23
  176.55810.0042   185.8  808.85     219  808.84  250.96810.0048   284.3     816
   295.6  821.92   298.3  822.55     309   822.7   312.3  821.94   315.7  822.71
   322.4  826.01   345.8  827.53   362.7  830.86   396.4  842.12   425.2  855.35
#Mann= 3 ,-1,0
       0      .1       0  176.55    .045       0  250.96      .1       0
Bank Sta=176.55,250.96
XS Rating Curve= 0 ,0
Exp/Cntr(USF)=0,0
Exp/Cntr=0.3,0.1

Type RM Length L Ch R = 1 ,8400    ,303.3,300,295.4
XS GIS Cut Line= 6
 1663917.9932261 458158.624663011663952.93377301458238.845631167
1663982.88286009458307.6063204261664022.81519492458399.287239417
  1664052.764282458468.0482567551664087.70482892458548.269224927
#Sta/Elev= 30
       0  951.48    12.5  941.71    26.9  927.68    45.3  905.03    55.5  891.49
    66.2  880.12    77.3  866.85    94.9  848.08     102  839.61   112.7  831.59
   129.7   822.2   148.5  817.18   162.8  809.88   167.1  808.75   223.7  808.28
  246.16 808.751   259.5  811.05   266.8  813.94   273.8  819.27   276.7  820.36
   288.1  820.74   291.7  821.62   309.1  832.12   316.7  835.11   337.5  839.02
   352.5  840.75   363.2  843.24   378.9  845.08   395.4  850.89     425   859.9
#Mann= 3 ,-1,0
       0      .1       0   167.1    .045       0  246.16      .1       0
Bank Sta=167.1,246.16
XS Rating Curve= 0 ,0
Exp/Cntr(USF)=0,0
Exp/Cntr=0.3,0.1

Type RM Length L Ch R = 1 ,8100    ,313.7,302,277.5
XS GIS Cut Line= 6
1663623.85897183458288.8169879171663666.89989626458364.999250263
1663703.79221092458430.2983322591663752.98174509458517.363774925
1663789.87373167458582.6625288431663832.91465609458658.845119253
#Sta/Elev= 30
       0  936.77      12  931.35    29.5  920.19    52.9  901.36    67.2  894.82
    72.2  891.56    78.5  885.24    81.8  880.83    89.8  866.25    93.9  860.71
   105.9  846.53   113.1   840.1   127.6   830.9   138.8  826.88   154.5  820.07
   167.8  815.83   180.2   808.1   182.9807.1339     199  805.85  258.08807.1342
   259.3  807.45   266.9  813.03   278.2  817.44   293.7  817.26   304.6  820.67
   341.3  822.63   368.6   830.1   383.7  831.77   402.5  835.34     425  838.42
#Mann= 4 ,-1,0
       0      .1       0   182.9    .045       0  258.08     .06       0
   312.5      .1       0
Bank Sta=182.9,258.08
XS Rating Curve= 0 ,0
Exp/Cntr(USF)=0,0
Exp/Cntr=0.3,0.1

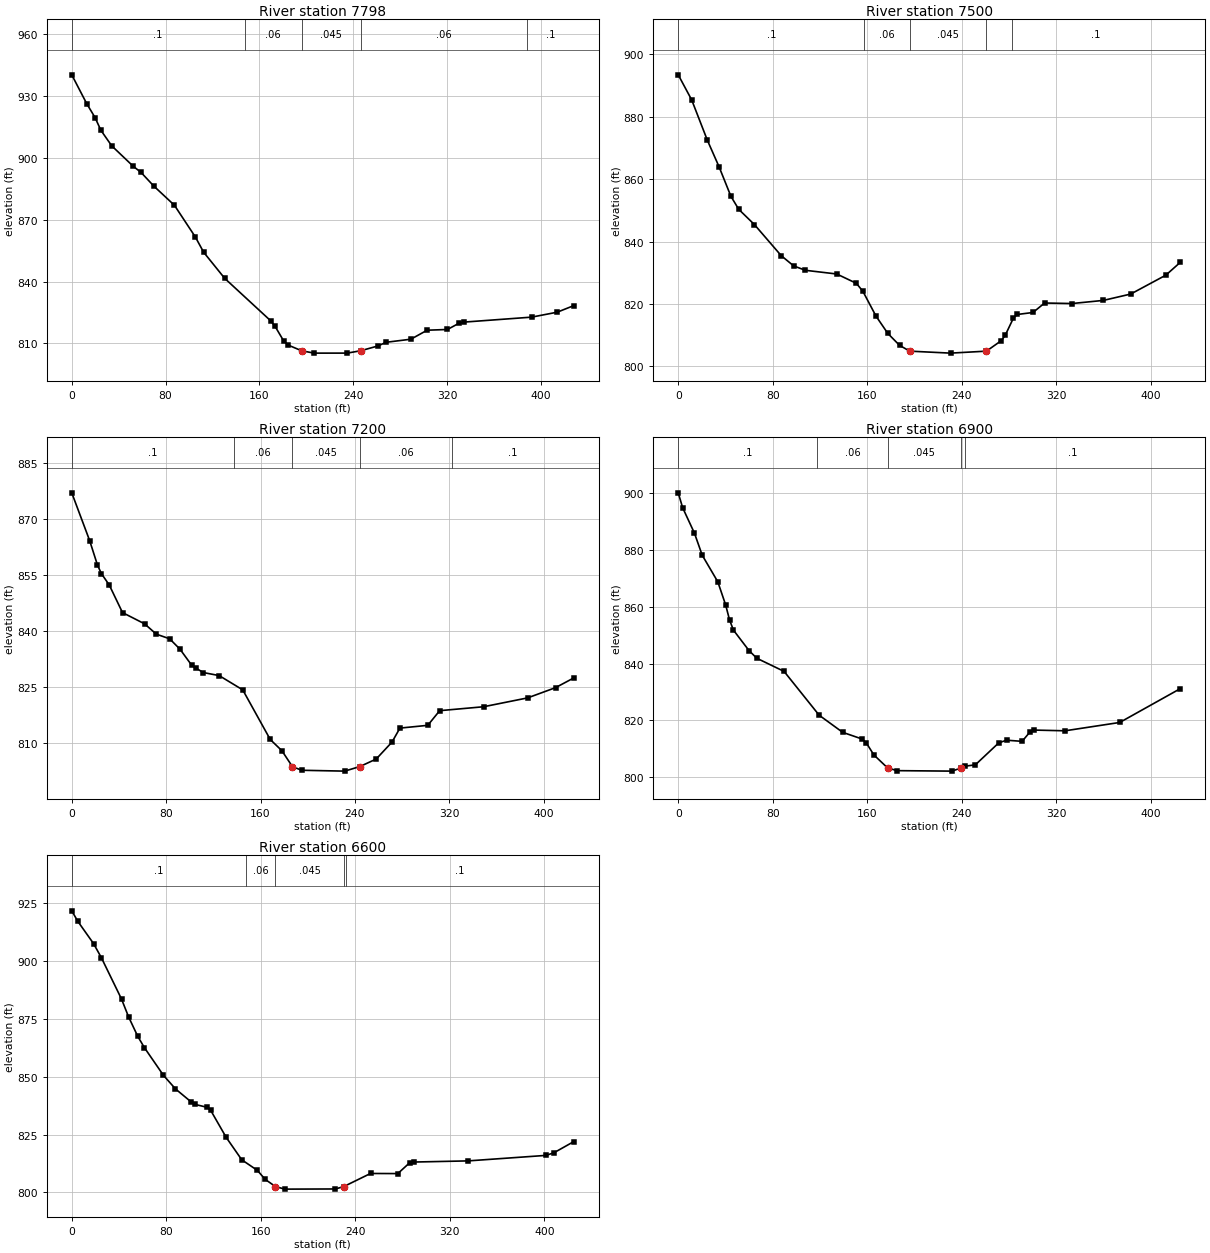
Type RM Length L Ch R = 1 ,7798    ,302.7,298,287.8
XS GIS Cut Line= 6
1663307.57449943458579.0906855911663388.10353784458613.315682754
1663457.12833418458642.6512539981663547.60026608458685.438570008
1663611.71759193458726.3213622571663689.13640034458771.417400673
#Sta/Elev= 30
       0  940.09    12.7  926.18    19.9  919.35    24.8  913.26    34.1  905.69
    52.3  895.87    59.1  892.82    69.8  886.31    87.6  876.89   105.4  861.56
   112.5  854.16   130.4  841.55   169.5  821.05   173.3  818.37   180.6  811.35
   184.2  809.31  195.95806.4808   206.7  805.32     235  805.33  246.46 806.481
     261  808.77   268.1  810.57   289.2  812.06   303.1  816.42   320.4  816.77
   329.9  819.68   334.2  820.33   392.2  822.75     414  825.14   428.2  828.34
#Mann= 5 ,-1,0
       0      .1       0   147.5     .06       0  195.95    .045       0
  246.46     .06       0  388.62      .1       0
Bank Sta=195.95,246.46
XS Rating Curve= 0 ,0
Exp/Cntr(USF)=0,0
Exp/Cntr=0.3,0.1

Type RM Length L Ch R = 1 ,7500    ,307.2,300,288.5
XS GIS Cut Line= 6
1663229.31153259458921.7087667581663315.78576909458935.066679671
1663389.90668385458946.5161318331663488.73457018458961.782505512
1663562.95423801458972.592195168 1663649.6354951458984.611200005
#Sta/Elev= 30
       0  893.45    11.4   885.4    24.6  872.52    34.6  863.93    44.6  854.49
    51.2  850.33    64.5  845.43    87.2  835.46    97.7  832.19   107.6  830.78
   134.2  829.59   150.8   826.6   156.3  824.04   167.4  816.09   177.4  810.54
   187.3  806.73  195.93804.8549   230.5  804.22   260.9804.8546   273.6  808.26
   276.9  810.02   283.6  815.36   286.9  816.61   300.3  817.25   310.1  820.29
   333.3  820.12   359.8  821.12     383  823.16   412.8  829.23     425  833.34
#Mann= 5 ,-1,0
       0      .1       0   157.5     .06       0  195.93    .045       0
   260.9     .06       0   282.5      .1       0
Bank Sta=195.93,260.9
XS Rating Curve= 0 ,0
Exp/Cntr(USF)=0,0
Exp/Cntr=0.3,0.1

Type RM Length L Ch R = 1 ,7200    ,298,300,300.9
XS GIS Cut Line= 6
1663219.03333792 459287.342549921663305.34287658459272.957736179
1663379.32238743459260.6280364251663477.96195392459244.188436762
1663551.12092835459226.9358465821663636.13158509459204.758725584
#Sta/Elev= 30
       0  877.04    15.2   864.2    21.8  857.66    25.1  855.41    31.8  852.32
      43  844.95    61.7  841.94    71.7  839.16    82.9  837.94    91.7  835.15
   101.6  830.86   105.7  829.99   111.4  828.89   124.9  828.07   144.9  824.24
   168.2  810.95   178.1  807.93  186.94803.6959   194.8   802.7   231.3  802.47
  244.13803.6945     258  805.71   271.4  810.26   278.1     814   301.7  814.74
   311.8  818.67     349  819.72   386.3  822.09     410  824.84   425.5  827.45
#Mann= 5 ,-1,0
       0      .1       0   137.5     .06       0  186.94    .045       0
  244.13     .06       0   322.5      .1       0
Bank Sta=186.94,244.13
XS Rating Curve= 0 ,0
Exp/Cntr(USF)=0,0
Exp/Cntr=0.3,0.1

Type RM Length L Ch R = 1 ,6900    ,300,300,300.2
XS GIS Cut Line= 6
1663269.63527083459570.5368654281663356.54585817    459560.39745
1663431.04078792459551.7065225091663530.36703284459540.118619174
1663604.86196259459531.4276916681663691.77222183459521.288276255
#Sta/Elev= 30
       0  900.23     3.7  895.01    13.7  886.02    20.3  878.22    33.5  868.83
    40.1  860.72    43.4  855.44    46.7   851.8    59.9  844.58    66.5  841.86
    89.6  837.22   119.3  821.76   139.2  815.72   155.7  813.35     159  812.12
   165.6  807.75  177.33803.1098   185.4   802.2   231.7  802.03  239.18  803.11
   242.5  803.76   251.5  804.25   271.3     812   277.9  812.94   291.1  812.54
   297.7  815.83     301  816.52   327.4  816.26   373.7   819.2     425  831.14
#Mann= 5 ,-1,0
       0      .1       0   117.5     .06       0  177.33    .045       0
  239.18     .06       0   242.5      .1       0
Bank Sta=177.33,239.18
XS Rating Curve= 0 ,0
Exp/Cntr(USF)=0,0
Exp/Cntr=0.3,0.1

Type RM Length L Ch R = 1 ,6600    ,310.6,300.4,293.5
XS GIS Cut Line= 6
1663304.26249817459868.3718996791663391.18784925459858.301053673
1663465.68901259459849.6632756741663565.02345958459838.146238342
1663639.52429484459829.5084603431663726.43619451459819.439254761
#Sta/Elev= 30
       0  921.73     5.2  917.12    18.4  907.59      25  901.52    42.1  883.59
    48.1  875.87    55.8  867.51    61.4  862.63    77.6   850.6    87.8  844.72
     101  839.12   104.4  838.01   114.2  836.82   117.5  835.54   130.7  823.78
   143.9  814.07   157.1   809.5   163.7  805.62  172.36802.5137   180.3  801.39
   223.2  801.46  230.31802.5137   252.9  808.16     276  808.11   285.9  812.74
   289.3   813.1   335.5   813.6   401.5  815.98   408.2  817.13     425  821.96
#Mann= 5 ,-1,0
       0      .1       0  147.51     .06       0  172.36    .045       0
  230.31     .06       0  232.51      .1       0
Bank Sta=172.36,230.31
XS Rating Curve= 0 ,0
Exp/Cntr(USF)=0,0
Exp/Cntr=0.3,0.1