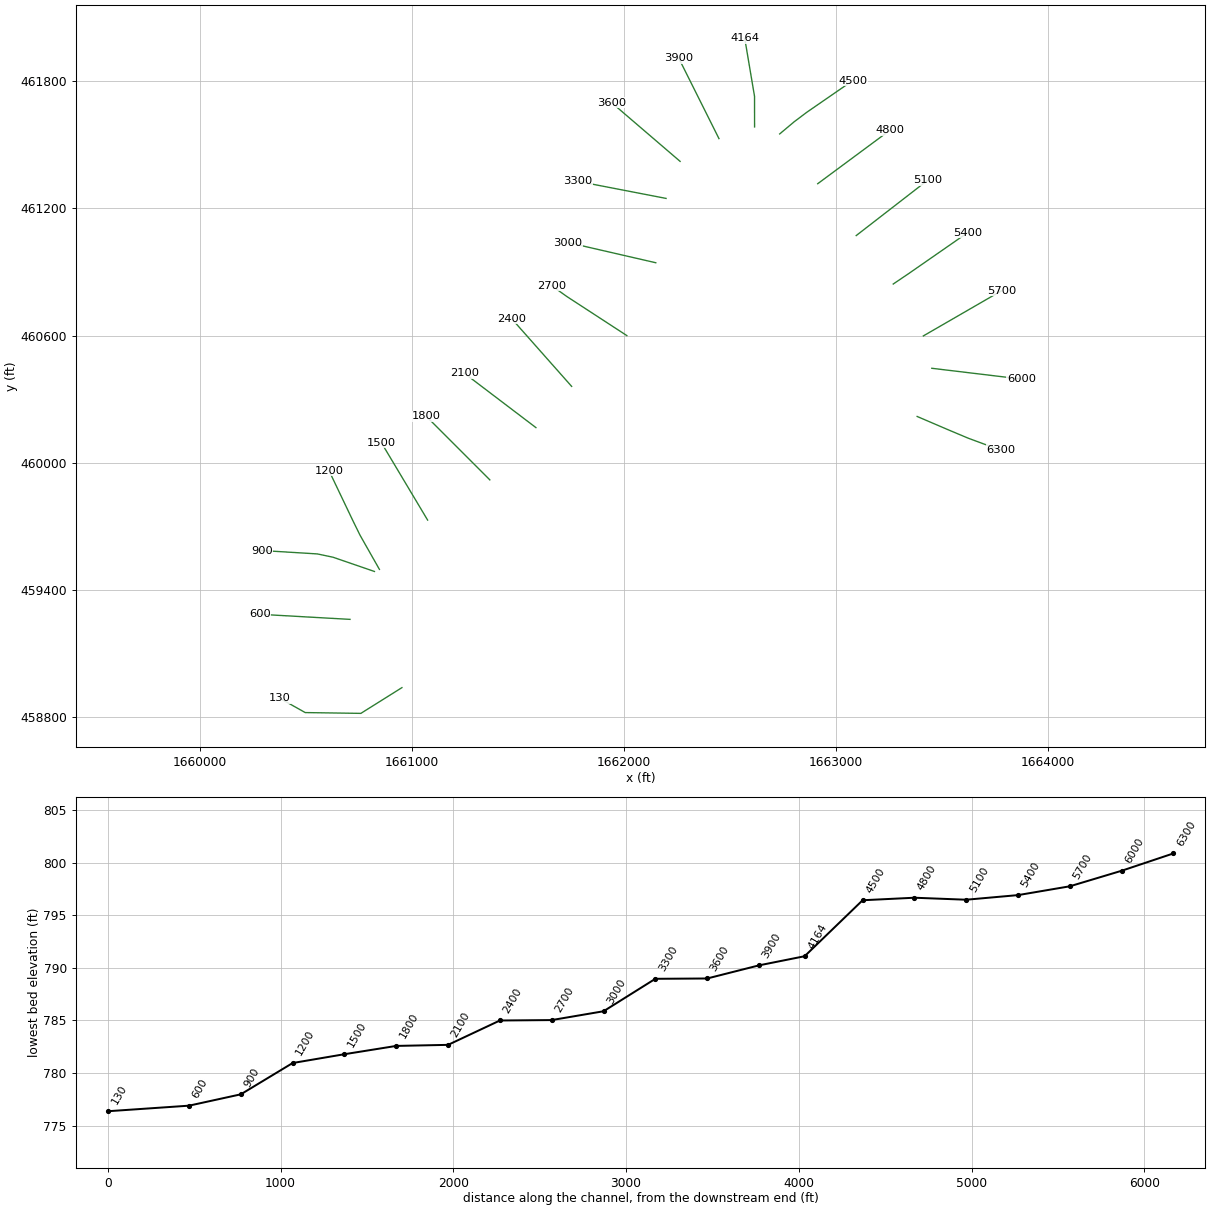
HEC-RAS study PenFrkFshCk.prj: PenFrkFshCk

--- PenFrkFshCk.g01 (geometry) --- (continued)

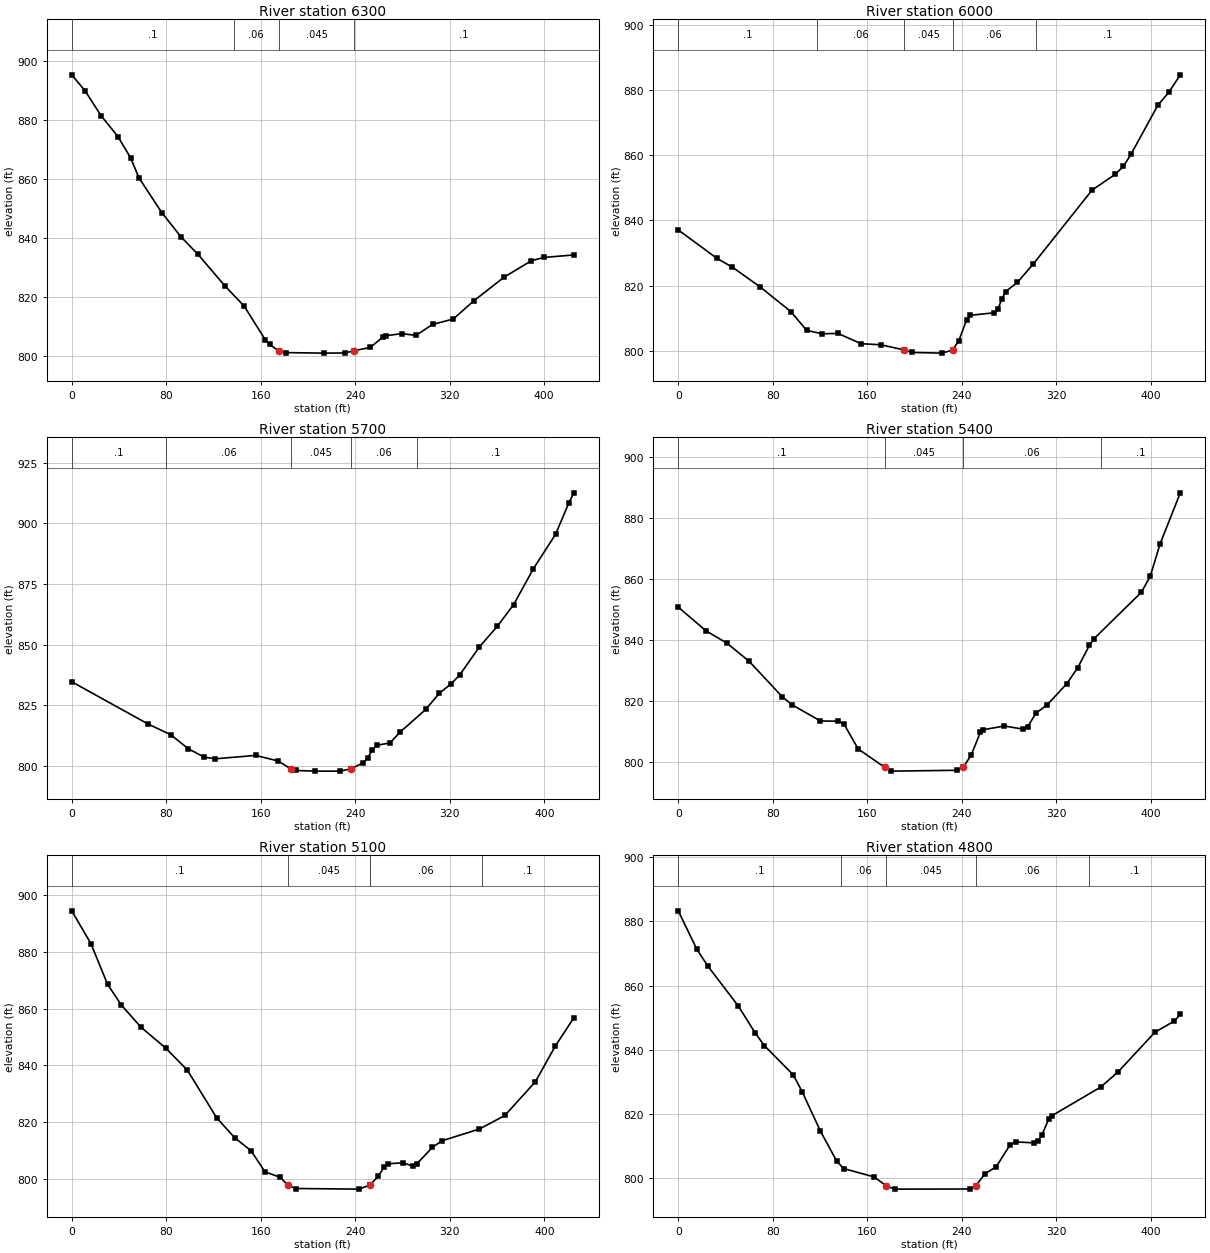
Type RM Length L Ch R = 1 ,6300    ,292.3,299.6,305.8
XS GIS Cut Line= 6
1663381.80663443460219.221591666 1663462.2319985460184.753484756
1663531.16788426460155.2095805851663623.36651875460116.480983511
1663693.79091859460090.4101695121663776.30715775460060.820989832
#Sta/Elev= 30
       0  895.33    11.3   889.9    24.8  881.48    39.1  874.38    49.8  867.19
    56.9   860.4    76.2  848.62    92.6  840.31   106.9  834.43   129.7  823.73
   146.1  816.84     164  805.38   167.5  803.85  175.13801.7512   181.8  801.09
   213.8  800.91   231.4  800.97  239.44801.7513   252.9  802.84   263.6  806.38
   266.5  806.84   279.5  807.52   291.6  806.93   305.6  810.64   323.1  812.48
   340.6  818.66   366.2  826.68   389.4  832.26   399.8  833.37   425.3  834.22
#Mann= 4 ,-1,0
       0      .1       0   137.5     .06       0  175.13    .045       0
  239.44      .1       0
Bank Sta=175.13,239.44
XS Rating Curve= 0 ,0
Exp/Cntr(USF)=0,0
Exp/Cntr=0.3,0.1

Type RM Length L Ch R = 1 ,6000    ,284.2,300,313.3
XS GIS Cut Line= 6
1663450.88818917460446.4944310931663537.76465584460436.069583178
1663612.23071426460427.1335774211663711.51824534460415.218903095
1663785.98397568460406.2832254171663872.86077042460395.857721344
#Sta/Elev= 30
       0  837.08    32.7  828.37    45.9  825.63      69  819.68    95.5  811.96
   108.7  806.23   121.9  805.21   135.1  805.31   154.9  802.15   171.5  801.83
  191.49800.2111   197.9  799.47   223.4  799.26  232.19800.2115   237.5  803.06
   244.1  809.51     247  810.87   267.7  811.65   270.6  812.74   273.9  815.88
   277.2  818.16   287.1  820.98   300.3  826.51   350.3  849.31   369.7   854.1
   376.8  856.57   383.2  860.26   406.1  875.43   415.2  879.28     425  884.69
#Mann= 5 ,-1,0
       0      .1       0   117.5     .06       0  191.49    .045       0
  232.19     .06       0   302.5      .1       0
Bank Sta=191.49,232.19
XS Rating Curve= 0 ,0
Exp/Cntr(USF)=0,0
Exp/Cntr=0.3,0.1

Type RM Length L Ch R = 1 ,5700    ,296.9,300,302.3
XS GIS Cut Line= 6
1663410.86071017460599.0663044151663486.62433818460642.839838922
1663551.56449701460680.3604331761663638.15126608460730.387892172
1663703.09142493460767.9081583321663778.85472484460811.682020918
#Sta/Elev= 30
       0  834.65    64.7  817.19    83.7  812.83    98.8  806.95   112.2  803.55
   121.6  802.87   155.7  804.27   174.7  801.96  185.34798.7369   189.8  798.04
   205.9  797.78   227.2  797.78  236.52 798.737   246.7  801.27   250.4  803.09
   254.2  806.37     258  808.43   269.4  809.41   277.9  813.88   299.6  823.22
     311  829.85   321.2  833.84   328.4  837.48   345.1  849.06   360.3  857.59
     374  866.48   390.8  881.34   409.5   895.5   420.9   908.6     425  912.63
#Mann= 5 ,-1,0
       0      .1       0      80     .06       0  185.34    .045       0
  236.52     .06       0   292.5      .1       0
Bank Sta=185.34,236.52
XS Rating Curve= 0 ,0
Exp/Cntr(USF)=0,0
Exp/Cntr=0.3,0.1

Type RM Length L Ch R = 1 ,5400    ,298.1,300,301.7
XS GIS Cut Line= 6
1663268.96401234460843.8679801671663341.48322426460892.842291668
1663403.09563383460935.6082822531663485.24507584460992.629821762
1663546.85715733461035.3958123331663618.73791909461085.289413333
#Sta/Elev= 30
       0  850.75    23.6  842.95      41     839      60  832.98    88.1  821.34
    96.4  818.69   120.4   813.4   135.5  813.32   140.2  812.46   152.3  804.21
  174.77798.1802   180.3  796.94   236.2  797.22  241.35  798.18   248.2  802.39
   255.7  809.63     258  810.52   276.1  811.75   292.1   810.7   295.8  811.51
   302.8  815.97   312.3  818.69   328.8  825.58   338.2  830.89     348  838.19
     352  840.41     392  855.61   399.5  860.81   407.9  871.55     425  888.26
#Mann= 4 ,-1,0
       0      .1       0  174.77    .045       0  241.35     .06       0
  357.51      .1       0
Bank Sta=174.77,241.35
XS Rating Curve= 0 ,0
Exp/Cntr(USF)=0,0
Exp/Cntr=0.3,0.1

Type RM Length L Ch R = 1 ,5100    ,300.7,300,299.1
XS GIS Cut Line= 6
 1663094.3114745461072.3183106781663163.49998443461125.883492261
1663222.80399968 461171.796458171663301.87667617461233.013527334
1663361.18069142461278.9268213361663430.34426701461332.524155095
#Sta/Elev= 30
       0  894.36    16.3  882.75    30.3  868.51      42  861.22    58.4  853.53
    79.5  846.08    97.8  838.37   122.7  821.54   137.9  814.57   151.7  810.02
   163.6  802.57   176.6  800.63  182.68 797.948   189.4  796.72   243.2   796.5
  252.33797.9462   252.5     798   259.5  801.05   264.2  804.14   267.9  805.41
   280.4  805.78   288.7  804.56   292.3  805.48   305.3  811.19   313.3  813.49
   345.1  817.63   366.6  822.41   392.4  834.24   409.4  846.87     425  856.74
#Mann= 5 ,-1,0
       0      .1       0  182.68    .045       0  252.33      .1       0
   252.5     .06       0   347.5      .1       0
Bank Sta=182.68,252.33
XS Rating Curve= 0 ,0
Exp/Cntr(USF)=0,0
Exp/Cntr=0.3,0.1

Type RM Length L Ch R = 1 ,4800    ,302.6,300,298.9
XS GIS Cut Line= 6
1662912.88893709461316.9287138431662983.21622425461368.989305258
1663043.49694359461413.6125755911663123.87145476461473.110488087
1663184.15184601461517.7334303411663254.47946125461569.794021755
#Sta/Elev= 30
       0  883.32    15.7  871.38    25.1  866.11    50.9  853.66      65  845.38
    72.9  841.36    97.4  832.24   104.9  827.02   120.4  814.71   134.2  805.37
   140.1  803.09   165.9  800.48  175.99797.7362   183.2  796.69   247.3  796.73
  251.91797.7364   259.7  801.48   269.1  803.63   281.1  810.57   285.9  811.38
   301.5  811.09   304.3  811.54   307.9  813.56   313.6  818.48     316  819.48
   357.6  828.45   372.3  833.17   403.6  845.56   419.9  848.99     425  851.09
#Mann= 5 ,-1,0
       0      .1       0   137.5     .06       0  175.99    .045       0
  251.91     .06       0   347.5      .1       0
Bank Sta=175.99,251.91
XS Rating Curve= 0 ,0
Exp/Cntr(USF)=0,0
Exp/Cntr=0.3,0.1

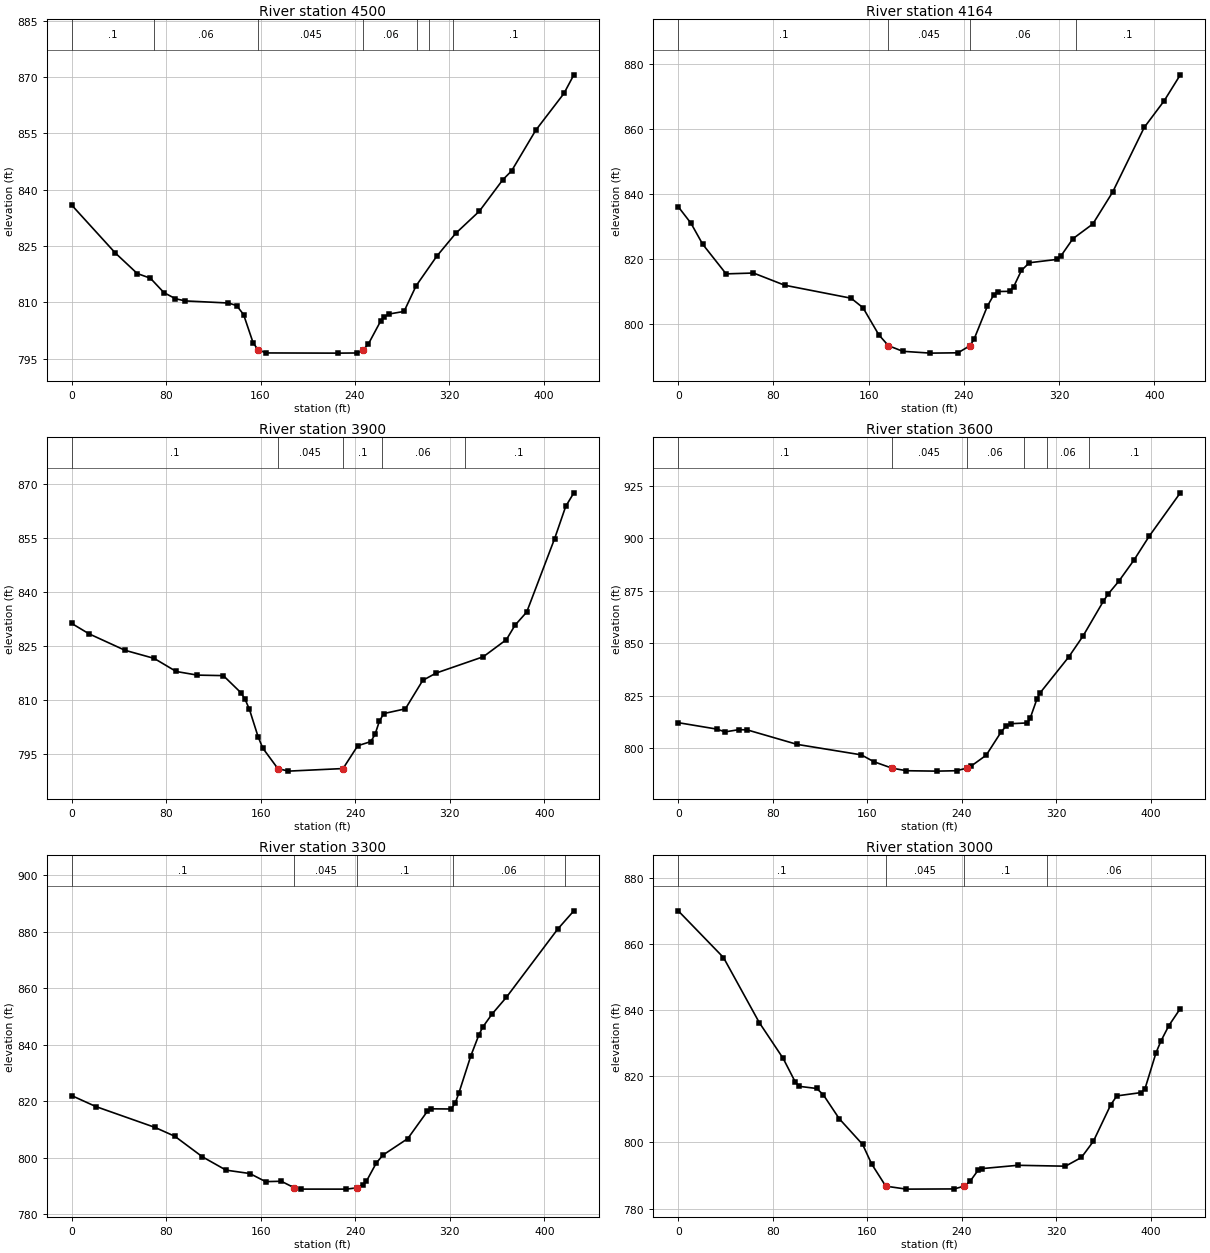
Type RM Length L Ch R = 1 ,4500    ,280.3,335.7,370.4
XS GIS Cut Line= 6
1662733.51003076461551.6287037581662800.81862317461608.152540833
1662860.74370018 461653.365376921662943.06505784461710.138885424
1663004.80607609461752.7188527581663076.83710001461802.395590678
#Sta/Elev= 30
       0  835.84    36.9  823.11    55.5  817.64    66.6   816.4    78.1  812.56
    87.9  810.93    96.2  810.35   132.7  809.79   139.7  809.12   145.6  806.72
   153.7  799.19   157.9  797.33   164.7   796.5   225.8  796.45   241.7  796.49
  247.22797.3557   251.4   798.9   261.7  804.94   264.5  806.07   268.7  806.85
   281.6  807.55   291.8  814.36   309.3  822.24   325.4  828.34   345.4  834.23
   365.3  842.61   372.7  844.95   393.2  855.78   417.1  865.58   425.5  870.54
#Mann= 7 ,-1,0
       0      .1       0      70     .06       0   157.9    .045       0
  247.22     .06       0  292.96      .1       0  302.96     .06       0
  322.96      .1       0
Bank Sta=157.9,247.22
XS Rating Curve= 0 ,0
Exp/Cntr(USF)=0,0
Exp/Cntr=0.3,0.1

Type RM Length L Ch R = 1 ,4164    ,252.5,264.3,271.1
XS GIS Cut Line= 3
1662615.01967348461584.6025120661662614.87925598461728.706381417
1662568.65149604462002.429674279
#Sta/Elev= 30
       0  836.12    10.7  831.04    20.5  824.61    40.2  815.48    63.2  815.74
    89.4  811.99   145.2     808   155.2  805.07   168.5  796.73   176.5 793.421
   188.6  791.68   211.8  791.12     235  791.22     245   793.4   248.4  795.34
   259.7   805.6     265  809.01   268.3  810.06   278.3  810.11   281.6  811.42
   288.2  816.52   294.9   818.9   318.2  819.93   321.6  821.08   331.5  826.29
   348.2  830.81   364.8  840.57   391.4   860.5   408.1  868.65   421.7  876.66
#Mann= 4 ,-1,0
       0      .1       0   176.5    .045       0     245     .06       0
   334.1      .1       0
Bank Sta=176.5,245
XS Rating Curve= 0 ,0
Exp/Cntr(USF)=0,0
Exp/Cntr=0.3,0.1

Type RM Length L Ch R = 1 ,3900    ,286.4,300,311.4
XS GIS Cut Line= 6
1662447.05948818461529.6976452621662407.92800476461607.959955916
1662374.38706134461675.0418427591662329.66536601461764.484577253
1662296.12442259461831.5664640961662256.99293917 461909.82877475
#Sta/Elev= 30
       0  831.25    14.6  828.38    45.1   823.8    69.7  821.56    88.4  817.92
   106.3  816.91   128.3  816.77     143  812.08   146.7   810.2   150.4  807.38
   157.7  799.82   161.7  796.63  174.43790.9647   183.4  790.25  229.61790.9651
   242.1  797.31   253.1  798.44   256.7  800.43   260.4  804.13   264.1  806.23
   282.4  807.55   297.1  815.45   308.4  817.48   348.4  822.02   367.9  826.76
   375.2  830.76   385.1  834.42   408.7  854.79   418.1  863.75     425  867.53
#Mann= 5 ,-1,0
       0      .1       0  174.43    .045       0  229.61      .1       0
   262.5     .06       0   332.5      .1       0
Bank Sta=174.43,229.61
XS Rating Curve= 0 ,0
Exp/Cntr(USF)=0,0
Exp/Cntr=0.3,0.1

Type RM Length L Ch R = 1 ,3600    ,284.6,300,315.4
XS GIS Cut Line= 6
1662263.83216435461422.2513378411662197.39758593461479.195449665
1662140.45314601461528.0047352611662064.52744484461593.084001422
  1662007.583333461641.893287003 1661941.1484265461698.837726921
#Sta/Elev= 30
       0  812.12    32.7  809.05    39.6  807.72    51.3  808.78    58.3  808.69
   100.7  801.75     155  796.76   165.5  793.51  180.97790.4175   193.2  789.19
   218.8     789   235.6  789.19  244.13790.4186   247.6  791.27   260.7   796.6
   273.5  807.84   277.8  810.62   282.1  811.65   295.6     812   297.9  814.22
   303.7  823.51   306.2  826.26   330.5  843.44   342.6  853.41   359.9   870.1
   364.2  873.68   372.9  879.59   385.8  889.72   398.8   901.2     425  921.79
#Mann= 6 ,-1,0
       0      .1       0  180.97    .045       0  244.13     .06       0
   292.5      .1       0   312.5     .06       0   347.5      .1       0
Bank Sta=180.97,244.13
XS Rating Curve= 0 ,0
Exp/Cntr(USF)=0,0
Exp/Cntr=0.3,0.1

Type RM Length L Ch R = 1 ,3300    ,302,300,298.8
XS GIS Cut Line= 6
1662197.57376668461247.5945349191662111.66350542461264.199160501
1662038.02651359461278.4314154981661939.84363909461297.407755509
1661866.20631917461311.640338585  1661780.296386461328.244636089
#Sta/Elev= 30
       0  822.02    20.4  818.16    70.2  810.83    87.2  807.67   110.6  800.39
   130.6  795.68   150.7  794.49   164.1  791.62   177.4  791.75  188.23789.4626
   194.1  788.98   232.5  788.97  241.75789.4632   246.6   790.5   249.4  791.76
   257.8  798.22   263.4  801.01   284.4  806.83   301.1  816.54   304.4  817.36
   321.1   817.3   324.5  819.28   327.8   823.1   337.8  836.09   344.5  843.37
   347.8   846.2   355.8  850.89   367.9  856.79   411.3  880.88     425  887.36
#Mann= 5 ,-1,0
       0      .1       0  188.23    .045       0  241.75      .1       0
   322.5     .06       0   417.5      .1       0
Bank Sta=188.23,241.75
XS Rating Curve= 0 ,0
Exp/Cntr(USF)=0,0
Exp/Cntr=0.3,0.1

Type RM Length L Ch R = 1 ,3000    ,312.4,300,289.4
XS GIS Cut Line= 6
1662149.23232792460944.1788031761662063.96281342460963.809013262
  1661990.874705 460980.635095091661893.42378442461003.070089594
1661820.33534792461019.8958433421661735.06583342461039.526381508
#Sta/Elev= 30
       0  870.08    38.3  855.95    68.6  836.27    88.8  825.44    98.9  818.41
   102.2  816.99   117.2  816.33   122.7  814.48   136.3  807.18   156.1  799.39
   163.7   793.5  175.66 786.778   193.1  785.88   233.5  785.94  242.13786.7811
     247  788.23   253.7  791.53   257.1  792.09   287.4  793.09   327.8  792.82
   341.3  795.47   351.4  800.34   366.2  811.46   371.3  814.09   391.8  815.09
   395.1  816.25   404.5   827.2   408.6  830.68   415.3  835.35     425  840.51
#Mann= 4 ,-1,0
       0      .1       0  175.66    .045       0  242.13      .1       0
   312.5     .06       0
Bank Sta=175.66,242.13
XS Rating Curve= 0 ,0
Exp/Cntr(USF)=0,0
Exp/Cntr=0.3,0.1

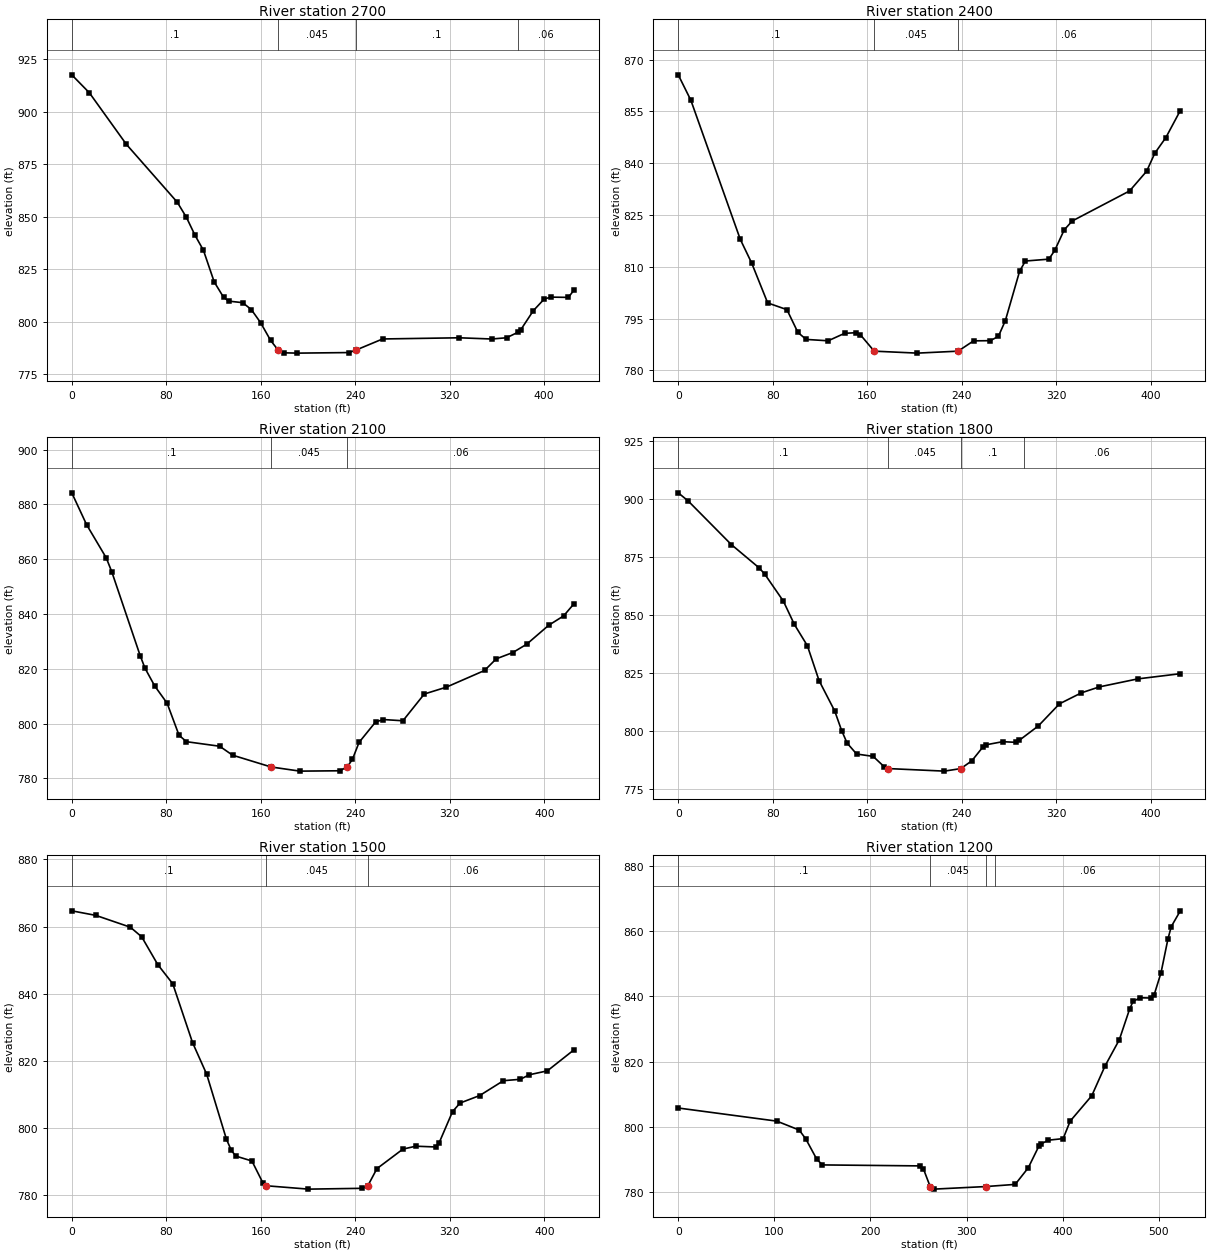
Type RM Length L Ch R = 1 ,2700    ,309.3,300,292
XS GIS Cut Line= 6
1662012.91206251460600.5407109261661939.58707793460648.287006512
  1661876.737138460689.2124495951661792.93743683460743.779925749
1661730.08749692460784.7053688321661658.74511993 460835.49627775
#Sta/Elev= 30
       0  917.47    14.9  908.92    46.2  884.41    89.3  856.87    97.1  849.62
   104.4  841.07   111.5  833.95   120.6  818.91   128.5  811.64   132.8  809.79
   144.7  809.05     152  805.78   159.8  799.61   168.4  791.05  174.83786.4196
   179.4  785.19   191.1  785.04   234.8  785.31  240.32786.4189   263.2  791.78
   328.1  792.34   355.6  791.76   368.1  792.35   377.5  794.89   380.2  796.19
   390.8  805.24   400.1  810.84   405.8  811.69   420.5  811.56   425.1  814.98
#Mann= 4 ,-1,0
       0      .1       0  174.83    .045       0  240.32      .1       0
   377.5     .06       0
Bank Sta=174.83,240.32
XS Rating Curve= 0 ,0
Exp/Cntr(USF)=0,0
Exp/Cntr=0.3,0.1

Type RM Length L Ch R = 1 ,2400    ,290.8,300,304.5
XS GIS Cut Line= 6
1661752.38075942460361.0982764211661694.36512743460426.599785835
1661644.63753659460482.743702427 1661578.3341915460557.602476582
1661528.60660067460613.7467212531661470.59096867460679.248230666
#Sta/Elev= 30
       0  865.58    10.7   858.2    52.5  817.96    62.2  811.05    75.7  799.54
      92  797.59   101.3  790.99   108.3  788.97   126.9  788.57   140.8  790.73
   150.1  790.91   154.2  790.31  165.89785.5691   202.4     785  236.88 785.568
     250  788.55   264.2  788.61     271  789.85   276.9  794.41     289  808.75
   293.9  811.67   313.7  812.21   318.7  814.73   326.7  820.68   333.5  823.26
   382.1  831.97   396.5  837.67   403.4  842.88   412.8  847.43     425  855.24
#Mann= 3 ,-1,0
       0      .1       0  165.89    .045       0  236.88     .06       0
Bank Sta=165.89,236.88
XS Rating Curve= 0 ,0
Exp/Cntr(USF)=0,0
Exp/Cntr=0.3,0.1

Type RM Length L Ch R = 1 ,2100    ,305.5,300,296.9
XS GIS Cut Line= 6
1661583.90898351460166.7955154181661514.21981843460219.707483083
1661454.48634209460265.0604107531661374.84148826460325.531418428
1661315.10801192460370.8846741771661245.41884685460423.796641842
#Sta/Elev= 30
       0  884.22    12.6  872.56    29.2  860.48    33.9  855.37    57.9  824.82
      62  820.22    70.2  813.76    80.7  807.46    90.8  795.77    97.1  793.42
   125.2  791.76   136.1   788.5  168.71784.1958   193.1  782.68   226.8  782.81
  233.15784.1943   237.6     787   243.2  793.18   257.2  800.62   263.8   801.5
   280.3  801.05   298.4  810.81   316.9  813.29   349.4   819.4   359.3  823.65
   373.4  825.96   385.1  828.99   403.8  835.93   416.3   839.3     425  843.68
#Mann= 3 ,-1,0
       0      .1       0  168.71    .045       0  233.15     .06       0
Bank Sta=168.71,233.15
XS Rating Curve= 0 ,0
Exp/Cntr(USF)=0,0
Exp/Cntr=0.3,0.1

Type RM Length L Ch R = 1 ,1800    ,308.2,300,293.4
XS GIS Cut Line= 6
1661366.60725276459920.2533575891661304.73532926459982.125281096
1661251.70262693460035.1583115011661180.99181034460105.868799999
1661127.95877993 460158.901830421661066.08685642460220.773753926
#Sta/Elev= 30
       0  902.53     8.4  899.03    44.9  880.25    68.7  870.09    73.4  867.36
      89  855.84    98.3  845.81   109.3  836.65   119.2  821.61   132.5  808.45
   138.3  800.08     143  794.62     151  789.95     165  788.94   174.2  784.53
  177.88 783.678   225.3  782.58  239.22 783.677   248.5  787.02   257.8  792.91
   260.7  793.94   274.6  795.27   285.6     795   288.5  795.79   304.8  802.05
   322.7  811.59   341.3  816.33   356.4  818.88   388.9  822.33     425  824.57
#Mann= 4 ,-1,0
       0      .1       0  177.88    .045       0  239.22      .1       0
   292.5     .06       0
Bank Sta=177.88,239.22
XS Rating Curve= 0 ,0
Exp/Cntr(USF)=0,0
Exp/Cntr=0.3,0.1

Type RM Length L Ch R = 1 ,1500    ,304.4,300,299.2
XS GIS Cut Line= 6
1661073.19412567459730.6641698331661028.31921542459805.780489415
1660989.85472542 459870.166187421660938.56906684459956.013784751
1660900.10490492460020.3994827571660855.22999467460095.515802339
#Sta/Elev= 30
       0   864.7    20.4  863.34    49.6  859.82    59.2  856.95    72.8  848.68
    85.5  842.96   102.2  825.47   114.2  816.02   130.9  796.68   135.1   793.3
   138.9  791.63   152.5  790.17   161.8  783.64  164.15782.8055   200.3  781.79
   245.9  782.03  250.64 782.809   258.3  787.89   280.3  793.71   291.2  794.58
     308  794.35   310.9  795.53   322.3  804.88   328.7  807.44   345.3  809.67
   365.4   814.1   379.7  814.51   387.3  815.86   402.6  817.03     425  823.26
#Mann= 3 ,-1,0
       0      .1       0  164.15    .045       0  250.64     .06       0
Bank Sta=164.15,250.64
XS Rating Curve= 0 ,0
Exp/Cntr(USF)=0,0
Exp/Cntr=0.3,0.1

Type RM Length L Ch R = 1 ,1200    ,279.9,300,326.2
XS GIS Cut Line= 6
1660845.90621334459498.1688083651660754.68524826459658.965166256
1660721.55408092 459726.256698341660678.45607001459816.492738336
1660646.13264383459884.1700964271660608.42208934459963.126631424
#Sta/Elev= 30
       0  805.78   102.6  801.76   125.9  799.03   132.8  796.27   144.1  790.13
     150  788.36   251.4  788.06   255.1  787.16  262.12781.7386     266  780.95
  320.24781.7415   350.6   782.4   364.2  787.48   375.2  794.09   377.7  794.81
   385.1  795.93   400.5  796.41   407.8  801.76   430.3  809.55   444.1  818.66
   458.9  826.65   469.6  836.02   473.2  838.38   480.5  839.52   491.4  839.45
   495.1  840.35   502.3  847.15   509.6  857.61     513  861.31   522.4  866.13
#Mann= 4 ,-1,0
       0      .1       0  262.12    .045       0  320.24      .1       0
  329.87     .06       0
Bank Sta=262.12,320.24
XS Rating Curve= 0 ,0
Exp/Cntr(USF)=0,0
Exp/Cntr=0.3,0.1

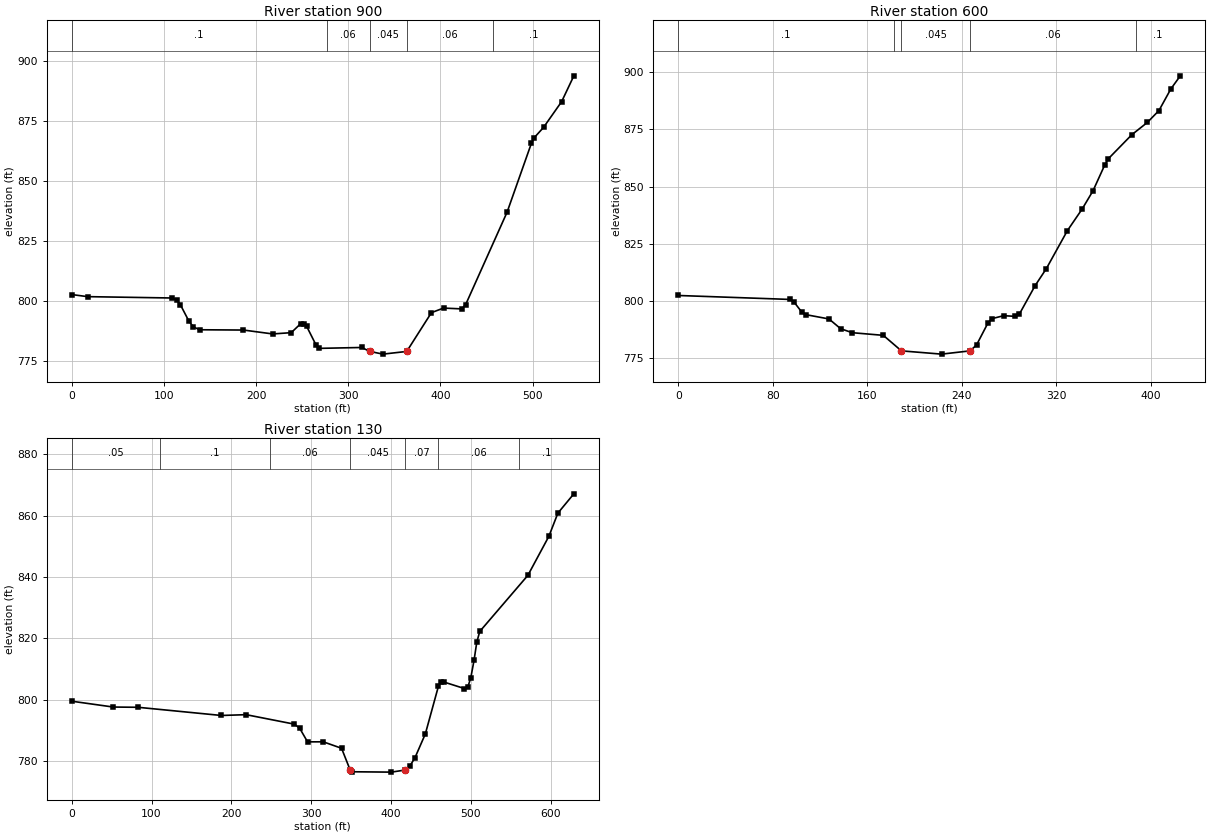
Type RM Length L Ch R = 1 ,900     ,300.9,300,300
XS GIS Cut Line= 6
1660822.40757007459488.2887563511660627.24029317459555.449625254
 1660553.0567145459571.0821399241660453.24359392459577.193348169
1660378.38383551459581.776672333  1660291.047396459587.124102592
#Sta/Elev= 30
       0  802.78    17.2  801.91   108.8  801.35     114  800.43   117.8  798.57
   126.9  791.84   131.6  789.42   138.6  788.12   186.3     788     218  786.38
   238.1  786.91   248.2   790.6   251.5  790.68   254.9  789.49   264.9  781.85
   268.3  780.37   314.6  780.74  323.46 779.085   337.6  777.97  363.39779.0865
   390.2  795.25   403.3  797.15     423  796.81   427.3  798.58   472.3  837.13
   498.6  865.74   501.9   868.2   511.8   872.4   531.5  883.17   544.7  893.89
#Mann= 5 ,-1,0
       0      .1       0   276.4     .06       0  323.46    .045       0
  363.39     .06       0  457.21      .1       0
Bank Sta=323.46,363.39
XS Rating Curve= 0 ,0
Exp/Cntr(USF)=0,0
Exp/Cntr=0.3,0.1

Type RM Length L Ch R = 1 ,600     ,471,469.6,470.2
XS GIS Cut Line= 6
1660707.23029068459262.4571010021660619.86793259459267.364571512
1660544.98619258459271.5712560121660445.14354451459277.180168673
1660370.26147643459281.3868531731660282.89911833459286.294651762
#Sta/Elev= 30
       0   802.5    94.8  800.77      98  799.64   104.6  795.23   107.9  794.14
   127.6  792.25   137.5  787.98   147.3  786.25   173.6  785.09  188.93778.3143
   222.9  776.89  247.05778.3147   252.5  780.88   262.3  790.62   265.6  792.39
   275.5  793.68   285.3  793.38   288.6  794.22   302.1   806.8   311.6  814.23
   329.4  830.81   341.9  840.25   351.1  848.22   360.9  859.34   364.2  862.28
   383.9  872.68   397.1  878.07   406.9  883.24     417  892.71     425  898.42
#Mann= 5 ,-1,0
       0      .1       0   182.5     .06       0  188.93    .045       0
  247.05     .06       0   387.5      .1       0
Bank Sta=188.93,247.05
XS Rating Curve= 0 ,0
Exp/Cntr(USF)=0,0
Exp/Cntr=0.3,0.1

Type RM Length L Ch R = 1 ,130     ,,,
XS GIS Cut Line= 4
1660951.93071805458940.4480233611660758.41222704458819.124347761
1660496.03275752458822.8995919271660375.34244926458890.700903601
#Sta/Elev= 30
       0  799.49      52  797.59      83  797.51   187.5  794.84   218.5   795.1
   279.1     792   285.6  790.67   295.5  786.23   315.1  786.25   338.1  784.14
  348.88 777.052   351.2  776.48   400.5  776.36  418.01 777.051   423.4  778.25
     430     781   443.1  788.83   459.5  804.38   462.8  805.68   466.1  805.77
     492  803.63   496.3  804.09   500.1   807.2   504.1   812.8   507.6  818.79
   511.3  822.25   571.6  840.55   597.9  853.28   609.2  860.85   629.2  867.14
#Mann= 7 ,-1,0
       0     .05       0     110      .1       0   248.4     .06       0
  348.88    .045       0  418.01     .07       0   458.4     .06       0
  560.81      .1       0
Bank Sta=348.88,418.01
XS Rating Curve= 0 ,0
Exp/Cntr(USF)=0,0
Exp/Cntr=0.3,0.1
LCMann Table=0

Chan Stop Cuts=-1
Use User Specified Reach Order=0
Composite Channel Slope=5